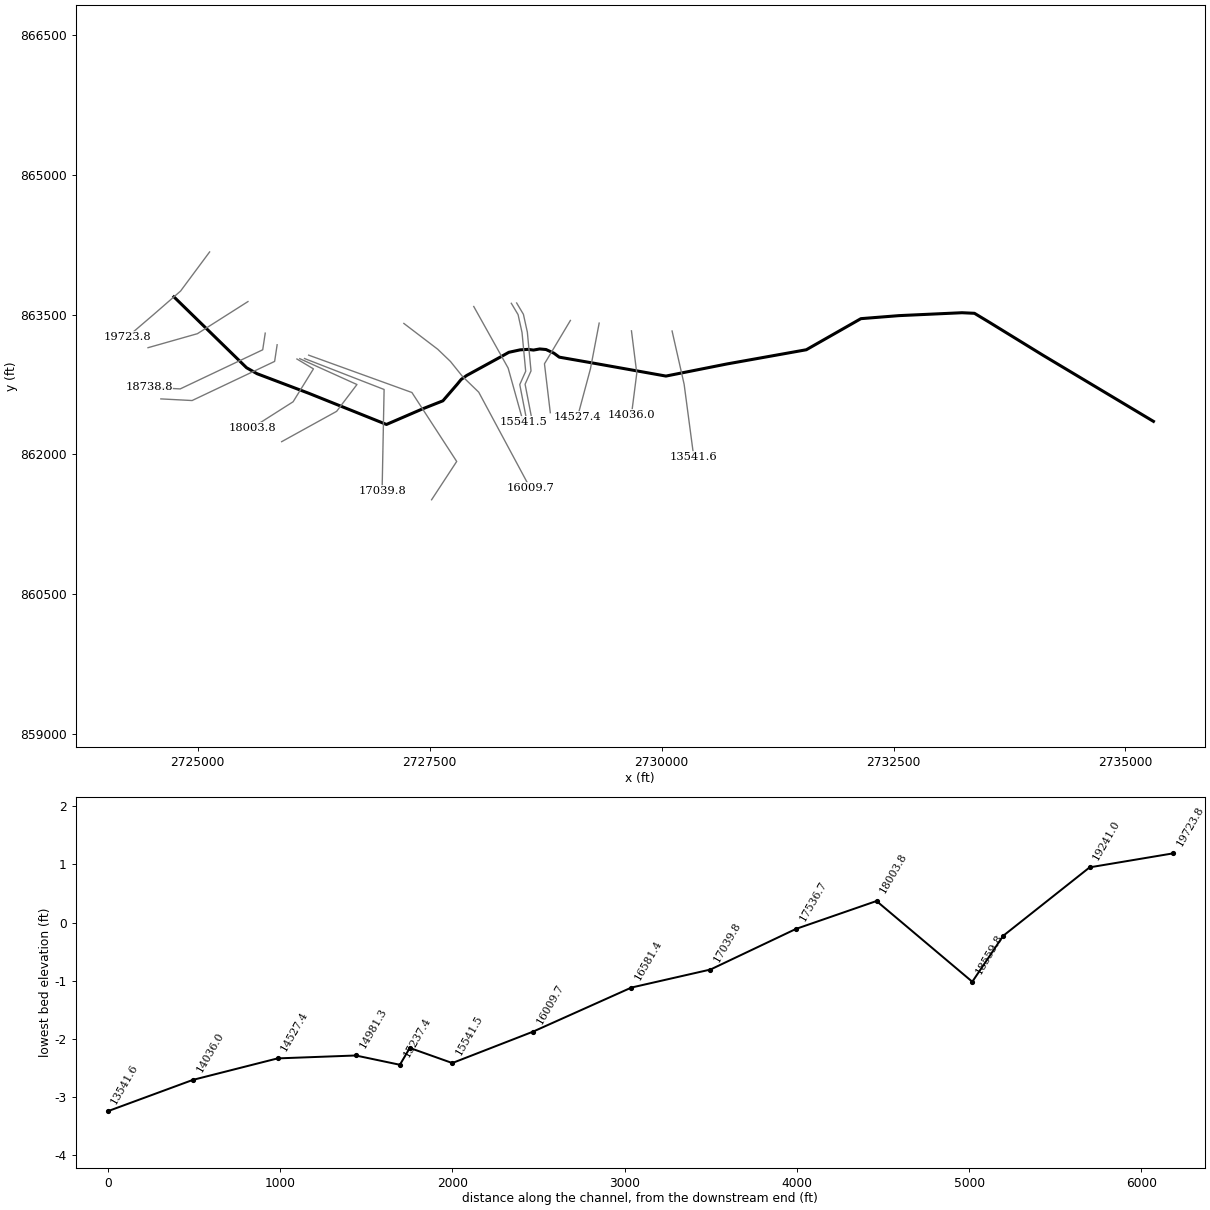
--- BURNT MILL CREEK.PRJ (project) ---

Proj Title=Burnt Mill Creek
Current Plan=p01
Default Exp/Contr=.3,.1
English Units
Geom File=g01
Flow File=f01
Plan File=p01
Y Axis Title=Elevation
X Axis Title(PF)=Main Channel Distance
X Axis Title(XS)=Station
BEGIN DESCRIPTION:
PASQUOTANK RIVER BASIN
BURNT MILL CREEK
HCFCD Unit X###-##-##
(Flood Hazard, Floodway) Model/
10, 2, 1, 0.2% Event
Filename:  N:\NC_flood\60227\Baker\ENG\Yeopim Basin\Burnt Mill Creek.prj
Prepared by:  ________     Date: ________
Reviewed by:  ________     Date: ________
STATUS (Draft RAS, SVSQ, FINAL)
END DESCRIPTION:
DSS Export Rating Curves= 0
DSS Export Rating Curve Sorted= 0
DSS Export Volume Flow Curves= 0
DXF OffsetX= 0
DXF OffsetY= 0
DXF ScaleX= 1
DXF ScaleY= 10

--- Burnt Mill Creek.p01 (plan) ---

Plan Title=100 Year Single
Version=Version 3.0.1  Mar 2001
Short Identifier=Plan01
Geom File=g01
Flow File=f01
Subcritical Flow
K Sum by GR= 0
Std Step Tol= 0.01
Critical Tol= 0.01
Num of Std Step Trials= 20
Max Error Tol= 0.3
Flow Tol Ratio= 0.001
Split Flow NTrial= 30
Split Flow Tol= 0.02
Split Flow Ratio= 0.02
Log Output Level= 0
Friction Slope Method= 1
Unsteady Friction Slope Method= 2
Parabolic Critical Depth
Global Vel Dist= 0 , 0 , 0
Global Log Level= 0
CheckData=True
Encroach Param=-1 ,0,0, 2
Encroach River=Burnt Mill Creek
Encroach Reach=Reach - 1
Encroach Node=19723.8
       1 4856.03 5179.51
Encroach Node=19241.0
       1 4976.17 5133.16
Encroach Node=18738.8
       1 4883.17 5102.98
Encroach Node=18649.3
       4     .75
Encroach Node=18559.8
       1 4883.17 5102.98
Encroach Node=18003.8
       1    4900    5070
Encroach Node=17536.7
       1    4880    5106
Encroach Node=17039.8
       1  4703.4 5143.69
Encroach Node=16581.4
       1    4715 5056.67
Encroach Node=16009.7
       1    4506    5120
Encroach Node=15541.5
       1  4746.6 5119.92
Encroach Node=15294.9
       1 4866.45 5080.47
Encroach Node=15266.1
       4     .75
Encroach Node=15237.4
       1 4866.45 5080.47
Encroach Node=14981.3
       1 4966.64 5118.96
Encroach Node=14527.4
       1 4946.85  5211.6
Encroach Node=14036.0
       1 4894.76 5089.98
Encroach Node=13541.6
       1    4835    5036
Encroach Node=13040.2
       1 4911.57 5018.47
Encroach Node=12542.1
       1 4832.88  5102.7
Encroach Node=12042.9
       1    4953    5213
Encroach Node=11543.6
       1    4770    5018
Encroach Node=11027.6
       1 4837.72 5076.27
Encroach Node=10544.0
       1 4921.92  5102.8
Encroach Node=10017.8
       1    4700    5110
Encroach Node=9524.3
       1 4810.95 5139.87
Encroach Node=9019.1
       1 4863.65 5276.46
Encroach Node=8515.3
       1 4803.33 5194.15
Encroach Node=8020.1
       1 4733.42 5166.44
Computation Interval=1HOUR
Output Interval=1HOUR
Run HTab= 0
Run UNet= 0
Run PostProcess= 0
UNET Theta= 1
UNET ZTol= 0.02
UNET ZSATol= 0.1
UNET MxIter= 20
UNET MaxInSteps= 20
UNET DtIC= 0
UNET DtMin= 0
UNET MaxCRTS= 20
UNET WFStab= 2
UNET SFStab= 1
UNET WFX= 1
UNET SFX= 1
UNET Convert EG Bridges=-1
UNET Use Existing IB Tables=-1
Instantaneous Interval=1HOUR
Write IC File= 0
Write Velocity= 0
Write Detailed= 0

--- Burnt Mill Creek.f01 (steady flow) ---

Flow Title= 100 Year Single
Version=Version 3.0.1  Mar 2001
Number of Profiles= 2
Profile Names=100-Year,Floodway
River Rch & RM=Burnt Mill Creek,Reach - 1       ,19723.8
     736     736
River Rch & RM=Burnt Mill Creek,Reach - 1       ,17039.8
    1092    1092
River Rch & RM=Burnt Mill Creek,Reach - 1       ,11543.6
    1126    1126
River Rch & RM=Burnt Mill Creek,Reach - 1       ,10017.8
    1591    1591
Boundary for River Rch & Prof#=Burnt Mill Creek,Reach - 1       , 1
Up Type= 0
Dn Type= 3
Dn Slope=.0004
Boundary for River Rch & Prof#=Burnt Mill Creek,Reach - 1       , 2
Up Type= 0
Dn Type= 1
Dn Known WS=4.87
DSS Import GetInterval= 0
DSS Import GetPeak= 0
DSS Import FillOption= 0

--- BURNT MILL CREEK.g01 (geometry) ---

Geom Title=Geom 01 by CodeH2 for Windows

River Reach=Burnt Mill Creek,Reach - 1
Reach XY= 30
 2724742.5975367 863689.59262772      2725525.61       862929.43
      2725638.89       862865.19      2726196.68       862655.05
      2727033.75       862320.77      2727422.54       862487.73
      2727642.42       862574.38      2727797.97        862753.6
      2727838.21       862802.61      2727898.88       862846.27
      2728271.61       863049.24      2728353.02       863094.74
      2728475.13       863121.08       2728557.9       863126.27
       2728618.8       863118.68      2728685.85       863130.66
      2728754.24       863124.56      2728839.47       863084.98
      2728896.95       863042.71      2729236.79       862983.54
      2730046.66       862839.82      2730706.77       862970.23
      2731559.87       863122.18      2732148.39       863455.78
      2732558.48       863488.21      2733238.38       863519.39
      2733372.49       863513.16      2733524.56       863421.99
      2734114.77       863060.93 2735302.1777169 862353.76642249

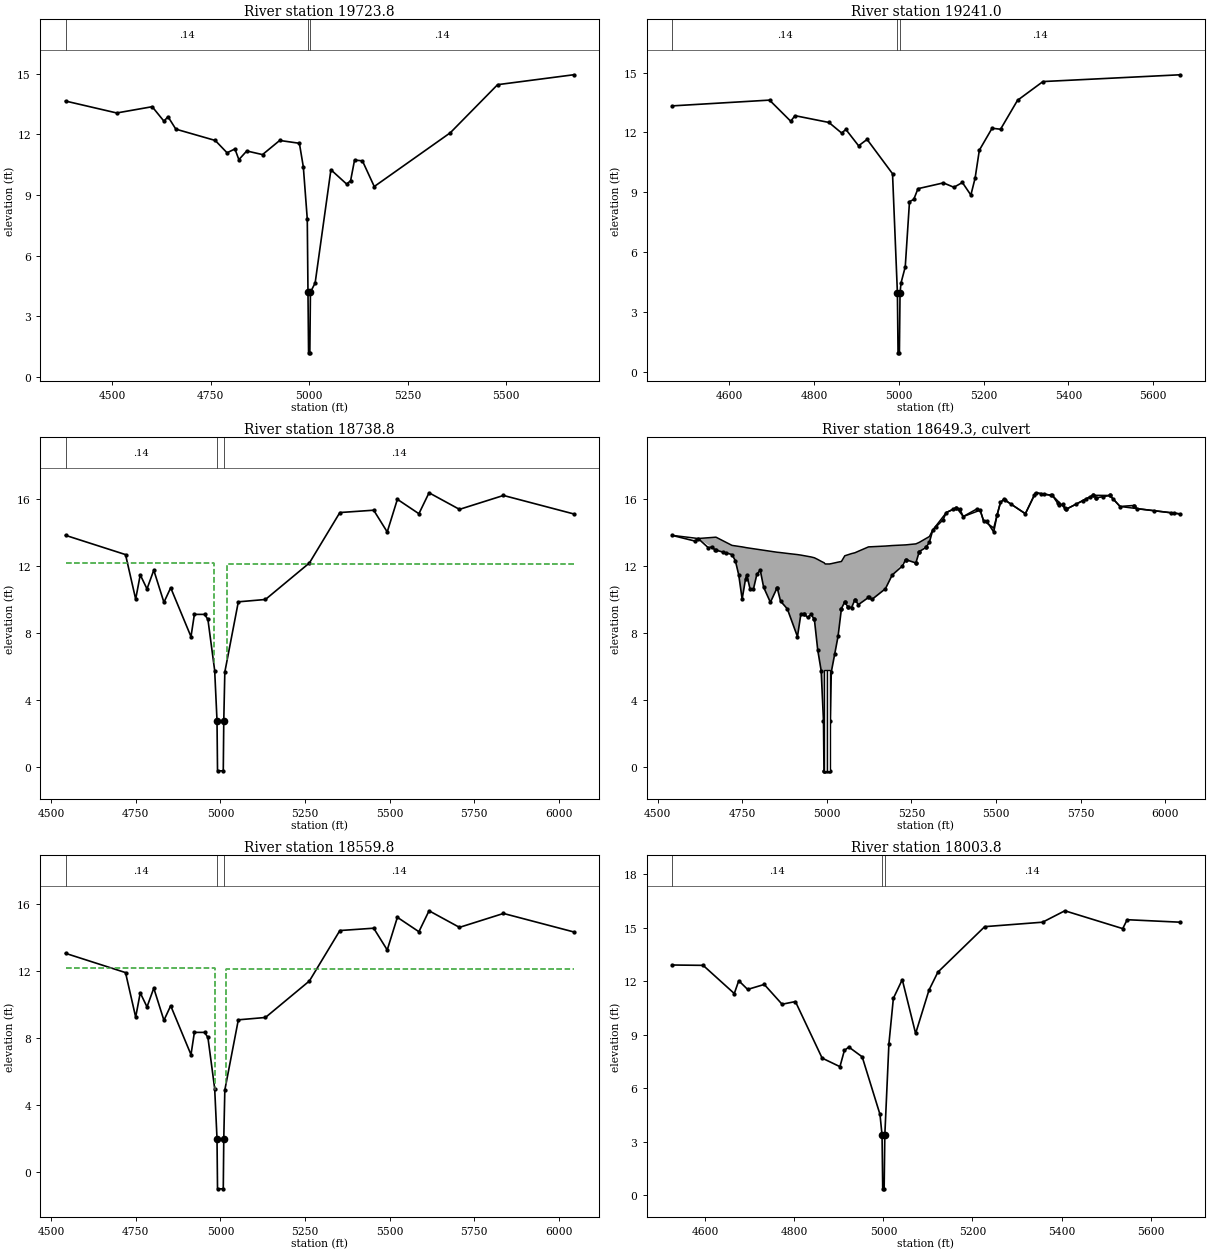
Type RM Length L Ch R = 1 ,19723.8,482.8,482.8,482.8
XS GIS Cut Line= 5
 2725127.4670341 864171.35000414 2724814.3071431 863751.71575015
 2724532.4632412 863507.45103513 2724238.0929436  863256.9231223
 2724238.0929436 863263.18632012
BEGIN DESCRIPTION:
Burnt Mill Creek 35.0
END DESCRIPTION:
#Sta/Elev= 30
  4381.5   13.65  4511.5   13.06  4601.5   13.37  4631.5   12.65  4641.5   12.88
  4661.5   12.26  4761.5    11.7  4791.5   11.09  4811.5   11.28  4821.5   10.75
  4841.5   11.18  4881.5      11  4925.1    11.7  4975.1   11.56  4985.1   10.39
  4995.1    7.81  4996.9    4.19  4998.4    1.19  5001.6    1.19  5003.1    4.19
  5015.1    4.65  5055.1   10.25  5095.1    9.54  5105.1    9.71  5115.1   10.73
  5135.1   10.69  5165.1    9.42  5358.1   12.08  5478.1   14.46  5670.9   14.95
#Mann= 3 , 1 , 0
 4381.50    0.14       0  4996.9   0.045       0  5003.1    0.14       0
Bank Sta=4996.90,5003.10
Exp/Cntr=0.3,0.1

Type RM Length L Ch R = 1 ,19241.0,502.2,502.2,502.2
XS GIS Cut Line= 3
 2725540.8380903 863638.97818937 2724995.9398799 863294.50230922
 2724463.5680651 863144.18556152
BEGIN DESCRIPTION:
Burnt Mill Creek 34.0
END DESCRIPTION:
#Sta/Elev= 30
  4465.4   13.33  4695.4   13.62  4745.4   12.56  4755.4   12.84  4835.4    12.5
  4865.4   11.97  4875.4   12.15  4905.4   11.33  4925.4   11.65  4985.4    9.93
  4996.9    3.95  4998.4    0.95  5001.6    0.95  5003.1    3.95  5005.4    4.45
  5015.4    5.26  5025.4    8.53  5035.4    8.64  5045.4    9.18  5105.4    9.47
  5130.1    9.25  5150.1    9.49  5170.1    8.86  5180.1    9.71  5190.1   11.11
  5220.1   12.21  5240.1   12.16  5280.1   13.61  5340.1   14.55  5663.2   14.89
#Mann= 3 , 1 , 0
 4465.40    0.14       0  4996.9   0.045       0  5003.1    0.14       0
Bank Sta=4996.90,5003.10
Exp/Cntr=0.3,0.1

Type RM Length L Ch R = 1 ,18738.8,179,179,179
XS GIS Cut Line= 4
 2725727.0111513 863300.41881254 2725699.8660500 863121.71356203
 2724810.2686133 862702.04471478 2724473.5283407 862719.63562454
BEGIN DESCRIPTION:
Upstream Section of Bridge/Culvert/Weir
END DESCRIPTION:
#Sta/Elev= 30
  4542.2   13.83  4719.6   12.68  4749.6   10.02  4763.1   11.47  4783.1   10.63
  4803.1   11.75  4833.1    9.83  4853.1    10.7  4913.1    7.78  4923.1    9.11
  4953.1    9.11  4963.1    8.81  4983.1    5.76    4990    2.77  4991.5   -0.23
  5008.5   -0.23    5010    2.77  5013.1    5.67    5053    9.86  5133.1      10
  5263.1   12.18  5353.1   15.19  5453.1   15.33  5493.1   14.03  5523.1   15.98
  5586.7   15.12  5616.7   16.37  5706.6   15.38  5836.7   16.21  6043.8   15.11
#Mann= 3 , 1 , 0
 4542.20    0.14       0    4990   0.045       0    5010    0.14       0
#XS Ineff= 2 , 0
       0    4980   12.19    5020       0   12.11
Bank Sta=4990.00,5010.00
Exp/Cntr=0.5,0.3

Type RM Length L Ch R = 2 ,18649.3,,,
BEGIN DESCRIPTION:
US Highway 17 - TOR
Structure ID: 34
Approximate Survey Structure
END DESCRIPTION:
Bridge Culvert--1,0,-1,-1, 0
Deck Dist Width WeirC Skew NumUp NumDn MinLoCord MaxHiCord MaxSubmerge Is_Ogee
10,159,3,, 60, 60,,,0.95,0,1,1,,
  4542.2  4619.6  4672.2  4719.6  4729.6  4739.6  4749.6  4763.1  4773.1  4783.1
  4793.1  4803.1  4813.1  4833.1  4853.1  4863.1  4883.1  4913.1  4923.1  4953.1
  4963.1  4973.1  4983.1    4990  4991.5  4995.1  5008.5    5010  5013.1  5033.1
  5043.1    5053  5073.1    5083  5093.1    5123  5133.1  5173.1  5193.1    5233
  5263.1  5273.1  5303.1  5313.1  5353.1  5383.1  5403.1  5453.1  5463.1  5493.1
  5513.1  5523.1  5586.7  5616.7  5666.7  5706.6  5786.6  5836.7  5866.7  6043.8
   13.81   13.62    13.7   13.21   13.18   13.15   13.12   13.07   13.04   13.01
   12.98   12.95   12.92   12.86    12.8   12.78   12.73   12.66   12.63   12.52
   12.47   12.37   12.26   12.19   12.18    12.1    12.1   12.11   12.12   12.21
   12.25   12.59   12.72   12.77   12.86   13.12   13.13   13.17    13.2   13.24
    13.3   13.39   13.74   14.13   15.17   15.46   14.93   15.31   14.68   14.25
   15.77   15.96    15.1   16.35   16.19   15.36    16.2   16.19   15.53   15.09
   13.81   13.62   12.93   12.66   12.29   11.44      10   11.45    10.6   10.61
   11.48   11.73   10.71    9.81   10.68    9.88    9.42    7.76    9.09    9.09
    8.79    6.95    5.74    2.75   -0.25   -0.25   -0.25    2.75    5.65    7.78
    9.44    9.84     9.5    9.97    9.67    10.1    9.98   10.62   11.44   12.36
   12.16   12.84    13.4   14.13   15.17   15.46   14.93   15.31   14.68   14.01
   15.77   15.96    15.1   16.35   16.19   15.36    16.2   16.19   15.53   15.09
  4542.2  4619.6  4672.2  4719.6  4729.6  4739.6  4749.6  4763.1  4773.1  4783.1
  4793.1  4803.1  4813.1  4833.1  4853.1  4863.1  4883.1  4913.1  4923.1  4953.1
  4963.1  4973.1  4983.1    4990  4991.5  4995.1  5008.5    5010  5013.1  5033.1
  5043.1    5053  5073.1    5083  5093.1  5133.1  5173.1  5193.1    5233  5263.1
  5273.1  5303.1  5313.1  5353.1  5383.1  5403.1  5453.1  5463.1  5493.1  5513.1
  5523.1  5586.7  5616.7  5666.7  5706.6  5786.6  5836.7  5866.7  6016.6  6043.8
   13.41   13.58    13.7   13.21   13.18   13.15   13.12   13.07   13.04   13.01
   12.98   12.95   12.92   12.86    12.8   12.78   12.73   12.66   12.63   12.52
   12.47   12.37   12.26   12.19   12.18    12.1    12.1   12.11   12.12   12.21
   12.25   12.59   12.72   12.77   12.86   13.13   13.17    13.2   13.24    13.3
   13.39   13.74   13.74   14.78   15.07   14.54   14.92   14.29   14.25   15.38
   15.57   14.71   15.96    15.8   14.97   15.81    15.8   15.14   15.08   14.69
   13.01   12.82   12.13   11.86   11.49   10.64     9.2   10.65     9.8    9.81
   10.68   10.93    9.91    9.01    9.88    9.08    8.62    6.96    8.29    8.29
    7.99    6.15    4.94    1.95   -1.05   -1.05   -1.05    1.95    4.85    6.98
    8.64    9.04     8.7    9.17    8.87    9.18    9.82   10.64   11.56   11.36
   12.04    12.6   13.33   14.37   14.66   14.13   14.51   13.88   13.21   14.97
   15.16    14.3   15.55   15.39   14.56    15.4   15.39   14.73   14.36   14.29
BR Coef= 1 , 0 , 0 ,1.25, 0 ,,,0.8,-1,2,0,
Wspro=,,,, 1 ,,,, 0 ,,,, 0 ,,,,-1 ,-1 ,-1 , 0 , 0 , 0 , 0 , 0
Culvert=2,6.0,8.0,159.0,0.015,0.4,1.0,8,1,-0.25,4995.55,-1.05,4995.55,Culvert #1  ,0,10
Culvert=2,6.0,8.0,159.0,0.015,0.4,1.0,8,1,-0.25,5004.55,-1.05,5004.55,Culvert #2  ,0,10
BC Design=,, 0 ,, 0 ,,,,,,
BR U #Sta/Elev= 124
  4542.2   13.81  4609.6   13.47  4619.6   13.62  4649.6   13.07  4659.6   13.12
  4669.6   12.94  4672.2   12.93  4692.2   12.81  4702.2   12.76  4719.6   12.66
  4729.6   12.29  4739.6   11.44  4749.6      10  4759.6    11.2  4763.1   11.45
  4773.1    10.6  4783.1   10.61  4793.1   11.48  4803.1   11.73  4813.1   10.71
  4833.1    9.81    4853   10.68  4853.1   10.68  4863.1    9.88  4883.1    9.42
  4913.1    7.76  4923.1    9.09    4933    9.12  4933.1    9.12  4943.1    8.91
  4953.1    9.09    4963    8.79  4963.1    8.79  4973.1    6.95  4983.1    5.74
    4990    2.75  4991.5   -0.25    4993   -0.25  4995.1   -0.25    5000   -0.25
  5007.3   -0.25  5008.5   -0.25    5010    2.75  5013.1    5.65    5023     6.7
  5033.1    7.78    5043    9.42  5043.1    9.44    5053    9.84  5053.1    9.84
    5063    9.51  5063.1    9.51  5073.1     9.5    5083    9.97  5083.1    9.97
  5093.1    9.67    5123    10.1  5123.1    10.1  5133.1    9.98  5173.1   10.62
  5193.1   11.44  5223.1   11.98    5233   12.36  5233.1   12.36    5263   12.16
  5263.1   12.16    5273   12.83  5273.1   12.84    5293   13.09  5293.1   13.09
  5303.1    13.4  5313.1   14.13    5323   14.33  5343.1   14.73  5353.1   15.17
    5373   15.36    5383   15.46  5383.1   15.46  5393.1   15.36  5403.1   14.93
  5443.1   15.38  5453.1   15.31  5463.1   14.68  5473.1   14.64  5493.1   14.01
    5503   15.02  5503.1   15.03  5513.1   15.77  5523.1   15.96  5526.7   15.91
    5543   15.69  5586.7    15.1    5613    16.2  5616.7   16.35    5633    16.3
    5643   16.27    5663    16.2  5666.7   16.19    5683   15.71  5686.7    15.6
  5696.7   15.67    5703   15.47  5706.6   15.36  5706.7   15.36  5736.6   15.67
  5756.6   15.88  5766.6   15.99  5776.6   16.09  5786.6    16.2  5786.7    16.2
  5796.6   16.05  5796.7   16.05  5816.6   16.12  5836.6   16.19  5836.7   16.19
  5846.6   15.97  5866.7   15.53  5906.6   15.59  5906.7   15.59  5916.4    15.4
  5966.6   15.28  6016.6   15.16  6026.6   15.13  6043.8   15.09
BR U #Mann= 3
 4542.20    0.14    4990   0.045    5010    0.14
BR U Banks=4990.00,5010.00
BR D #Sta/Elev= 124
  4542.2   13.01  4609.6   12.67  4619.6   12.82  4649.6   12.27  4659.6   12.32
  4669.6   12.14  4672.2   12.13  4692.2   12.01  4702.2   11.96  4719.6   11.86
  4729.6   11.49  4739.6   10.64  4749.6     9.2  4759.6    10.4  4763.1   10.65
  4773.1     9.8  4783.1    9.81  4793.1   10.68  4803.1   10.93  4813.1    9.91
  4833.1    9.01    4853    9.88  4853.1    9.88  4863.1    9.08  4883.1    8.62
  4913.1    6.96  4923.1    8.29    4933    8.32  4933.1    8.32  4943.1    8.11
  4953.1    8.29    4963    7.99  4963.1    7.99  4973.1    6.15  4983.1    4.94
    4990    1.95  4991.5   -1.05    4993   -1.05  4995.1   -1.05    5000   -1.05
  5007.3   -1.05  5008.5   -1.05    5010    1.95  5013.1    4.85    5023     5.9
  5033.1    6.98    5043    8.62  5043.1    8.64    5053    9.04  5053.1    9.04
    5063    8.71  5063.1    8.71  5073.1     8.7    5083    9.17  5083.1    9.17
  5093.1    8.87    5123     9.3  5123.1     9.3  5133.1    9.18  5173.1    9.82
  5193.1   10.64  5223.1   11.18    5233   11.56  5233.1   11.56    5263   11.36
  5263.1   11.36    5273   12.03  5273.1   12.04    5293   12.29  5293.1   12.29
  5303.1    12.6  5313.1   13.33    5323   13.53  5343.1   13.93  5353.1   14.37
    5373   14.56    5383   14.66  5383.1   14.66  5393.1   14.56  5403.1   14.13
  5443.1   14.58  5453.1   14.51  5463.1   13.88  5473.1   13.84  5493.1   13.21
    5503   14.22  5503.1   14.23  5513.1   14.97  5523.1   15.16  5526.7   15.11
    5543   14.89  5586.7    14.3    5613    15.4  5616.7   15.55    5633    15.5
    5643   15.47    5663    15.4  5666.7   15.39    5683   14.91  5686.7    14.8
  5696.7   14.87    5703   14.67  5706.6   14.56  5706.7   14.56  5736.6   14.87
  5756.6   15.08  5766.6   15.19  5776.6   15.29  5786.6    15.4  5786.7    15.4
  5796.6   15.25  5796.7   15.25  5816.6   15.32  5836.6   15.39  5836.7   15.39
  5846.6   15.17  5866.7   14.73  5906.6   14.79  5906.7   14.79  5916.4    14.6
  5966.6   14.48  6016.6   14.36  6026.6   14.33  6043.8   14.29
BR D #Mann= 3
 4542.20    0.14    4990   0.045    5010    0.14
BR D Banks=4990.00,5010.00

Type RM Length L Ch R = 1 ,18559.8,556,556,556
XS GIS Cut Line= 4
 2725855.4433434 863175.73452308 2725828.2982421 862997.02927258
 2724938.7008054 862577.36042533 2724601.9605327 862594.95133509
BEGIN DESCRIPTION:
Downstream Section of Bridge/Culvert/Weir
END DESCRIPTION:
#Sta/Elev= 30
  4542.2   13.04  4719.6   11.89  4749.6    9.23  4763.1   10.68  4783.1    9.84
  4803.1   10.96  4833.1    9.04  4853.1    9.91  4913.1    6.99  4923.1    8.32
  4953.1    8.32  4963.1    8.02  4983.1    4.97    4990    1.98  4991.5   -1.02
  5008.5   -1.02    5010    1.98  5013.1    4.88    5053    9.07  5133.1    9.21
  5263.1   11.39  5353.1    14.4  5453.1   14.54  5493.1   13.24  5523.1   15.19
  5586.7   14.33  5616.7   15.58  5706.6   14.59  5836.7   15.42  6043.8   14.32
#Mann= 3 , 1 , 0
 4542.20    0.14       0    4990   0.045       0    5010    0.14       0
#XS Ineff= 2 , 0
       0 4983.33   12.19 5016.67       0   12.11
Bank Sta=4990.00,5010.00
Exp/Cntr=0.5,0.3

Type RM Length L Ch R = 1 ,18003.8,467.1,467.1,467.1
XS GIS Cut Line= 4
 2726068.6198515 863022.97945962 2726246.6815887 862916.82727015
 2726027.5286814 862564.12805999 2725589.2228668  862286.7626617
BEGIN DESCRIPTION:
Burnt Mill Creek 33.5
END DESCRIPTION:
#Sta/Elev= 30
    4525   12.92    4595    12.9    4665   11.32    4675   12.04    4695   11.55
  4732.3   11.83  4772.3   10.72  4802.3   10.87  4862.3     7.7  4902.3    7.22
  4912.3    8.13  4922.3    8.32  4952.3    7.77  4992.3    4.54  4996.9    3.37
  4998.4    0.37  5001.6    0.37  5003.1    3.37  5012.3     8.5  5022.3   11.05
  5042.3    12.1  5072.3    9.08  5102.3   11.51  5122.3   12.52  5227.5   15.07
  5357.5   15.32  5407.5   15.96  5537.5   14.96  5547.5   15.46  5666.2   15.32
#Mann= 3 , 1 , 0
 4525.00    0.14       0  4996.9   0.045       0  5003.1    0.14       0
Bank Sta=4996.90,5003.10
Exp/Cntr=0.3,0.1

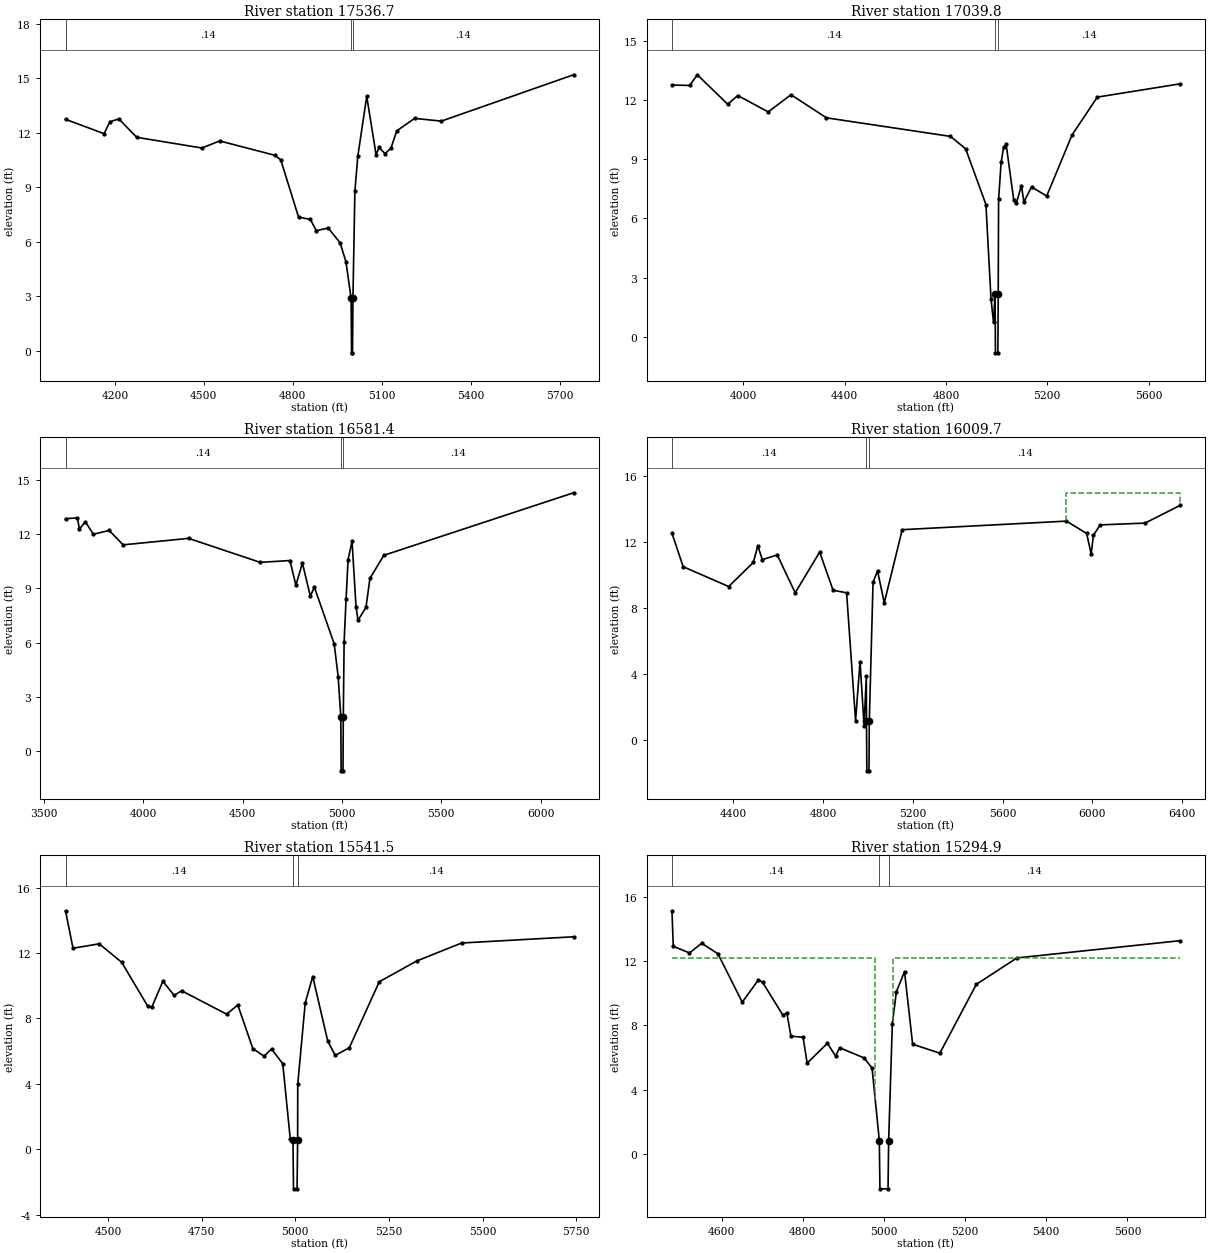
Type RM Length L Ch R = 1 ,17536.7,496.9,496.9,496.9
XS GIS Cut Line= 4
 2726099.4382291 863026.40372379 2726715.8057809 862749.03832551
 2726496.6528736  862461.4001347 2725904.2551711 862136.09503794
BEGIN DESCRIPTION:
Burnt Mill Creek 33.0
END DESCRIPTION:
#Sta/Elev= 30
  4033.7   12.74  4163.7   11.95  4183.7   12.61  4213.7   12.76  4273.7   11.75
  4493.7   11.16  4553.7   11.55  4739.6   10.76  4759.6   10.51  4819.6    7.36
  4859.6    7.23  4879.6    6.61  4919.6    6.76  4959.6    5.95  4979.6     4.9
  4996.9    2.89  4998.4   -0.11  5001.6   -0.11  5003.1    2.89  5009.6    8.77
  5019.6   10.72  5049.6      14  5081.2   10.79  5091.2   11.19  5111.2   10.85
  5131.2   11.15  5151.2   12.11  5211.2   12.79  5301.2   12.64  5747.1   15.19
#Mann= 3 , 1 , 0
 4033.70    0.14       0  4996.9   0.045       0  5003.1    0.14       0
Bank Sta=4996.90,5003.10
Exp/Cntr=0.3,0.1

Type RM Length L Ch R = 1 ,17039.8,458.4,458.4,458.4
XS GIS Cut Line= 3
 2726150.7278343  863027.8789688 2727008.4644722 862695.99092294
 2726986.9133004 861609.81186379
BEGIN DESCRIPTION:
Burnt Mill Creek 32.0
END DESCRIPTION:
#Sta/Elev= 30
    3718   12.75    3788   12.73    3818   13.27    3938   11.78    3978   12.22
    4098   11.39    4188   12.26    4328   11.09  4817.7   10.15  4877.7    9.52
  4957.7     6.7  4977.7    1.94  4987.7    0.73  4993.8    2.19  4995.3   -0.81
  5004.8   -0.81  5006.3    2.19  5007.7    6.97  5017.7    8.83  5027.7    9.61
  5037.7    9.74  5067.7    6.91  5077.7    6.76  5097.7    7.66  5107.7    6.83
  5137.7    7.59  5197.7    7.13  5297.7   10.22  5397.7   12.14  5724.1   12.81
#Mann= 3 , 1 , 0
 3718.00    0.14       0  4993.8   0.045       0  5006.3    0.14       0
Bank Sta=4993.80,5006.30
Exp/Cntr=0.3,0.1

Type RM Length L Ch R = 1 ,16581.4,571.7,571.7,571.7
XS GIS Cut Line= 4
 2726195.3176261 863064.07062973 2727308.2034834  862663.4317211
 2727791.0247322 861923.79065901 2727520.5078623 861512.87895785
BEGIN DESCRIPTION:
Burnt Mill Creek 31.5
END DESCRIPTION:
#Sta/Elev= 30
  3607.5   12.87  3667.5   12.92  3677.5    12.3  3707.5    12.7  3747.5   12.01
  3827.5   12.22  3897.5   11.42  4227.5   11.78  4587.5   10.45  4737.5   10.55
  4767.5    9.18  4800.3   10.41  4840.3    8.57  4860.3    9.08  4960.3    5.93
  4980.3    4.11  4993.7    1.88  4995.2   -1.12  5004.7   -1.12  5006.2    1.88
  5010.3    6.03  5020.3    8.44  5030.3    10.6  5050.3   11.62  5070.3    7.98
  5080.3    7.23  5120.3    7.95  5140.3    9.56  5210.3   10.84  6165.5   14.31
#Mann= 3 , 1 , 0
 3607.50    0.14       0  4993.7   0.045       0  5006.2    0.14       0
Bank Sta=4993.70,5006.20
Exp/Cntr=0.3,0.1

Type RM Length L Ch R = 1 ,16009.7,468.2,468.2,468.2
XS GIS Cut Line= 6
 2727221.4678021 863404.45799410 2727586.9067010 863127.18356757
 2727723.7445791 862996.56559305 2727854.3625536 862834.84810078
 2728028.5198530 862666.91070497 2728582.0912688 861640.62661946
BEGIN DESCRIPTION:
Burnt Mill Creek 31.0
END DESCRIPTION:
#Sta/Elev= 30
  4126.9   12.54  4176.9   10.51  4379.5    9.31  4489.5   10.77  4509.5   11.78
  4529.5   10.94    4596   11.23    4676    8.93  4785.1    11.4  4845.1    9.08
  4905.1    8.93  4945.1    1.17  4965.1    4.75    4983    0.85    4993    3.86
  4993.8    1.12  4995.3   -1.88  5004.8   -1.88  5006.3    1.12    5023    9.57
    5043   10.26    5073    8.32    5153   12.76    5885   13.28    5975   12.53
    5995   11.28    6005   12.41    6035   13.05    6235   13.16    6391   14.23
#Mann= 3 , 1 , 0
 4126.90    0.14       0  4993.8   0.045       0  5006.3    0.14       0
#XS Ineff= 2 , 0
       0                    5884       0      15
Bank Sta=4993.80,5006.30
Exp/Cntr=0.3,0.1

Type RM Length L Ch R = 1 ,15541.5,246.65,246.65,246.65
XS GIS Cut Line= 3
 2727974.8752155 863586.14120965 2728345.6693118 862925.45354706
 2728507.4703720 862349.03727001
BEGIN DESCRIPTION:
Burnt Mill Creek 30.0
END DESCRIPTION:
#Sta/Elev= 30
  4386.6   14.58  4406.6   12.29  4476.6   12.56  4536.6   11.43  4606.6    8.73
  4616.6    8.67  4646.6   10.27  4676.6    9.41  4696.6    9.69  4816.6    8.26
  4846.6    8.82  4886.6    6.16  4916.6    5.69  4936.6    6.13  4966.6    5.23
  4986.6    0.63  4993.8    0.58  4995.3   -2.42  5004.8   -2.42  5006.3    0.58
  5006.6    3.98  5026.6    8.95  5046.6   10.56  5086.6    6.62  5106.6    5.74
  5144.2     6.2  5224.2   10.24  5324.2   11.51  5444.2   12.61  5742.9   12.99
#Mann= 3 , 1 , 0
 4386.60    0.14       0  4993.8   0.045       0  5006.3    0.14       0
Bank Sta=4993.80,5006.30
Exp/Cntr=0.3,0.1

Type RM Length L Ch R = 1 ,15294.9,57.5,57.5,57.5
XS GIS Cut Line= 6
 2728379.8409075 863620.46310843 2728452.7453902 863498.95563727
 2728495.2730051 863307.58137021 2728534.7629333 862891.41828150
 2728470.9715109 862748.64700290 2728535.9408933 862414.94062954
BEGIN DESCRIPTION:
Upstream Section of Bridge/Culvert/Weir
END DESCRIPTION:
#Sta/Elev= 30
  4477.4   15.12  4480.6   12.91  4520.6    12.5  4550.6    13.1  4590.6   12.45
  4650.6    9.44  4690.6   10.83  4700.6   10.68  4750.6    8.64  4760.6    8.77
  4770.6    7.33  4800.6    7.26  4810.6    5.65  4860.6    6.89  4880.6    6.09
  4890.6    6.61  4950.6    5.98  4970.6    5.35  4988.5    0.84    4990   -2.16
    5010   -2.16  5011.5    0.84  5020.6    8.11  5030.6   10.09  5050.6   11.34
  5070.6    6.83  5137.7    6.27  5227.7   10.55  5327.7   12.19  5729.7   13.26
#Mann= 3 , 1 , 0
 4477.40    0.14       0  4988.5   0.045       0  5011.5    0.14       0
#XS Ineff= 2 , 0
       0  4978.5    12.2  5021.5       0    12.2
Bank Sta=4988.50,5011.50
Exp/Cntr=0.5,0.3

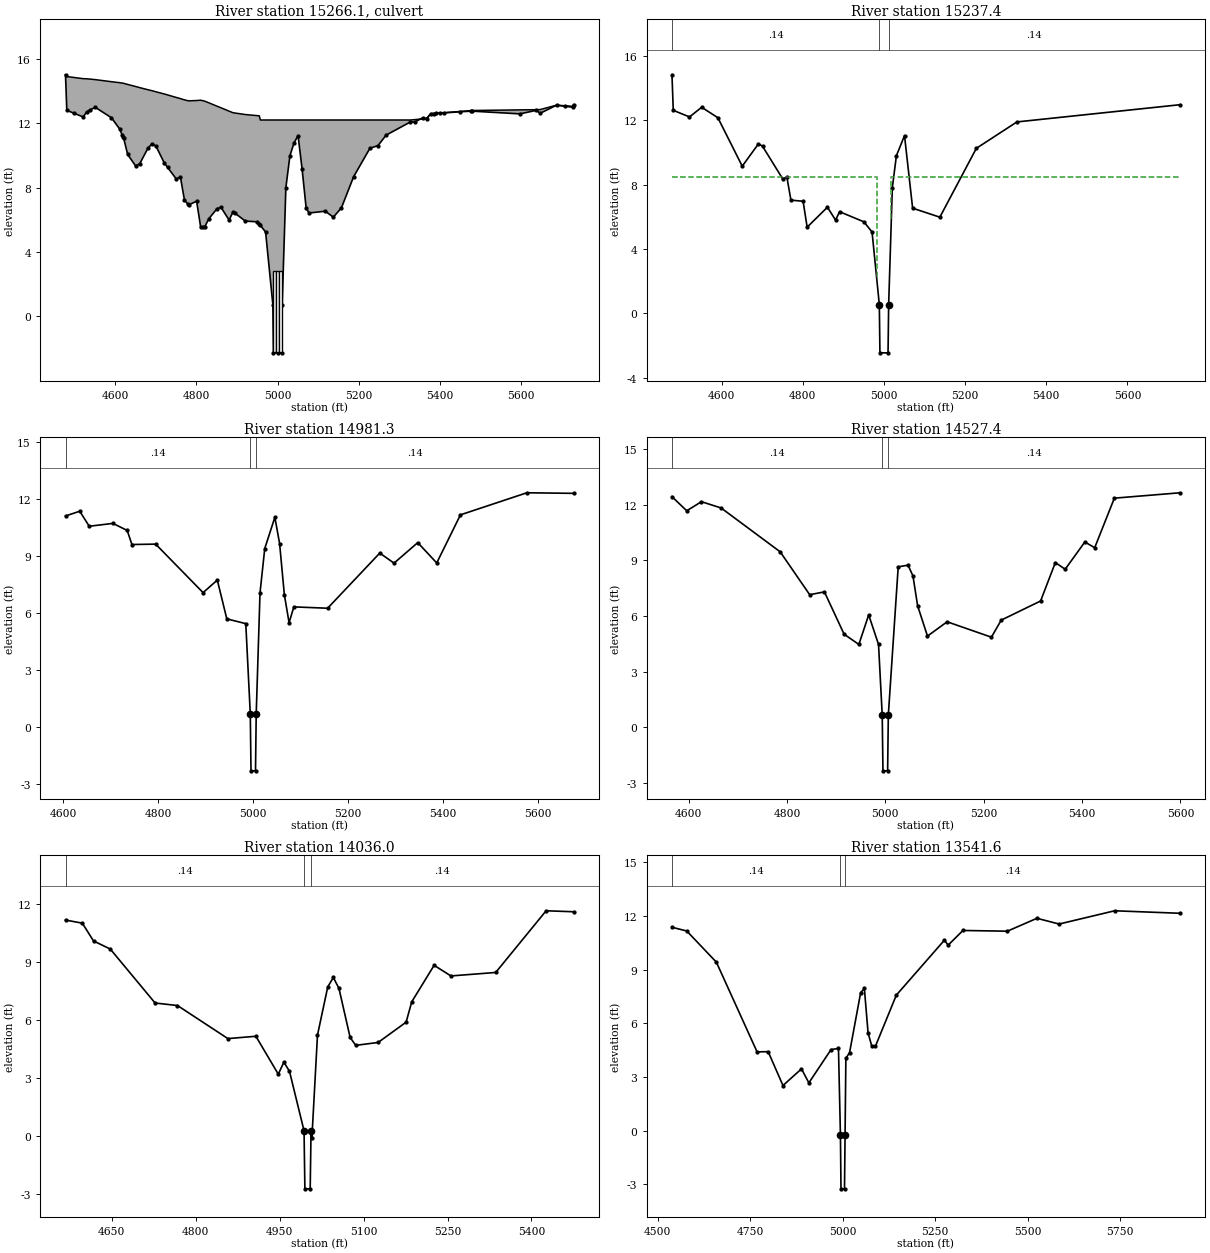
Type RM Length L Ch R = 2 ,15266.1,,,
BEGIN DESCRIPTION:
NC 37 -TOR
Structure ID: 35
Approximate Survey Structure
END DESCRIPTION:
Bridge Culvert--1,0,-1,-1, 0
Deck Dist Width WeirC Skew NumUp NumDn MinLoCord MaxHiCord MaxSubmerge Is_Ogee
10,37.5,3,, 60, 60,,,0.95,0,1,1,,
  4477.4  4480.6  4520.6  4530.6  4550.6  4590.6  4610.6  4620.6  4630.6  4650.6
  4660.6  4680.6  4690.6  4700.6  4720.6  4750.6  4760.6  4770.6  4780.6  4800.6
  4810.6  4820.6  4830.6  4850.6  4860.6  4880.6  4890.6  4920.6  4950.6  4955.1
  4957.7  4970.6  4988.5    4990    5010  5011.5  5020.6  5030.6  5040.6  5050.6
  5060.6  5070.6  5077.7  5117.7  5137.7  5157.7  5187.7  5227.7  5247.7  5267.7
  5327.7  5367.7  5377.7  5479.7  5597.7  5637.7  5647.7  5687.7  5728.6  5729.7
   15.01    14.9   14.77   14.76   14.71   14.58   14.52   14.48   14.41   14.28
   14.21   14.08   14.02   13.95   13.82    13.6   13.53   13.45   13.39   13.41
   13.43   13.37   13.27   13.06   12.96   12.75   12.65   12.54   12.47   12.46
    12.2    12.2    12.2    12.2    12.2    12.2    12.2    12.2    12.2    12.2
    12.2    12.2    12.2    12.2    12.2    12.2    12.2    12.2    12.2    12.2
    12.2   12.29   12.59   12.79   12.83   12.84   12.85   13.12   13.05   13.15
   15.01    12.8   12.39   12.72   12.99   12.34   11.65   11.08   10.06    9.33
    9.49   10.45   10.72   10.57    9.54    8.53    8.66    7.22    6.92    7.15
    5.54    5.56    6.06    6.68    6.78    5.98     6.5    5.92    5.87    5.73
    5.65    5.24    0.73   -2.27   -2.27    0.73       8    9.98   10.77   11.23
    9.15    6.72    6.42    6.53    6.16    6.75    8.68   10.44   10.61   11.26
   12.08   12.29   12.59   12.75   12.58    12.8   12.62   13.12   12.99   13.15
  4477.4  4480.6  4520.6  4530.6  4550.6  4590.6  4610.6  4620.6  4630.6  4650.6
  4660.6  4680.6  4690.6  4700.6  4720.6  4750.6  4760.6  4770.6  4780.6  4800.6
  4810.6  4820.6  4830.6  4850.6  4860.6  4880.6  4890.6  4920.6  4950.6  4955.1
  4957.7  4970.6  4988.5    4990    5010  5011.5  5020.6  5030.6  5040.6  5050.6
  5060.6  5070.6  5077.7  5117.7  5137.7  5157.7  5187.7  5227.7  5247.7  5267.7
  5327.7  5367.7  5377.7  5479.7  5597.7  5637.7  5647.7  5687.7  5728.6  5729.7
   14.92    14.9   14.77   14.76   14.71   14.58   14.52   14.48   14.41   14.28
   14.21   14.08   14.02   13.95   13.82    13.6   13.53   13.45   13.39   13.41
   13.43   13.37   13.27   13.06   12.96   12.75   12.65   12.54   12.47   12.46
    12.2    12.2    12.2    12.2    12.2    12.2    12.2    12.2    12.2    12.2
    12.2    12.2    12.2    12.2    12.2    12.2    12.2    12.2    12.2    12.2
    12.2    12.2   12.51   12.79   12.83   12.84   12.85   13.04   13.05   13.06
   14.82   12.61    12.2   12.53    12.8   12.15   11.46   10.89    9.87    9.14
     9.3   10.26   10.53   10.38    9.35    8.34    8.47    7.03    6.73    6.96
    5.35    5.37    5.87    6.49    6.59    5.79    6.31    5.73    5.68    5.54
    5.46    5.05    0.54   -2.46   -2.46    0.54    7.81    9.79   10.58   11.04
    8.96    6.53    6.23    6.34    5.97    6.56    8.49   10.25   10.42   11.07
   11.89    12.1    12.4   12.56   12.39   12.61   12.43   12.93    12.8   12.96
BR Coef= 1 , 0 , 0 ,1.25, 0 ,,,0.8,-1,2,0,
Wspro=,,,, 1 ,,,, 0 ,,,, 0 ,,,,-1 ,-1 ,-1 , 0 , 0 , 0 , 0 , 0
Culvert=2,5.0,6.0,37.5,0.015,0.4,1.0,8,1,-2.20,4993.02,-2.39,4993.02,Culvert #1  ,0,10
Culvert=2,5.0,6.0,37.5,0.015,0.4,1.0,8,1,-2.20,5000.02,-2.39,5000.02,Culvert #2  ,0,10
Culvert=2,5.0,6.0,37.5,0.015,0.4,1.0,8,1,-2.20,5007.02,-2.39,5007.02,Culvert #3  ,0,10
BC Design=,, 0 ,, 0 ,,,,,,
BR U #Sta/Elev= 78
  4477.4   15.01  4480.6    12.8  4497.4   12.63  4520.6   12.39  4530.6   12.72
  4537.4   12.81  4550.6   12.99  4590.6   12.34  4610.6   11.65  4617.4   11.26
  4619.1   11.17  4620.6   11.08  4630.6   10.06  4650.6    9.33  4660.6    9.49
  4680.6   10.45  4690.6   10.72  4700.6   10.57  4720.6    9.54  4729.1    9.25
  4750.6    8.53  4760.6    8.66  4770.6    7.22  4779.1    6.97  4780.6    6.92
  4800.6    7.15  4810.6    5.54  4815.1    5.55  4820.6    5.56  4830.6    6.06
  4850.6    6.68  4860.6    6.78  4880.6    5.98  4890.6     6.5  4895.1    6.41
  4920.6    5.92  4950.6    5.87  4955.1    5.73  4957.7    5.65  4970.6    5.24
  4988.5    0.73    4990   -2.27    5000   -2.27    5010   -2.27  5011.5    0.73
  5020.6       8  5030.6    9.98  5040.6   10.77  5050.6   11.23  5060.6    9.15
  5070.6    6.72  5077.7    6.42  5117.7    6.53  5137.7    6.16  5157.7    6.75
  5187.7    8.68  5227.7   10.44  5247.7   10.61  5267.7   11.26  5327.7   12.08
  5337.7   12.07  5357.7   12.33  5367.7   12.29  5377.7   12.59  5384.9    12.6
  5389.7   12.61  5399.7   12.63  5409.7   12.64  5449.7   12.71  5477.7   12.75
  5479.7   12.75  5597.7   12.58  5637.7    12.8  5647.7   12.62  5687.7   13.12
  5709.7   13.05  5728.6   12.99  5729.7   13.15
BR U #Mann= 3
 4477.40    0.14  4988.5   0.045  5011.5    0.14
BR U Banks=4988.50,5011.50
BR D #Sta/Elev= 78
  4477.4   14.82  4480.6   12.61  4497.4   12.44  4520.6    12.2  4530.6   12.53
  4537.4   12.62  4550.6    12.8  4590.6   12.15  4610.6   11.46  4617.4   11.07
  4619.1   10.98  4620.6   10.89  4630.6    9.87  4650.6    9.14  4660.6     9.3
  4680.6   10.26  4690.6   10.53  4700.6   10.38  4720.6    9.35  4729.1    9.06
  4750.6    8.34  4760.6    8.47  4770.6    7.03  4779.1    6.78  4780.6    6.73
  4800.6    6.96  4810.6    5.35  4815.1    5.36  4820.6    5.37  4830.6    5.87
  4850.6    6.49  4860.6    6.59  4880.6    5.79  4890.6    6.31  4895.1    6.22
  4920.6    5.73  4950.6    5.68  4955.1    5.54  4957.7    5.46  4970.6    5.05
  4988.5    0.54    4990   -2.46    5000   -2.46    5010   -2.46  5011.5    0.54
  5020.6    7.81  5030.6    9.79  5040.6   10.58  5050.6   11.04  5060.6    8.96
  5070.6    6.53  5077.7    6.23  5117.7    6.34  5137.7    5.97  5157.7    6.56
  5187.7    8.49  5227.7   10.25  5247.7   10.42  5267.7   11.07  5327.7   11.89
  5337.7   11.88  5357.7   12.14  5367.7    12.1  5377.7    12.4  5384.9   12.41
  5389.7   12.42  5399.7   12.44  5409.7   12.45  5449.7   12.52  5477.7   12.56
  5479.7   12.56  5597.7   12.39  5637.7   12.61  5647.7   12.43  5687.7   12.93
  5709.7   12.86  5728.6    12.8  5729.7   12.96
BR D #Mann= 3
 4477.40    0.14  4988.5   0.045  5011.5    0.14
BR D Banks=4988.50,5011.50

Type RM Length L Ch R = 1 ,15237.4,256.05,256.05,256.05
XS GIS Cut Line= 6
 2728437.2282012 863624.06151430 2728510.1326839 863502.55404314
 2728552.6602988 863311.17977608 2728592.1502269 862895.01668737
 2728528.3588046 862752.24540877 2728593.3281870 862418.53903542
BEGIN DESCRIPTION:
Downstream Section of Bridge/Culvert/Weir
END DESCRIPTION:
#Sta/Elev= 30
  4477.4   14.83  4480.6   12.62  4520.6   12.21  4550.6   12.81  4590.6   12.16
  4650.6    9.15  4690.6   10.54  4700.6   10.39  4750.6    8.35  4760.6    8.48
  4770.6    7.04  4800.6    6.97  4810.6    5.36  4860.6     6.6  4880.6     5.8
  4890.6    6.32  4950.6    5.69  4970.6    5.06  4988.5    0.55    4990   -2.45
    5010   -2.45  5011.5    0.55  5020.6    7.82  5030.6     9.8  5050.6   11.05
  5070.6    6.54  5137.7    5.98  5227.7   10.26  5327.7    11.9  5729.7   12.97
#Mann= 3 , 1 , 0
 4477.40    0.14       0  4988.5   0.045       0  5011.5    0.14       0
#XS Ineff= 2 , 0
       0 4981.83     8.5 5018.17       0     8.5
Bank Sta=4988.50,5011.50
Exp/Cntr=0.5,0.3

Type RM Length L Ch R = 1 ,14981.3,453.9,453.9,453.9
XS GIS Cut Line= 4
 2729016.7457286  863436.5543187 2728799.9807270 863075.27931589
 2728737.1502917 862971.60909769 2728799.9807270 862446.97496318
BEGIN DESCRIPTION:
Burnt Mill Creek 29.5
END DESCRIPTION:
#Sta/Elev= 30
  4604.3   11.11  4634.3   11.36  4654.3   10.57  4704.3   10.72  4734.3   10.35
  4744.3    9.61  4794.3    9.63  4894.3    7.08  4924.3    7.74  4944.3     5.7
  4984.3    5.45  4993.8    0.71  4995.3   -2.29  5004.8   -2.29  5006.3    0.71
  5014.3    7.07  5024.3     9.4  5045.6   11.04  5055.6    9.66  5065.6    6.97
  5075.6     5.5  5085.6    6.33  5156.8    6.26  5266.8    9.16  5296.8    8.63
  5346.8    9.71  5386.8    8.64  5436.8   11.17  5576.8   12.33  5675.2    12.3
#Mann= 3 , 1 , 0
 4604.30    0.14       0  4993.8   0.045       0  5006.3    0.14       0
Bank Sta=4993.80,5006.30
Exp/Cntr=0.3,0.1

Type RM Length L Ch R = 1 ,14527.4,491.4,491.4,491.4
XS GIS Cut Line= 3
 2729326.8609736  863408.0891139 2729232.8341422 862917.51434137
 2729093.8379567 862402.41083021
BEGIN DESCRIPTION:
Burnt Mill Creek 29.0
END DESCRIPTION:
#Sta/Elev= 30
  4566.2   12.43  4596.2   11.67  4626.2   12.16  4666.2   11.82  4786.2    9.46
  4846.2    7.15  4876.2     7.3  4916.2    5.02  4946.2    4.47  4966.2    6.06
  4986.2    4.47  4993.7    0.66  4995.2   -2.34  5004.7   -2.34  5006.1    0.66
  5026.2    8.65  5046.2    8.74  5056.2    8.16  5065.7    6.55  5085.7    4.92
  5125.7    5.69  5215.7    4.86  5235.7    5.78  5315.7    6.81  5345.7    8.88
  5365.7    8.52  5405.7    9.99  5425.7    9.68  5465.7   12.35  5599.2   12.64
#Mann= 3 , 1 , 0
 4566.20    0.14       0  4993.7   0.045       0  5006.1    0.14       0
Bank Sta=4993.70,5006.10
Exp/Cntr=0.3,0.1

Type RM Length L Ch R = 1 ,14036.0,494.4,494.4,494.4
XS GIS Cut Line= 3
         2729675          863325 2729732.3307324 862870.27941626
         2729675          862425
BEGIN DESCRIPTION:
Burnt Mill Creek 28.0
END DESCRIPTION:
#Sta/Elev= 30
  4567.8   11.19  4597.8   11.03  4617.8   10.11  4647.8    9.69  4727.8     6.9
  4767.8    6.77  4857.8    5.06  4907.8    5.18  4947.8    3.22  4957.8    3.84
  4967.8    3.37  4993.8    0.29  4995.3   -2.71  5004.8   -2.71  5006.3    0.29
  5007.8   -0.09  5017.8    5.24  5036.1    7.73  5046.1    8.22  5056.1    7.66
  5076.1    5.12  5086.1    4.71  5126.1    4.86  5176.1    5.91  5186.1    6.96
  5226.1    8.85  5256.1     8.3  5336.1    8.48  5426.1   11.67  5475.1   11.62
#Mann= 3 , 1 , 0
 4567.80    0.14       0  4993.8   0.045       0  5006.3    0.14       0
Bank Sta=4993.80,5006.30
Exp/Cntr=0.3,0.1

Type RM Length L Ch R = 1 ,13541.6,501.4,501.4,501.4
XS GIS Cut Line= 3
 2730112.8789114 863323.21479691 2730242.8446161 862751.36569639
 2730346.8171798 861971.57146841
BEGIN DESCRIPTION:
Burnt Mill Creek 27.0
END DESCRIPTION:
#Sta/Elev= 30
  4538.4   11.36  4578.4   11.15  4658.4    9.41  4768.4     4.4  4798.4    4.41
  4838.4    2.52  4888.4    3.45  4908.4    2.67  4968.4    4.53  4988.4    4.59
  4993.7   -0.25  4995.2   -3.25  5004.7   -3.25  5006.2   -0.25  5008.4    4.04
  5018.4    4.36  5048.4    7.71  5058.4    7.94  5068.4    5.46  5078.4    4.72
  5088.4    4.72  5144.8    7.57  5274.8   10.64  5284.8   10.36  5324.8   11.18
  5444.8   11.14  5524.8   11.86  5584.8   11.54  5734.8   12.28  5911.5   12.14
#Mann= 3 , 1 , 0
 4538.40    0.14       0  4993.7   0.045       0  5006.2    0.14       0
Bank Sta=4993.70,5006.20
Exp/Cntr=0.3,0.1