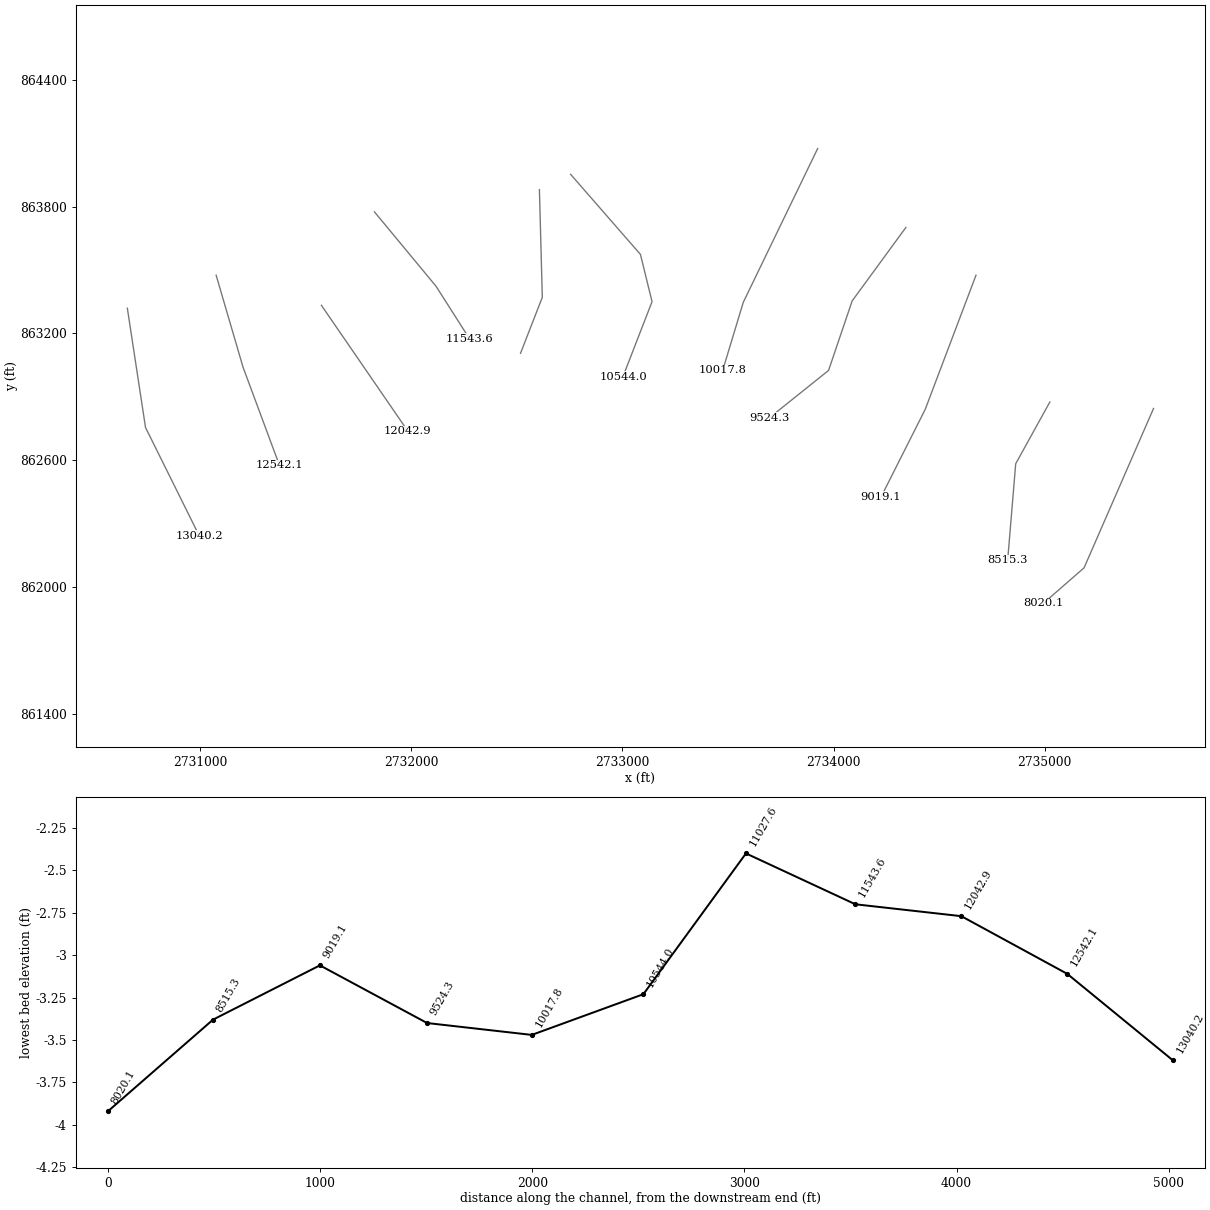
HEC-RAS study BURNT MILL CREEK.PRJ: Burnt Mill Creek

--- BURNT MILL CREEK.g01 (geometry) --- (continued)

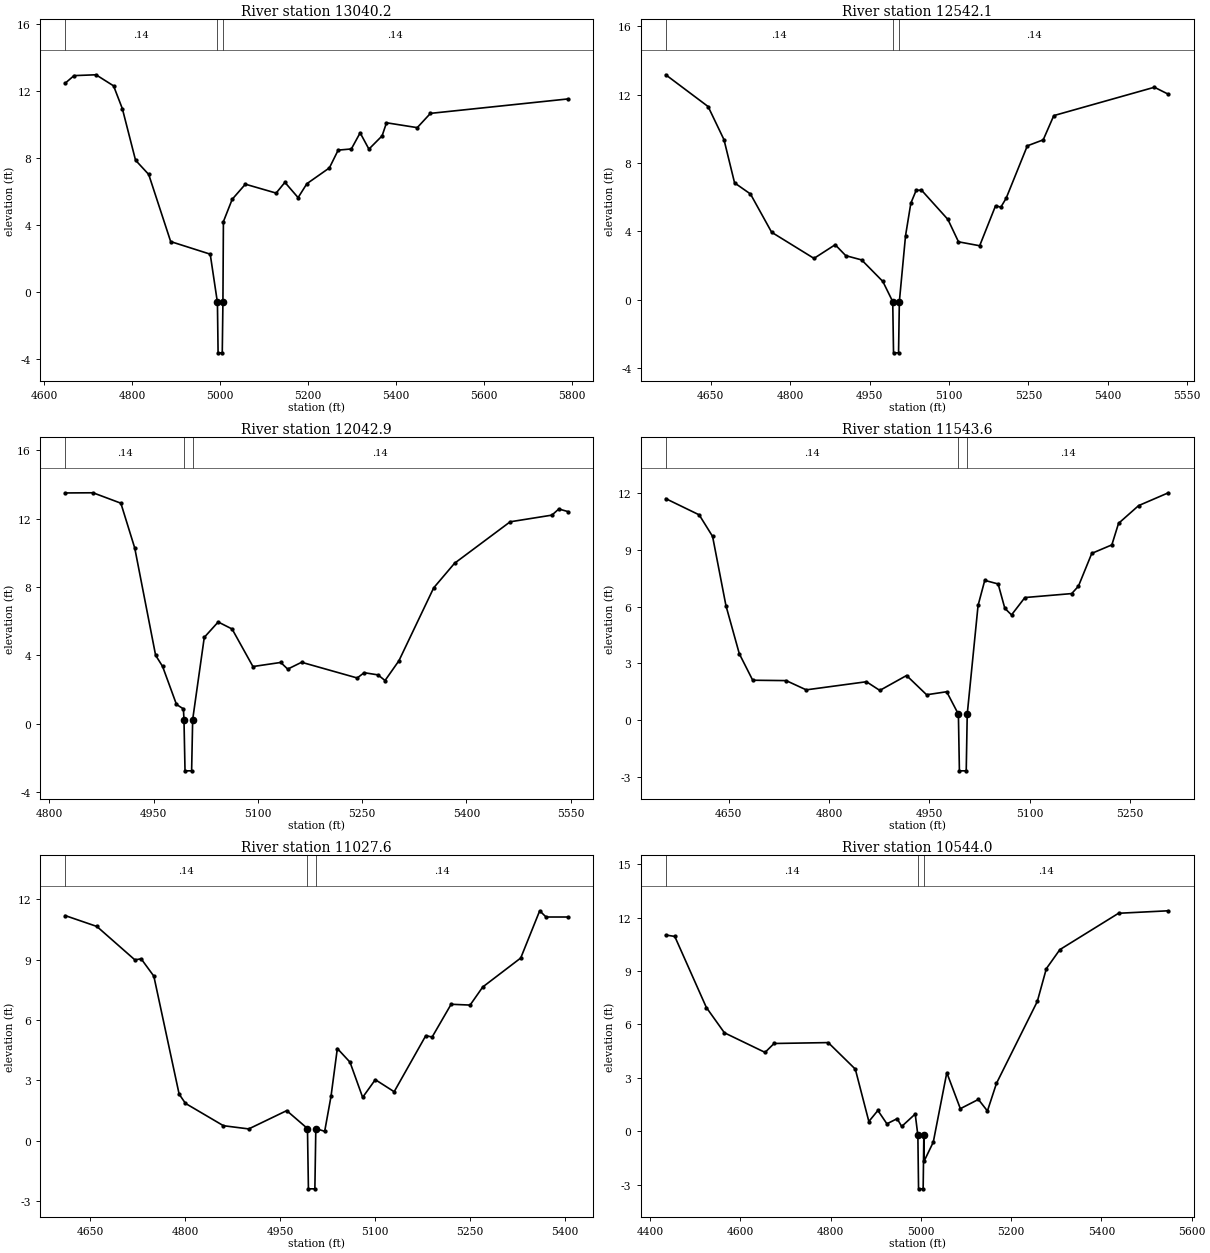
Type RM Length L Ch R = 1 ,13040.2,498.1,498.1,498.1
XS GIS Cut Line= 3
 2730654.2976091 863318.94726631 2730740.3756411 862754.27537635
 2730995.1666158 862241.25030559
BEGIN DESCRIPTION:
Burnt Mill Creek 26.0
END DESCRIPTION:
#Sta/Elev= 30
  4647.4   12.45  4667.4    12.9  4717.4   12.95  4757.4   12.29  4777.4   10.93
  4807.4    7.86  4837.4    7.01  4887.4    3.01  4977.4    2.26  4993.8   -0.62
  4995.3   -3.62  5004.8   -3.62  5006.3   -0.62  5007.4     4.2  5027.4    5.53
  5057.4    6.43  5127.4     5.9  5147.4    6.54  5177.4    5.63  5197.4    6.46
  5248.6     7.4  5268.6    8.46  5298.6    8.53  5318.6    9.49  5338.6    8.52
  5368.6    9.31  5378.6   10.09  5448.6     9.8  5478.6   10.65  5791.4   11.51
#Mann= 3 , 1 , 0
 4647.40    0.14       0  4993.8   0.045       0  5006.3    0.14       0
Bank Sta=4993.80,5006.30
Exp/Cntr=0.3,0.1

Type RM Length L Ch R = 1 ,12542.1,499.2,499.2,499.2
XS GIS Cut Line= 3
         2731075          863475 2731202.1868116 863040.36040242
         2731375          862575
BEGIN DESCRIPTION:
Burnt Mill Creek 25.0
END DESCRIPTION:
#Sta/Elev= 30
  4565.1   13.17  4645.1   11.31  4675.1    9.37  4695.1    6.84  4725.1    6.19
  4765.1    3.95  4845.1    2.42  4885.1    3.22  4905.1    2.58  4935.1    2.33
  4975.1    1.07  4993.8   -0.11  4995.3   -3.11  5004.8   -3.11  5006.3   -0.11
    5018    3.75    5028    5.65    5038     6.4    5048    6.42    5098     4.7
    5118    3.39    5158    3.16    5188     5.5    5198    5.42    5208    5.94
    5248    9.01    5278    9.36    5298   10.78    5488   12.44  5514.4   12.03
#Mann= 3 , 1 , 0
 4565.10    0.14       0  4993.8   0.045       0  5006.3    0.14       0
Bank Sta=4993.80,5006.30
Exp/Cntr=0.3,0.1

Type RM Length L Ch R = 1 ,12042.9,499.3,499.3,499.3
XS GIS Cut Line= 2
 2731573.6109909 863332.71975143 2731983.3424233 862737.05976995
BEGIN DESCRIPTION:
Burnt Mill Creek 24.0
END DESCRIPTION:
#Sta/Elev= 30
  4822.9   13.51  4862.9   13.52  4902.9   12.91  4922.9   10.28  4952.9       4
  4962.9    3.35  4982.9    1.12  4992.9    0.86  4993.7    0.23  4995.2   -2.77
  5004.7   -2.77  5006.2    0.23  5022.9    5.05  5042.9    5.95  5062.9    5.54
  5092.9    3.34  5132.9    3.58  5142.9    3.19  5162.9    3.59  5242.9    2.67
  5252.9    2.98  5272.9    2.85  5282.9    2.52  5302.9    3.68  5352.9    7.95
  5382.9    9.39  5462.9   11.82  5522.9   12.21  5532.9   12.57  5545.9   12.42
#Mann= 3 , 1 , 0
 4822.90    0.14       0  4993.7   0.045       0  5006.2    0.14       0
Bank Sta=4993.70,5006.20
Exp/Cntr=0.3,0.1

Type RM Length L Ch R = 1 ,11543.6,516,516,516
XS GIS Cut Line= 3
         2731825          863775 2732116.4926194 863423.21809474
         2732275          863175
BEGIN DESCRIPTION:
Burnt Mill Creek 23.0
END DESCRIPTION:
#Sta/Elev= 30
  4555.9   11.72  4605.9   10.86  4625.9    9.72  4645.9    6.05  4665.9     3.5
  4685.9     2.1  4735.9    2.08  4765.9    1.59  4855.9    2.02  4875.9    1.56
  4915.9    2.35  4945.9    1.33  4975.9    1.49  4993.4     0.3  4994.9    -2.7
  5005.1    -2.7  5006.6     0.3  5022.8    6.06  5032.8    7.39  5052.8     7.2
  5062.8    5.91  5072.8    5.56  5092.8    6.48  5162.8    6.69  5172.8    7.08
  5192.8    8.82  5222.8    9.27  5232.8   10.41  5262.8   11.35  5307.3   12.03
#Mann= 3 , 1 , 0
 4555.90    0.14       0  4993.4   0.045       0  5006.6    0.14       0
Bank Sta=4993.40,5006.60
Exp/Cntr=0.3,0.1

Type RM Length L Ch R = 1 ,11027.6,483.6,483.6,483.6
XS GIS Cut Line= 3
 2732606.5473750   863880.176035 2732620.3198601 863370.59408552
 2732517.0262217 863105.47374694
BEGIN DESCRIPTION:
Burnt Mill Creek 22.0
END DESCRIPTION:
#Sta/Elev= 30
  4610.6   11.19  4660.6   10.65  4720.6    8.99  4730.6    9.04  4750.6    8.18
  4790.6    2.31  4800.6    1.85  4860.6    0.74  4900.6    0.58  4960.6    1.49
  4993.4     0.6  4994.9    -2.4  5005.1    -2.4  5006.6     0.6  5020.6    0.46
  5030.6     2.2  5040.6    4.58  5060.6     3.9  5080.6    2.15  5100.6    3.03
  5130.4    2.43  5180.4    5.22  5190.4    5.15  5220.4    6.78  5250.4    6.74
  5270.4    7.64  5330.4    9.08  5360.4   11.43  5370.4   11.12  5404.9   11.12
#Mann= 3 , 1 , 0
 4610.60    0.14       0  4993.4   0.045       0  5006.6    0.14       0
Bank Sta=4993.40,5006.60
Exp/Cntr=0.3,0.1

Type RM Length L Ch R = 1 ,10544.0,526.2,526.2,526.2
XS GIS Cut Line= 4
 2732754.6015900 863952.48158188 2733085.1412329 863573.73824105
 2733140.2311734 863349.93535784 2733002.5063222 862995.29386597
BEGIN DESCRIPTION:
Burnt Mill Creek 21.0
END DESCRIPTION:
#Sta/Elev= 30
  4434.8   11.02  4454.8   10.94  4524.8    6.95  4564.8    5.53  4654.8    4.43
  4674.8    4.93  4794.8    4.98  4854.8    3.49  4884.8    0.55  4904.8    1.17
  4924.8    0.42  4947.5    0.71  4957.5    0.27  4987.5    0.97  4993.4   -0.23
  4994.9   -3.23  5005.1   -3.23  5006.6   -0.23  5007.5   -1.66  5027.5   -0.61
  5057.5    3.29  5087.5    1.27  5127.5    1.79  5147.5    1.14  5167.5    2.69
    5258    7.29    5278    9.13    5308    10.2    5438   12.24  5548.4   12.38
#Mann= 3 , 1 , 0
 4434.80    0.14       0  4993.4   0.045       0  5006.6    0.14       0
Bank Sta=4993.40,5006.60
Exp/Cntr=0.3,0.1

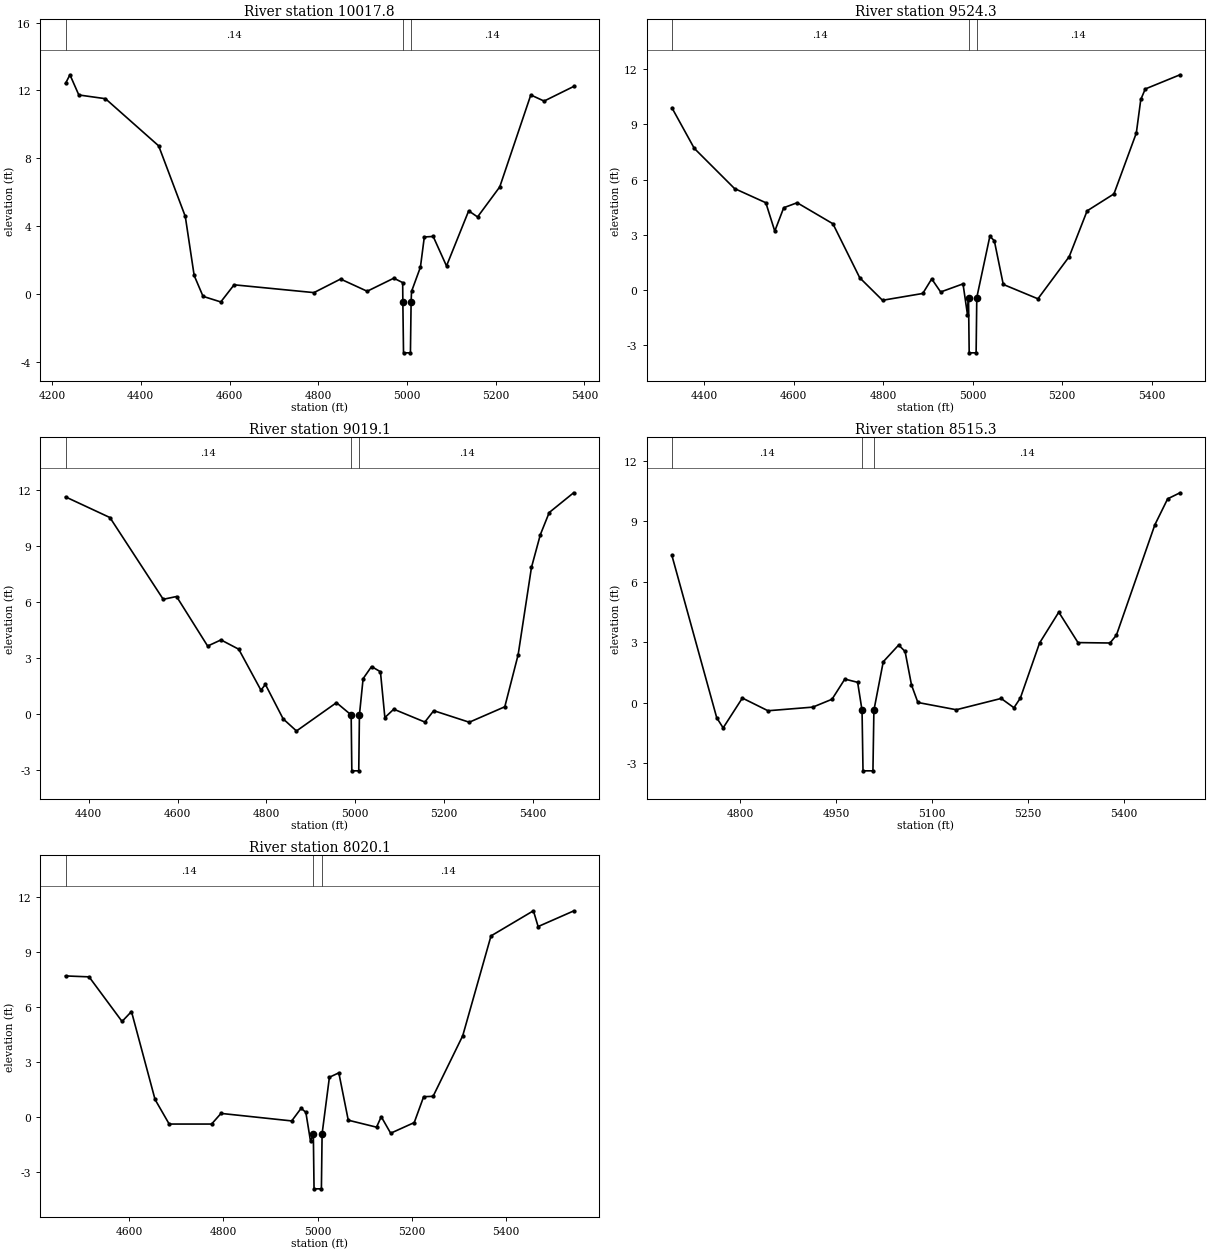
Type RM Length L Ch R = 1 ,10017.8,493.5,493.5,493.5
XS GIS Cut Line= 3
         2733925          864075 2733572.5440904 863347.04336054
         2733475          863025
BEGIN DESCRIPTION:
Burnt Mill Creek 20.0
END DESCRIPTION:
#Sta/Elev= 30
  4230.3   12.41  4240.3   12.92  4260.3   11.73  4320.3   11.51  4440.3    8.73
  4500.3    4.57  4520.3    1.09  4540.3   -0.14  4580.3   -0.47  4610.3    0.54
  4790.3    0.08  4850.3    0.88  4910.3    0.16  4970.3    0.93  4990.3    0.67
  4990.7   -0.47  4992.2   -3.47  5007.8   -3.47  5009.3   -0.47  5010.3    0.15
  5030.3    1.58  5039.1    3.36  5059.1    3.39  5089.1    1.65  5139.1     4.9
  5159.1    4.54  5209.1    6.31  5279.1   11.73  5309.1   11.37  5375.6   12.23
#Mann= 3 , 1 , 0
 4230.30    0.14       0  4990.7   0.045       0  5009.3    0.14       0
Bank Sta=4990.70,5009.30
Exp/Cntr=0.3,0.1

Type RM Length L Ch R = 1 ,9524.3,505.2,505.2,505.2
XS GIS Cut Line= 4
 2734342.8020140 863701.06311672 2734088.2632674 863353.40043844
 2733976.5145494 863024.36254649 2733697.1427544 862800.86511046
BEGIN DESCRIPTION:
Burnt Mill Creek 19.0
END DESCRIPTION:
#Sta/Elev= 30
  4327.6    9.89  4377.6    7.69  4467.6    5.51  4537.6    4.74  4557.6     3.2
  4577.6    4.47  4607.6    4.74  4687.6     3.6  4747.6    0.67  4798.5   -0.55
  4888.5   -0.18  4908.5    0.61  4928.5    -0.1  4978.5    0.34  4988.5   -1.33
  4990.8    -0.4  4992.3    -3.4  5007.8    -3.4  5009.3    -0.4  5038.5    2.92
  5048.5    2.68  5068.5    0.31    5146   -0.47    5216    1.82    5256     4.3
    5316    5.22    5366    8.52    5376   10.34    5386   10.91  5463.7   11.68
#Mann= 3 , 1 , 0
 4327.60    0.14       0  4990.8   0.045       0  5009.3    0.14       0
Bank Sta=4990.80,5009.30
Exp/Cntr=0.3,0.1

Type RM Length L Ch R = 1 ,9019.1,503.8,503.8,503.8
XS GIS Cut Line= 3
         2734675          863475 2734434.4371948 862839.99825451
         2734225          862425
BEGIN DESCRIPTION:
Burnt Mill Creek 18.0
END DESCRIPTION:
#Sta/Elev= 30
  4347.6   11.65  4447.6   10.54  4567.6    6.15  4597.6     6.3  4667.6    3.64
  4697.6    3.97  4737.6    3.47  4787.6    1.27  4797.6    1.58  4837.6   -0.27
  4867.6   -0.92  4957.6     0.6  4990.7   -0.06  4992.2   -3.06  5007.8   -3.06
  5009.3   -0.06  5017.6    1.89  5036.6    2.54  5056.6    2.26  5066.6    -0.2
  5086.6    0.25  5156.6   -0.44  5176.6    0.17  5256.6   -0.45  5336.6    0.38
  5366.6    3.17  5396.6    7.86  5416.6    9.62  5436.6   10.81  5491.5   11.87
#Mann= 3 , 1 , 0
 4347.60    0.14       0  4990.7   0.045       0  5009.3    0.14       0
Bank Sta=4990.70,5009.30
Exp/Cntr=0.3,0.1

Type RM Length L Ch R = 1 ,8515.3,495.2,495.2,495.2
XS GIS Cut Line= 3
         2735025          862875 2734863.1836576 862582.75037679
         2734825          862125
BEGIN DESCRIPTION:
Burnt Mill Creek 17.0
END DESCRIPTION:
#Sta/Elev= 30
  4693.8     7.3  4763.8   -0.75  4773.8   -1.25  4803.8    0.23  4843.8    -0.4
  4913.8   -0.22  4943.8    0.17  4963.8    1.17  4983.8    1.01  4990.7   -0.38
  4992.2   -3.38  5007.7   -3.38  5009.2   -0.38  5023.8    2.03  5047.9    2.86
  5057.9    2.54  5067.9    0.88  5077.9    0.01  5137.9   -0.35  5207.9    0.21
  5227.9   -0.25  5237.9    0.23  5267.9    2.96  5297.9    4.49  5327.9    2.98
  5377.9    2.96  5387.9    3.35  5447.9    8.82  5467.9   10.11  5487.2   10.41
#Mann= 3 , 1 , 0
 4693.80    0.14       0  4990.7   0.045       0  5009.2    0.14       0
Bank Sta=4990.70,5009.20
Exp/Cntr=0.3,0.1

Type RM Length L Ch R = 1 ,8020.1,0,0,0
XS GIS Cut Line= 3
 2735516.1635532 862844.32294524 2735187.1256613 862090.01909861
 2734994.6695358 861922.39602158
BEGIN DESCRIPTION:
Burnt Mill Creek 16.0
END DESCRIPTION:
#Sta/Elev= 30
  4464.8    7.68  4514.8    7.63  4584.8     5.2  4604.8    5.74  4654.8    0.95
  4684.8   -0.39  4774.8   -0.39  4794.8    0.19  4944.8   -0.22  4964.8    0.47
  4974.8    0.25  4984.8   -1.34  4990.7   -0.92  4992.2   -3.92  5007.8   -3.92
  5009.3   -0.92  5024.8    2.16  5044.8     2.4  5064.8   -0.18  5124.8   -0.56
  5134.8    0.01  5154.8   -0.89  5204.8   -0.31  5224.8     1.1  5244.8    1.12
  5307.7    4.42  5367.7    9.86  5457.7   11.23  5467.7   10.37    5543   11.22
#Mann= 3 , 1 , 0
 4464.80    0.14       0  4990.7   0.045       0  5009.3    0.14       0
Bank Sta=4990.70,5009.30
Exp/Cntr=0.3,0.1

Chan Stop Cuts=-1