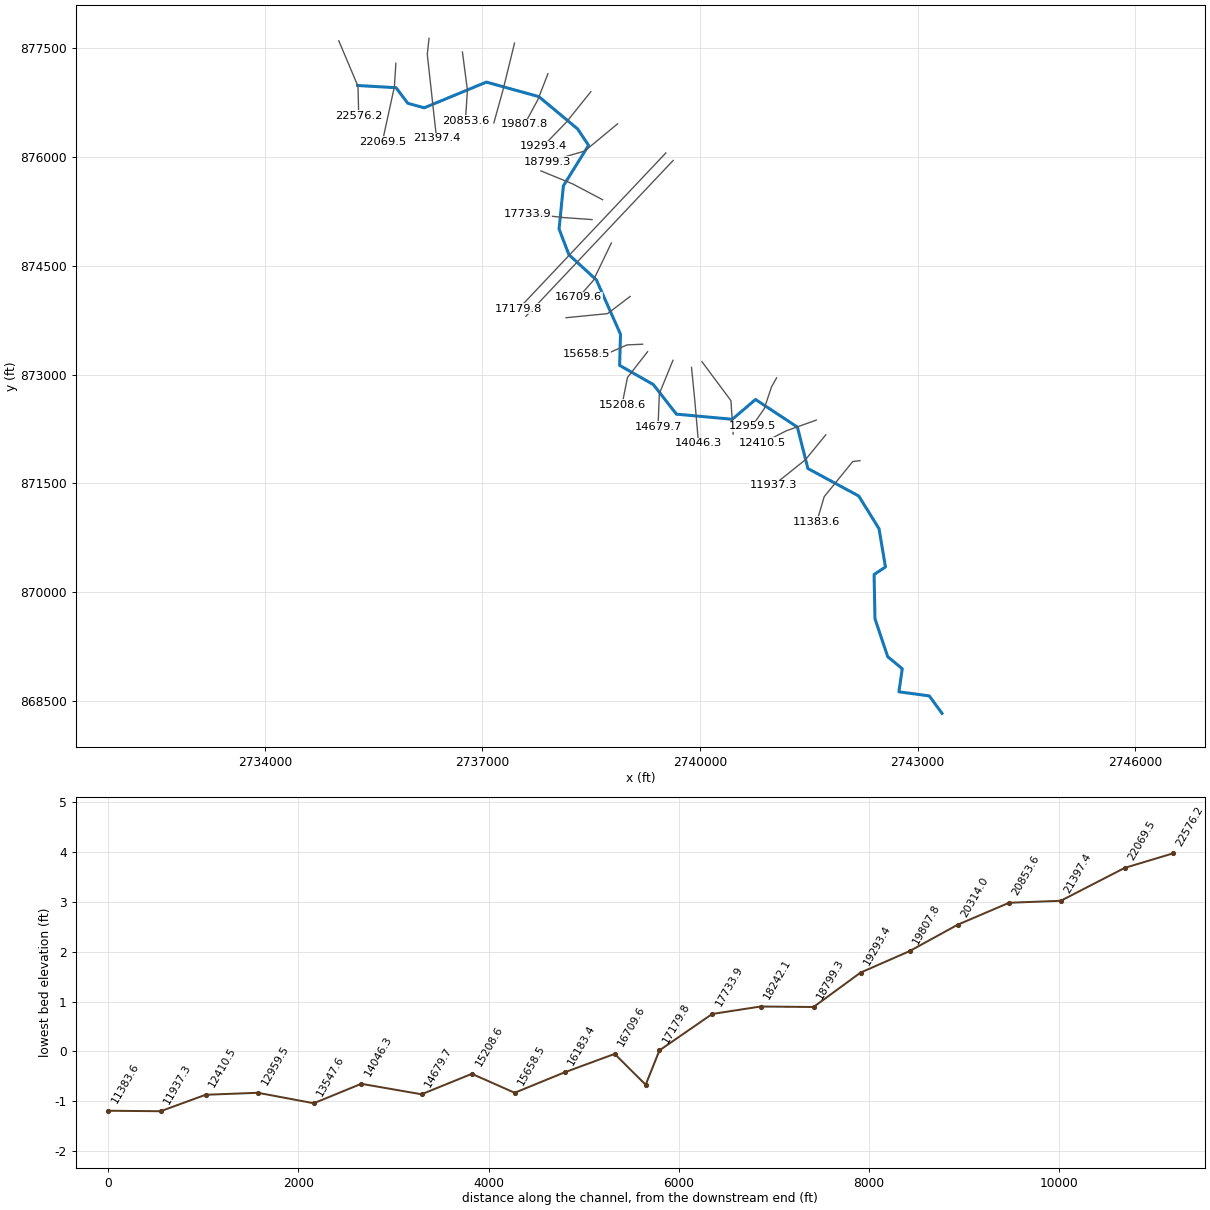
--- BETHEL CREEK.PRJ (project) ---

Proj Title=Bethel Creek
Current Plan=p01
Default Exp/Contr=.3,.1
English Units
Geom File=g01
Flow File=f01
Plan File=p01
Y Axis Title=Elevation
X Axis Title(PF)=Main Channel Distance
X Axis Title(XS)=Station
BEGIN DESCRIPTION:
####(Watershed Name)####
BETHEL CREEK
HCFCD Unit X###-##-##
(Flood Hazard, Floodway) Model
10, 2, 1, 0.2% Event
Filename:  N:\NC_flood\60227\Baker\ENG\Yeopim Basin\Bethel Creek.prj
Prepared by:  ________     Date: ________
Reviewed by:  ________     Date: ________
STATUS (Draft RAS, SVSQ, FINAL)
END DESCRIPTION:
DSS Export Rating Curves= 0
DSS Export Rating Curve Sorted= 0
DSS Export Volume Flow Curves= 0
DXF OffsetX= 0
DXF OffsetY= 0
DXF ScaleX= 1
DXF ScaleY= 10

--- BETHEL CREEK.p01 (plan) ---

Plan Title=100 Year Single
Version=Version 3.0.1  Mar 2001
Short Identifier=Plan01
Geom File=g01
Flow File=f01
Subcritical Flow
K Sum by GR= 0
Std Step Tol= 0.01
Critical Tol= 0.01
Num of Std Step Trials= 20
Max Error Tol= 0.3
Flow Tol Ratio= 0.001
Split Flow NTrial= 30
Split Flow Tol= 0.02
Split Flow Ratio= 0.02
Log Output Level= 0
Friction Slope Method= 1
Unsteady Friction Slope Method= 2
Parabolic Critical Depth
Global Vel Dist= 0 , 0 , 0
Global Log Level= 0
CheckData=True
Encroach Param=-1 ,0,0, 2
Encroach River=Bethel Creek
Encroach Reach=Reach - 1
Encroach Node=22576.2
       1 4808.26 5160.95
Encroach Node=22069.5
       1 4891.61 5240.97
Encroach Node=21397.4
       1 4695.08 5036.45
Encroach Node=20853.6
       1 4792.07 5234.17
Encroach Node=20314.0
       1 4816.46 5205.31
Encroach Node=19807.8
       1 4835.55 5183.45
Encroach Node=19293.4
       1 4924.24 5307.59
Encroach Node=18799.3
       1 4868.14 5334.59
Encroach Node=18242.1
       1 4616.54  5031.5
Encroach Node=17733.9
       1 4702.53 5099.68
Encroach Node=17179.8
       1    4979    5021
Encroach Node=17107.5
       4     .75
Encroach Node=17035.3
       1    4979    5021
Encroach Node=16709.6
       1 4832.33 5167.05
Encroach Node=16183.4
       1 4903.47 5238.79
Encroach Node=15658.5
       1 4920.92 5243.44
Encroach Node=15208.6
       1 4927.21 5218.81
Encroach Node=14679.7
       1 4865.29 5222.29
Encroach Node=14046.3
       1 4816.07 5086.87
Encroach Node=13547.6
       1    4458    5051
Encroach Node=12959.5
       1 4881.12 5215.05
Encroach Node=12410.5
       1    4958 5300.93
Encroach Node=11937.3
       1 4828.07 5256.03
Encroach Node=11383.6
       1 4762.41 5202.06
Encroach Node=10874.3
       1 4916.87 5291.52
Encroach Node=10364.1
       1 4791.02 5084.67
Encroach Node=9727.1
       1    4885    5226
Encroach Node=9297.4
       1    4885    5226
Encroach Node=8876.8
       1    4827    5170
Encroach Node=8507.6
       1    4975    5025
Encroach Node=8484.9
       1    4975    5025
Encroach Node=8462.3
       1    4975   50225
Encroach Node=8191.9
       1    4960    5334
Encroach Node=7673.0
       1 4805.63 5026.35
Encroach Node=7168.8
       1    4810    5036
Computation Interval=1HOUR
Output Interval=1HOUR
Run HTab= 0
Run UNet= 0
Run PostProcess= 0
UNET Theta= 1
UNET ZTol= 0.02
UNET ZSATol= 0.1
UNET MxIter= 20
UNET MaxInSteps= 20
UNET DtIC= 0
UNET DtMin= 0
UNET MaxCRTS= 20
UNET WFStab= 2
UNET SFStab= 1
UNET WFX= 1
UNET SFX= 1
UNET Convert EG Bridges=-1
UNET Use Existing IB Tables=-1
Instantaneous Interval=1HOUR
Write IC File= 0
Write Velocity= 0
Write Detailed= 0

--- bethel creek.f01 (steady flow) ---

Flow Title= 100 Year Single
Version=Version 3.0.1  Mar 2001
Number of Profiles= 2
Profile Names=100-Year,Floodway
River Rch & RM=Bethel Creek,Reach - 1       ,22576.2
    1301    1301
River Rch & RM=Bethel Creek,Reach - 1       ,18242.1
    1417    1417
River Rch & RM=Bethel Creek,Reach - 1       ,15208.6
    1527    1527
River Rch & RM=Bethel Creek,Reach - 1       ,11383.6
    1630    1630
River Rch & RM=Bethel Creek,Reach - 1       ,7168.8
    1721    1721
Boundary for River Rch & Prof#=Bethel Creek,Reach - 1       , 1
Up Type= 0
Dn Type= 3
Dn Slope=.0013
Boundary for River Rch & Prof#=Bethel Creek,Reach - 1       , 2
Up Type= 0
Dn Type= 1
Dn Known WS=4.07
DSS Import GetInterval= 0
DSS Import GetPeak= 0
DSS Import FillOption= 0

--- BETHEL CREEK.g01 (geometry) ---

Geom Title=Geom 01 by CodeH2 for Windows

River Reach=Bethel Creek,Reach - 1
Reach XY= 30
 2735278.5389669 876984.37723488      2735807.16        876954.1
      2735970.16       876739.36      2736195.75       876676.54
       2737053.1        877031.2      2737777.85       876830.74
      2738311.78       876385.48      2738462.37        876159.6
      2738116.02       875602.43      2738055.79       875007.61
      2738191.71       874652.31      2738570.44       874304.93
      2738903.51       873555.52      2738891.17       873126.84
      2739356.86       872861.61      2739674.51       872454.52
      2740445.52       872383.59      2740765.56       872656.61
      2741342.97       872275.65      2741487.91       871705.11
      2742189.39       871325.77      2742468.63       870875.51
      2742558.07       870348.14      2742400.78       870243.28
      2742413.12       869632.65      2742588.91       869111.45
      2742789.37       868944.92      2742743.11       868627.26
      2743161.75       868570.44 2743337.9072839 868329.76030518

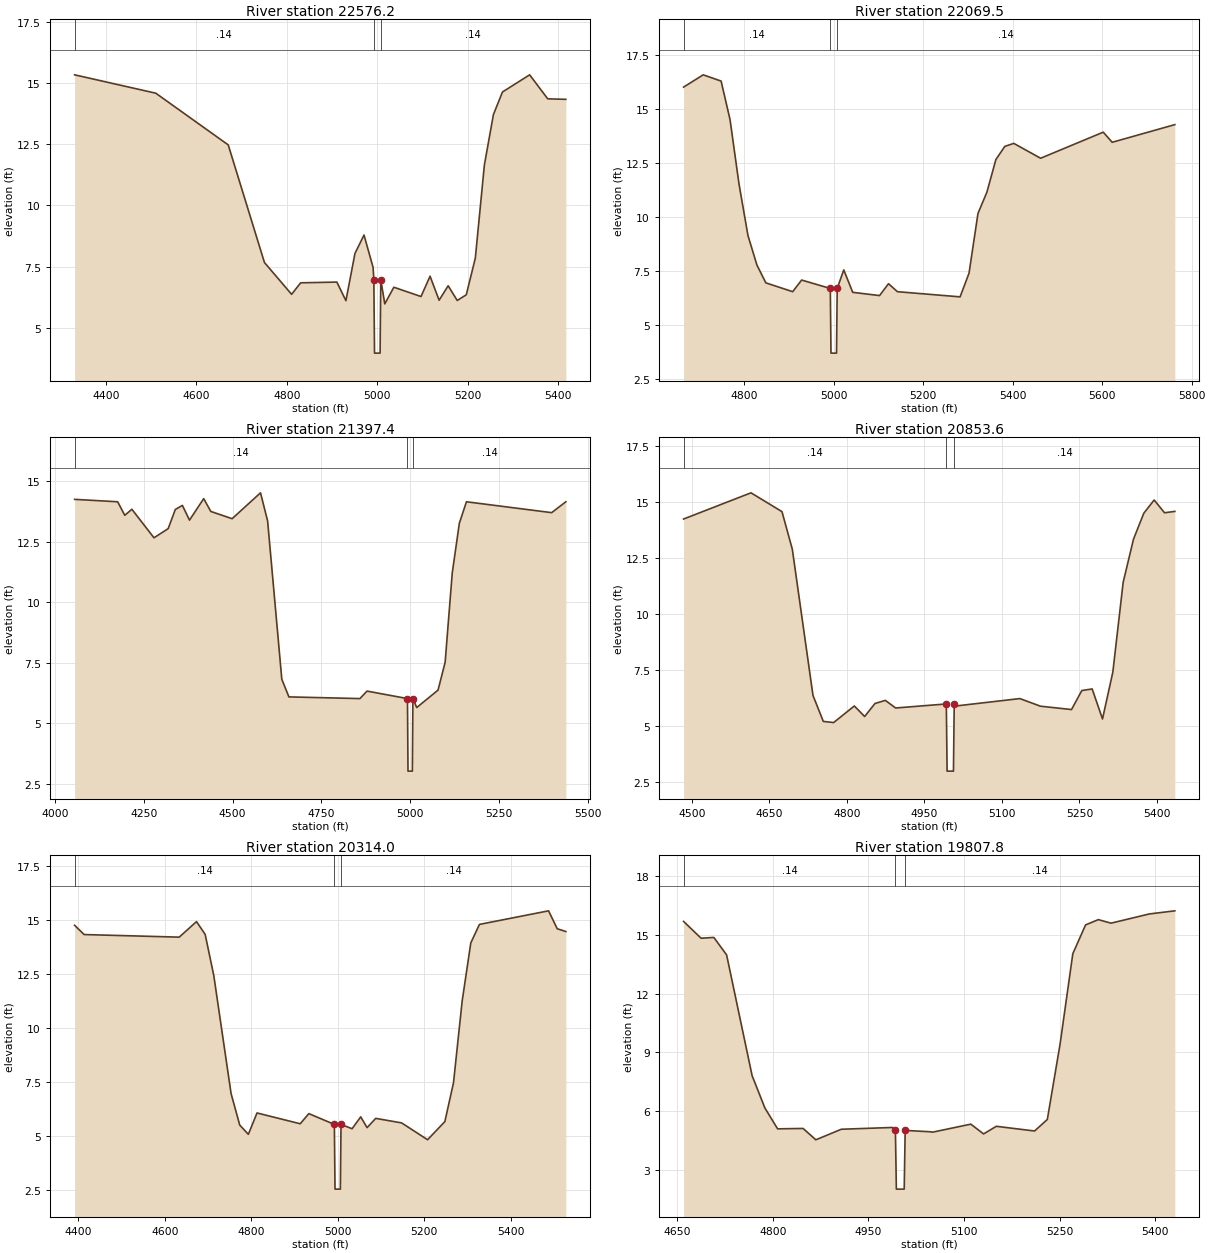
Type RM Length L Ch R = 1 ,22576.2,506.7,506.7,506.7
XS GIS Cut Line= 3
 2735017.9557208 877600.21370299 2735282.7045806 876974.44367072
 2735293.0194712  876568.7246388
BEGIN DESCRIPTION:
BETHEL CREEK 29.0
END DESCRIPTION:
#Sta/Elev= 30
  4331.3   15.33  4510.7   14.58  4670.7   12.47  4750.7    7.67  4810.7    6.37
  4830.7    6.84  4910.7    6.87  4930.7    6.11  4950.7    8.04  4970.7    8.79
  4990.7    7.47  4992.4    6.97  4993.9    3.97  5006.2    3.97  5007.7    6.97
  5016.6    5.98  5036.6    6.66  5096.6    6.28  5116.6    7.11  5136.6    6.13
  5156.6    6.72  5176.6    6.12  5196.6    6.35  5216.6    7.85  5236.6   11.65
  5256.6   13.71  5276.6   14.63  5336.6   15.33  5376.6   14.35  5416.6   14.33
#Mann= 3 , 1 , 0
 4331.30    0.14       0  4992.4   0.045       0  5007.7    0.14       0
Bank Sta=4992.40,5007.70
Exp/Cntr=0.3,0.1

Type RM Length L Ch R = 1 ,22069.5,672.1,672.1,672.1
XS GIS Cut Line= 3
 2735805.3257065 877290.76698374 2735784.6959252 876967.56707696
 2735619.6576749 876211.14176321
BEGIN DESCRIPTION:
BETHEL CREEK 28.0
END DESCRIPTION:
#Sta/Elev= 30
  4664.3   16.02  4708.2   16.59  4748.2    16.3  4768.2   14.51  4788.2   11.53
  4808.2    9.14  4828.2    7.77  4848.2    6.94  4908.2    6.53  4928.2    7.07
  4992.3    6.68  4993.8    3.68  5006.2    3.68  5007.7    6.68  5022.4    7.54
  5042.4     6.5  5102.4    6.35  5122.4     6.9  5142.4    6.53  5282.4    6.29
  5302.4    7.39  5322.4   10.16  5342.4   11.15  5362.4   12.66  5382.4   13.27
  5402.4   13.41  5462.4   12.72  5602.4   13.93  5622.4   13.46  5762.4   14.28
#Mann= 3 , 1 , 0
 4664.30    0.14       0  4992.3   0.045       0  5007.7    0.14       0
Bank Sta=4992.30,5007.70
Exp/Cntr=0.3,0.1

Type RM Length L Ch R = 1 ,21397.4,543.8,543.8,543.8
XS GIS Cut Line= 3
 2736262.6191916  877634.5966718 2736238.5511134 877414.54567144
 2736365.7680980 876259.27791954
BEGIN DESCRIPTION:
BETHEL CREEK 27.0
END DESCRIPTION:
#Sta/Elev= 30
  4054.9   14.26  4176.2   14.16  4196.2    13.6  4216.2   13.85  4278.5   12.67
  4318.5   13.05  4338.5   13.84  4358.5   14.01  4378.5    13.4  4418.5   14.29
  4438.5   13.76  4498.5   13.46  4578.5   14.53  4598.5   13.37  4638.5    6.82
  4658.5    6.09  4858.5    6.02  4878.5    6.33  4992.4    6.02  4993.9    3.02
  5006.2    3.02  5007.7    6.02  5018.5    5.65  5078.5    6.37  5098.5    7.52
  5118.5   11.21  5138.5   13.27  5158.5   14.16  5398.5   13.71  5438.5   14.16
#Mann= 3 , 1 , 0
 4054.90    0.14       0  4992.4   0.045       0  5007.7    0.14       0
Bank Sta=4992.40,5007.70
Exp/Cntr=0.3,0.1

Type RM Length L Ch R = 1 ,20853.6,539.6,539.6,539.6
XS GIS Cut Line= 3
 2736723.3509736 877445.49034337 2736792.1169112 876919.43092063
 2736764.6105362 876499.95870119
BEGIN DESCRIPTION:
BETHEL CREEK 26.0
END DESCRIPTION:
#Sta/Elev= 30
  4483.7   14.24  4614.2   15.41  4674.2   14.57  4694.2   12.89  4734.2    6.36
  4754.2     5.2  4774.2    5.15  4814.2    5.89  4834.2    5.42  4854.2       6
  4874.2    6.14  4894.2     5.8  4992.3    5.98  4993.8    2.98  5006.1    2.98
  5007.6    5.98  5014.6     5.9  5134.6    6.22  5174.6    5.88  5234.6    5.73
  5254.6    6.58  5274.6    6.65  5294.6    5.31  5314.6     7.4  5334.6   11.41
  5354.6   13.34  5374.6    14.5  5394.6   15.09  5414.6   14.52  5434.6   14.58
#Mann= 3 , 1 , 0
 4483.70    0.14       0  4992.3   0.045       0  5007.6    0.14       0
Bank Sta=4992.30,5007.60
Exp/Cntr=0.3,0.1

Type RM Length L Ch R = 1 ,20314.0,506.2,506.2,506.2
XS GIS Cut Line= 3
 2737441.9550216 877569.26903107 2737283.7933651 876926.30751439
 2737156.5763806 876469.01402926
BEGIN DESCRIPTION:
BETHEL CREEK 25.0
END DESCRIPTION:
#Sta/Elev= 30
  4391.2   14.77  4413.3   14.34  4633.3   14.22  4673.3   14.94  4693.3   14.35
  4713.3   12.44  4753.3    6.97  4773.3    5.51  4793.3    5.08  4813.3    6.07
  4913.3    5.57  4933.3    6.04  4992.3    5.54  4993.8    2.54  5006.2    2.54
  5007.7    5.54  5033.3    5.34  5053.3    5.89    5068    5.39    5088    5.82
    5148    5.61    5208    4.83    5248    5.67    5268    7.47    5288   11.25
    5308   13.95    5328   14.81    5488   15.44    5508   14.61    5528   14.48
#Mann= 3 , 1 , 0
 4391.20    0.14       0  4992.3   0.045       0  5007.7    0.14       0
Bank Sta=4992.30,5007.70
Exp/Cntr=0.3,0.1

Type RM Length L Ch R = 1 ,19807.8,514.4,514.4,514.4
XS GIS Cut Line= 3
 2737902.6868037 877146.35851475 2737761.7166315 876785.33734228
 2737579.4868969 876448.38424798
BEGIN DESCRIPTION:
BETHEL CREEK 24.0
END DESCRIPTION:
#Sta/Elev= 29
  4660.1   15.69  4687.6   14.83  4707.6   14.87  4727.6   13.98  4767.6    7.81
  4787.6    6.16  4807.6    5.09  4847.6    5.11  4867.6    4.53  4907.6    5.07
  4987.6    5.16  4992.4    5.01  4993.9    2.01  5006.2    2.01  5007.7    5.01
  5047.6    4.94  5050.7    4.92  5110.7    5.33  5130.7    4.83  5150.7    5.22
  5210.7    4.98  5230.7    5.57  5250.7    9.42  5270.7   14.04  5290.7   15.51
  5310.7   15.78  5330.7    15.6  5390.7   16.07  5430.7   16.23
#Mann= 3 , 1 , 0
 4660.10    0.14       0  4992.4   0.045       0  5007.7    0.14       0
Bank Sta=4992.40,5007.70
Exp/Cntr=0.3,0.1

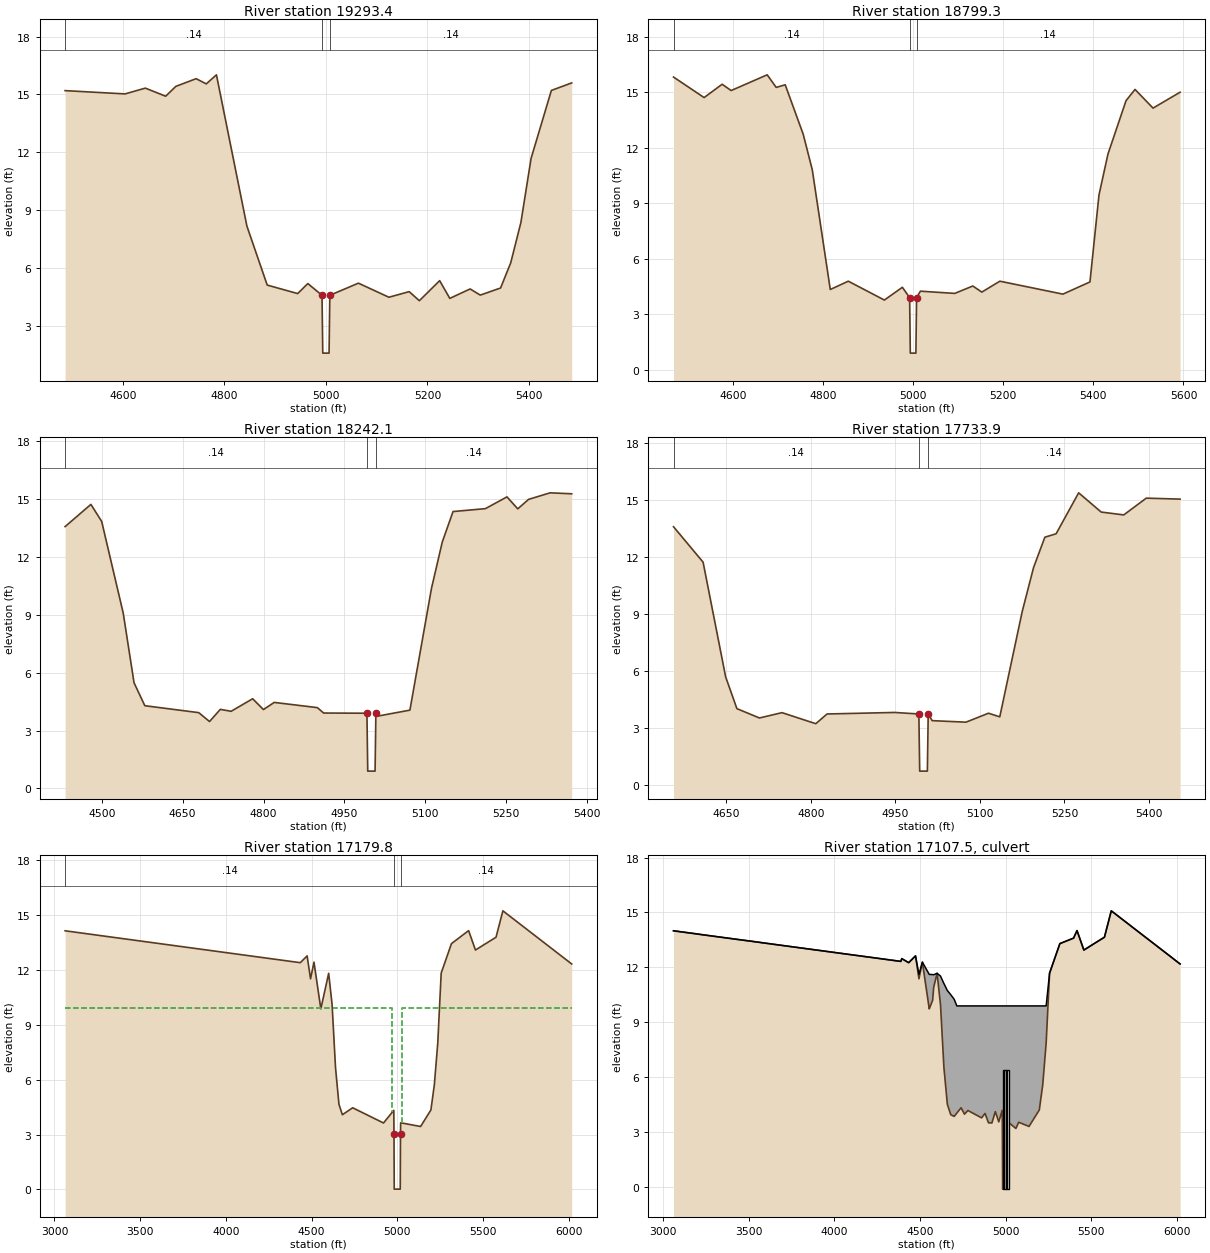
Type RM Length L Ch R = 1 ,19293.4,494.1,494.1,494.1
XS GIS Cut Line= 3
 2738494.0738671 876898.80113934 2738157.1207728  876479.3289199
 2737837.3591629 876149.25241936
BEGIN DESCRIPTION:
BETHEL CREEK 23.0
END DESCRIPTION:
#Sta/Elev= 30
  4486.4    15.2  4604.4   15.03  4644.4   15.33  4684.4   14.91  4704.4   15.42
  4744.4   15.82  4764.4   15.55  4784.4   16.02  4844.4    8.17  4884.4    5.11
  4944.4    4.67  4964.4    5.19  4992.3    4.58  4993.8    1.58  5006.2    1.58
  5007.7    4.58    5064    5.21    5124    4.48    5164    4.77    5184     4.3
    5224    5.34    5244    4.42    5284    4.91    5304    4.59    5344    4.96
    5364    6.27    5384    8.36    5404   11.68    5444   15.21    5484    15.6
#Mann= 3 , 1 , 0
 4486.40    0.14       0  4992.3   0.045       0  5007.7    0.14       0
Bank Sta=4992.30,5007.70
Exp/Cntr=0.3,0.1

Type RM Length L Ch R = 1 ,18799.3,557.2,557.2,557.2
XS GIS Cut Line= 3
 2738863.1831781 876456.12281032 2738410.1324938 876081.37718261
 2737895.5564080 875930.36028787
BEGIN DESCRIPTION:
BETHEL CREEK 22.0
END DESCRIPTION:
#Sta/Elev= 30
  4468.3   15.82  4536.2   14.71  4576.2   15.43  4596.2   15.09  4676.2   15.94
  4696.2   15.26  4716.2    15.4  4756.2   12.72  4776.2   10.81  4816.2    4.33
  4856.2    4.78  4936.2    3.76  4976.2    4.45  4992.3    3.89  4993.8    0.89
  5006.2    0.89  5007.7    3.89  5016.2    4.24  5092.5    4.12  5132.5    4.52
  5152.5    4.19  5192.5    4.78  5332.5    4.08  5392.5    4.74  5412.5    9.44
  5432.5   11.66  5472.5   14.54  5492.5   15.15  5532.5   14.14  5592.5      15
#Mann= 3 , 1 , 0
 4468.30    0.14       0  4992.3   0.045       0  5007.7    0.14       0
Bank Sta=4992.30,5007.70
Exp/Cntr=0.3,0.1

Type RM Length L Ch R = 1 ,18242.1,508.2,508.2,508.2
XS GIS Cut Line= 3
 2738656.2341001 875410.19098374 2738242.3359441 875628.32649837
 2737806.0649148 875807.30948474
BEGIN DESCRIPTION:
BETHEL CREEK 21.0
END DESCRIPTION:
#Sta/Elev= 30
    4432   13.57  4479.8   14.72  4499.8   13.84  4539.8    9.08  4559.8    5.48
  4579.8    4.29  4679.8    3.93  4699.8    3.47  4719.8     4.1  4739.8       4
  4779.8    4.65  4799.8    4.09  4819.8    4.46  4899.8    4.19  4911.4    3.91
  4991.7     3.9  4993.2     0.9  5006.8     0.9  5008.3     3.9  5011.4    3.75
  5071.4    4.06  5111.4   10.37  5131.4   12.77  5151.4   14.35  5211.4    14.5
  5251.4   15.11  5271.4   14.49  5291.4   14.98  5331.4   15.32  5371.4   15.27
#Mann= 3 , 1 , 0
 4432.00    0.14       0  4991.7   0.045       0  5008.3    0.14       0
Bank Sta=4991.70,5008.30
Exp/Cntr=0.3,0.1

Type RM Length L Ch R = 1 ,17733.9,554.15,554.15,554.15
XS GIS Cut Line= 3
 2738510.8104237 875136.12328587 2738119.2851410 875164.08937749
 2737615.8954918 875220.02156073
BEGIN DESCRIPTION:
BETHEL CREEK 20.0
END DESCRIPTION:
#Sta/Elev= 26
  4556.3   13.58  4608.8   11.72  4648.8     5.7  4668.8    4.03  4708.8    3.54
  4748.8    3.82  4808.8    3.24  4828.8    3.75  4948.8    3.83  4991.7    3.75
  4993.2    0.75  5006.8    0.75  5008.3    3.75  5015.3     3.4  5075.3    3.32
  5115.3    3.79  5135.3     3.6  5175.3    9.15  5195.3   11.44  5215.3   13.03
  5235.3   13.21  5275.3   15.36  5315.3   14.35  5355.3    14.2  5395.3   15.08
  5455.3   15.03
#Mann= 3 , 1 , 0
 4556.30    0.14       0  4991.7   0.045       0  5008.3    0.14       0
Bank Sta=4991.70,5008.30
Exp/Cntr=0.3,0.1

Type RM Length L Ch R = 1 ,17179.8,144.5,144.5,144.5
XS GIS Cut Line= 2
 2739528.5693953 876054.69762225 2737498.2311437 873906.90178585
BEGIN DESCRIPTION:
Upstream Section of Bridge/Culvert/Weir
END DESCRIPTION:
#Sta/Elev= 30
  3062.2   14.12  4434.2   12.38  4474.2   12.75  4494.2    11.5  4514.2   12.41
  4554.2    9.86  4599.9    11.8  4619.9   10.09  4639.9    6.65  4659.9    4.65
  4679.9    4.08  4739.9    4.46  4919.9    3.63  4979.9    4.32    4981    3.02
  4982.5    0.02  5017.5    0.02    5019    3.02  5019.9    3.64  5136.4    3.44
  5196.4    4.34  5216.4    5.71  5236.4    7.99  5256.4   11.81  5316.4   13.42
  5416.4   14.13  5456.4   13.07  5576.4   13.77  5616.4   15.21  6017.8   12.31
#Mann= 3 , 1 , 0
 3062.20    0.14       0    4981   0.045       0    5019    0.14       0
#XS Ineff= 2 , 0
       0    4971     9.9    5029       0     9.9
Bank Sta=4981.00,5019.00
Exp/Cntr=0.5,0.3

Type RM Length L Ch R = 2 ,17107.5,,,
BEGIN DESCRIPTION:
US HWY 17-TOR
Structure ID: 123
Approximate Survey Structure
END DESCRIPTION:
Bridge Culvert--1,0,-1,-1, 0
Deck Dist Width WeirC Skew NumUp NumDn MinLoCord MaxHiCord MaxSubmerge Is_Ogee
10,124.5,3,, 46, 46,,,0.95,0,1,1,,
  3062.2  4388.3  4394.2  4434.2  4474.2  4494.2  4514.2  4554.2  4574.2  4579.9
  4599.9  4619.9  4639.9  4659.9  4679.9  4699.9  4715.3  4739.9  4759.9  4779.9
  4859.9  4879.9  4899.9  4919.9  4939.9  4959.9  4979.9    4981  4982.5  5017.5
    5019  5019.9  5059.9  5076.4  5136.4  5196.4  5216.4  5236.4  5256.4  5316.4
  5396.4  5416.4  5456.4  5576.4  5616.4  6017.8
      14   12.33   12.48   12.26   12.63   11.62   12.29   11.62   11.61    11.6
   11.68   11.53   11.12   10.74   10.51   10.26     9.9     9.9     9.9     9.9
     9.9     9.9     9.9     9.9     9.9     9.9     9.9     9.9     9.9     9.9
     9.9     9.9     9.9     9.9     9.9     9.9     9.9     9.9   11.69    13.3
    13.6   14.01   12.95   13.65   15.09   12.19
      14   12.33   12.48   12.26   12.63   11.38   12.29    9.74   10.21    10.9
   11.68    9.97    6.53    4.53    3.96    3.87    4.05    4.34    3.99    4.19
    3.79    4.03    3.52    3.51    4.13    3.57     4.2     2.9    -0.1    -0.1
     2.9    3.52    3.21    3.55    3.32    4.22    5.59    7.87   11.69    13.3
    13.6   14.01   12.95   13.65   15.09   12.19
  3062.2  4388.3  4394.2  4434.2  4474.2  4494.2  4514.2  4554.2  4574.2  4579.9
  4599.9  4619.9  4639.9  4659.9  4679.9  4699.9  4715.3  4739.9  4759.9  4779.9
  4859.9  4879.9  4899.9  4919.9  4939.9  4959.9  4979.9    4981  4982.5  5017.5
    5019  5019.9  5059.9  5076.4  5136.4  5196.4  5216.4  5236.4  5256.4  5316.4
  5396.4  5416.4  5456.4  5576.4  5616.4  6017.8
   13.69   12.03   12.18   11.96   12.33   11.62   11.99   11.62   11.61    11.6
   11.58   11.53   11.12   10.74   10.51   10.26     9.9     9.9     9.9     9.9
     9.9     9.9     9.9     9.9     9.9     9.9     9.9     9.9     9.9     9.9
     9.9     9.9     9.9     9.9     9.9     9.9     9.9     9.9   11.39      13
    13.3   13.71   12.65   13.35   14.79   11.88
   13.38   11.71   11.86   11.64   12.01   10.76   11.67    9.12    9.59   10.28
   11.06    9.35    5.91    3.91    3.34    3.25    3.43    3.72    3.37    3.57
    3.17    3.41     2.9    2.89    3.51    2.95    3.58    2.28   -0.72   -0.72
    2.28     2.9    2.59    2.93     2.7     3.6    4.97    7.25   11.07   12.68
   12.98   13.39   12.33   13.03   14.47   11.57
BR Coef= 1 , 0 , 0 ,1.25, 0 ,,,0.8,-1,2,0,
Wspro=,,,, 1 ,,,, 0 ,,,, 0 ,,,,-1 ,-1 ,-1 , 0 , 0 , 0 , 0 , 0
Culvert=2,6.5,8.0,124.5,0.015,0.4,1.0,8,1,-0.09,4986.46,-0.71,4986.46,Culvert #1  ,0,10
Culvert=2,6.5,8.0,124.5,0.015,0.4,1.0,8,1,-0.09,4995.46,-0.71,4995.46,Culvert #2  ,0,10
Culvert=2,6.5,8.0,124.5,0.015,0.4,1.0,8,1,-0.09,5004.46,-0.71,5004.46,Culvert #3  ,0,10
Culvert=2,6.5,8.0,124.5,0.015,0.4,1.0,8,1,-0.09,5013.46,-0.71,5013.46,Culvert #4  ,0,10
BC Design=,, 0 ,, 0 ,,,,,,
BR U #Sta/Elev= 69
  3062.2      14  3117.8   13.93  3197.8   13.83  3217.8    13.8  3297.8    13.7
  3417.8   13.55  3517.8   13.43  3557.8   13.38  3577.8   13.35  4388.3   12.33
  4394.2   12.48  4434.2   12.26  4474.2   12.63  4494.2   11.38  4514.2   12.29
  4554.2    9.74  4557.8    9.82  4574.2   10.21  4579.9    10.9  4599.9   11.68
  4617.8   10.15  4619.9    9.97  4639.9    6.53  4657.8    4.74  4659.9    4.53
  4679.9    3.96  4697.8    3.88  4699.9    3.87  4715.3    4.05  4739.9    4.34
  4759.9    3.99  4779.9    4.19  4859.9    3.79  4879.9    4.03  4899.9    3.52
  4919.9    3.51  4939.9    4.13  4959.9    3.57  4979.9     4.2    4981     2.9
  4982.5    -0.1    5000    -0.1  5017.5    -0.1    5019     2.9  5019.9    3.52
  5059.9    3.21  5076.4    3.55  5136.4    3.32  5196.4    4.22  5216.4    5.59
  5236.4    7.87  5256.4   11.69  5316.4    13.3  5396.4    13.6  5416.4   14.01
  5427.7   13.71  5456.4   12.95  5477.8   13.07  5517.8   13.31  5576.4   13.65
  5616.4   15.09  5617.8   15.08  5657.8   14.79  5717.8   14.36  5737.8   14.21
  5897.8   13.06  5977.8   12.48  5997.8   12.33  6017.8   12.19
BR U #Mann= 3
 3062.20    0.14    4981   0.045    5019    0.14
BR U Banks=4981.00,5019.00
BR D #Sta/Elev= 69
  3062.2   13.38  3117.8   13.31  3197.8   13.21  3217.8   13.18  3297.8   13.08
  3417.8   12.93  3517.8   12.81  3557.8   12.76  3577.8   12.73  4388.3   11.71
  4394.2   11.86  4434.2   11.64  4474.2   12.01  4494.2   10.76  4514.2   11.67
  4554.2    9.12  4557.8     9.2  4574.2    9.59  4579.9   10.28  4599.9   11.06
  4617.8    9.53  4619.9    9.35  4639.9    5.91  4657.8    4.12  4659.9    3.91
  4679.9    3.34  4697.8    3.26  4699.9    3.25  4715.3    3.43  4739.9    3.72
  4759.9    3.37  4779.9    3.57  4859.9    3.17  4879.9    3.41  4899.9     2.9
  4919.9    2.89  4939.9    3.51  4959.9    2.95  4979.9    3.58    4981    2.28
  4982.5   -0.72    5000   -0.72  5017.5   -0.72    5019    2.28  5019.9     2.9
  5059.9    2.59  5076.4    2.93  5136.4     2.7  5196.4     3.6  5216.4    4.97
  5236.4    7.25  5256.4   11.07  5316.4   12.68  5396.4   12.98  5416.4   13.39
  5427.7   13.09  5456.4   12.33  5477.8   12.45  5517.8   12.69  5576.4   13.03
  5616.4   14.47  5617.8   14.46  5657.8   14.17  5717.8   13.74  5737.8   13.59
  5897.8   12.44  5977.8   11.86  5997.8   11.71  6017.8   11.57
BR D #Mann= 3
 3062.20    0.14    4981   0.045    5019    0.14
BR D Banks=4981.00,5019.00

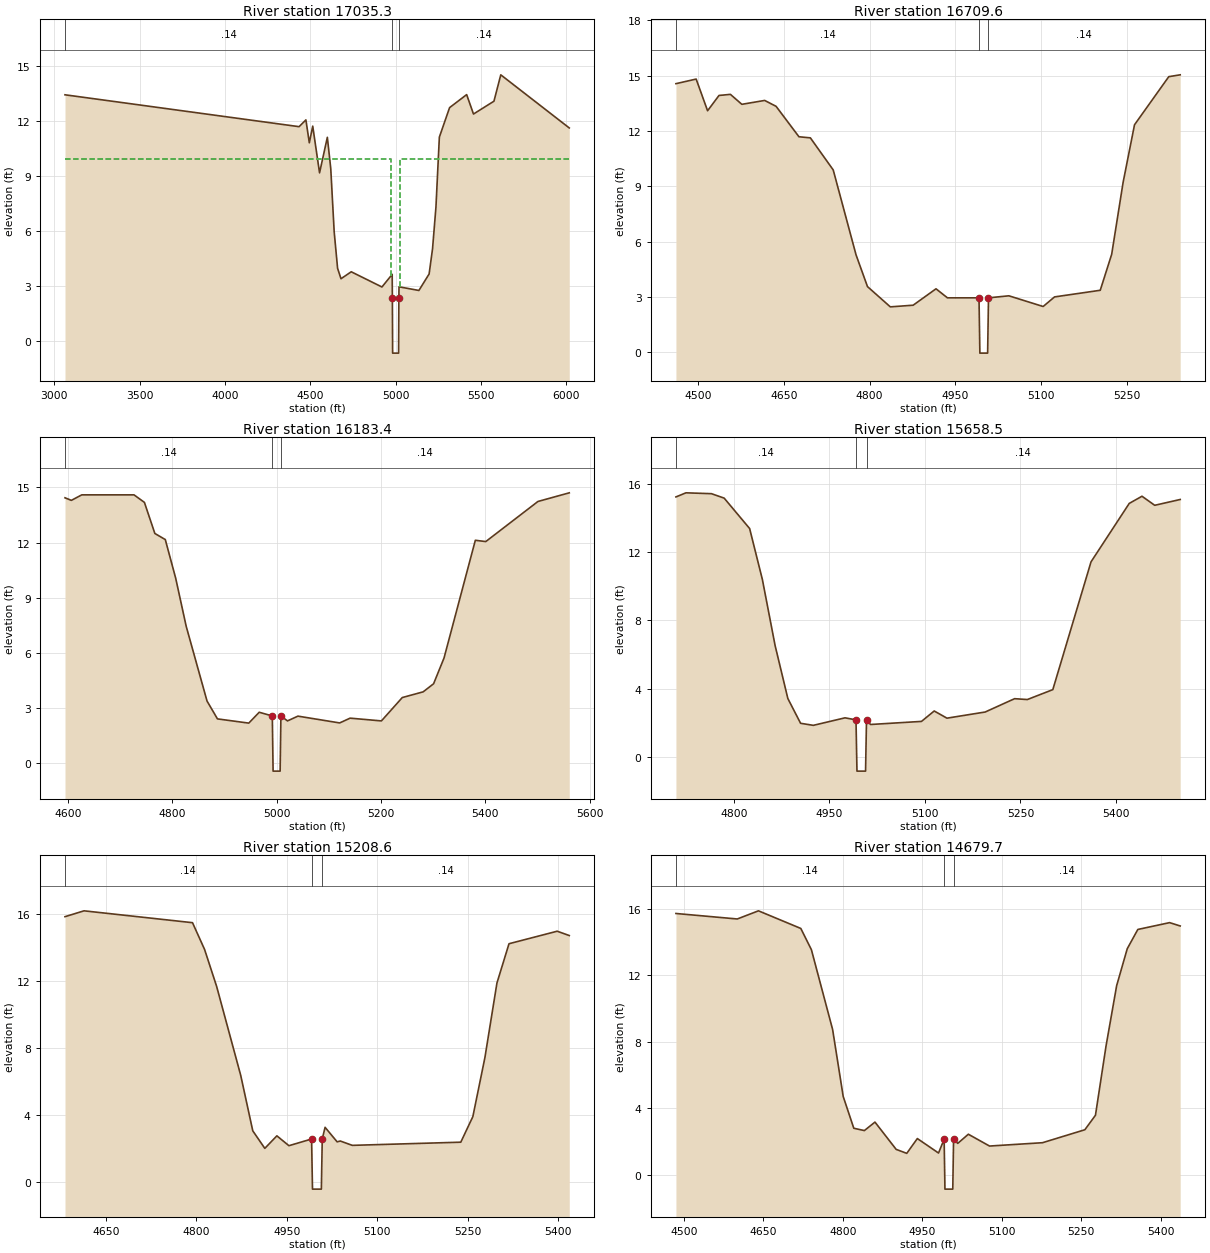
Type RM Length L Ch R = 1 ,17035.3,325.65,325.65,325.65
XS GIS Cut Line= 2
 2739629.6608518 875951.44662990 2737599.3226002 873803.65079350
BEGIN DESCRIPTION:
Downstream Section of Bridge/Culvert/Weir
END DESCRIPTION:
#Sta/Elev= 30
  3062.2   13.43  4434.2   11.69  4474.2   12.06  4494.2   10.81  4514.2   11.72
  4554.2    9.17  4599.9   11.11  4619.9     9.4  4639.9    5.96  4659.9    3.96
  4679.9    3.39  4739.9    3.77  4919.9    2.94  4979.9    3.63    4981    2.33
  4982.5   -0.67  5017.5   -0.67    5019    2.33  5019.9    2.95  5136.4    2.75
  5196.4    3.65  5216.4    5.02  5236.4     7.3  5256.4   11.12  5316.4   12.73
  5416.4   13.44  5456.4   12.38  5576.4   13.08  5616.4   14.52  6017.8   11.62
#Mann= 3 , 1 , 0
 3062.20    0.14       0    4981   0.045       0    5019    0.14       0
#XS Ineff= 2 , 0
       0 4974.33     9.9 5025.67       0     9.9
Bank Sta=4981.00,5019.00
Exp/Cntr=0.5,0.3

Type RM Length L Ch R = 1 ,16709.6,526.2,526.2,526.2
XS GIS Cut Line= 3
 2738777.3823842 874814.13085404 2738527.5619626 874295.75347911
 2738324.5828700 874064.66958908
BEGIN DESCRIPTION:
BETHEL CREEK 19.0
END DESCRIPTION:
#Sta/Elev= 30
    4461   14.57  4496.4   14.82  4516.4    13.1  4536.4   13.93  4556.4   13.99
  4576.4   13.45  4616.4   13.66  4636.4   13.34  4676.4   11.69  4696.4   11.63
  4736.4    9.89  4776.4    5.28  4796.4    3.56  4836.4    2.46  4876.4    2.55
  4916.4    3.44  4936.4    2.95  4991.7    2.95  4993.2   -0.05  5006.8   -0.05
  5008.3    2.95    5044    3.06    5104    2.48    5124       3    5204    3.36
    5224    5.31    5244    9.21    5264   12.34    5324   14.95    5344   15.05
#Mann= 3 , 1 , 0
 4461.00    0.14       0  4991.7   0.045       0  5008.3    0.14       0
Bank Sta=4991.70,5008.30
Exp/Cntr=0.3,0.1

Type RM Length L Ch R = 1 ,16183.4,524.9,524.9,524.9
XS GIS Cut Line= 3
 2739036.5710717 874077.16061017 2738724.2955446 873839.83120959
 2738152.8313301 873783.62161472
BEGIN DESCRIPTION:
BETHEL CREEK 18.0
END DESCRIPTION:
#Sta/Elev= 30
  4594.5   14.44  4606.7    14.3  4626.7    14.6  4726.7    14.6  4746.7   14.19
  4766.7    12.5  4786.7   12.17  4806.7   10.06  4826.7    7.46  4866.7    3.39
  4886.7    2.42  4946.7    2.19  4966.7    2.78  4991.8    2.58  4993.3   -0.42
  5006.8   -0.42  5008.3    2.58  5020.9    2.31  5040.9    2.57  5120.9     2.2
  5140.9    2.46  5200.9    2.31  5240.9    3.58  5280.9    3.89  5300.9    4.33
  5320.9    5.73  5380.9   12.13  5400.9   12.06  5500.9   14.24  5560.9   14.71
#Mann= 3 , 1 , 0
 4594.50    0.14       0  4991.8   0.045       0  5008.3    0.14       0
Bank Sta=4991.80,5008.30
Exp/Cntr=0.3,0.1

Type RM Length L Ch R = 1 ,15658.5,449.9,449.9,449.9
XS GIS Cut Line= 4
 2739208.3226116 873418.25924805 2738992.8524979 873408.89098224
 2738746.1548315 873299.59454777 2738440.1248150 873290.22628196
BEGIN DESCRIPTION:
BETHEL CREEK 17.0
END DESCRIPTION:
#Sta/Elev= 28
  4709.1   15.22  4724.8   15.46  4764.8   15.41  4784.8   15.15  4824.8   13.37
  4844.8   10.39  4864.8    6.52  4884.8    3.42  4904.8    1.97  4924.8    1.85
  4974.6    2.29  4991.8    2.17  4993.3   -0.83  5006.8   -0.83  5008.3    2.17
  5014.6     1.9  5094.6    2.08  5114.6    2.69  5134.6    2.27  5194.6    2.63
  5240.8    3.41  5260.8    3.36  5300.8    3.94  5360.8   11.42  5420.8   14.84
  5440.8   15.26  5460.8   14.73  5500.8   15.07
#Mann= 3 , 1 , 0
 4709.10    0.14       0  4991.8   0.045       0  5008.3    0.14       0
Bank Sta=4991.80,5008.30
Exp/Cntr=0.3,0.1

Type RM Length L Ch R = 1 ,15208.6,528.9,528.9,528.9
XS GIS Cut Line= 3
 2739277.0232276 873315.20832412 2738999.0980085 872959.21422326
 2738924.1518820 872581.36083551
BEGIN DESCRIPTION:
BETHEL CREEK 16.0
END DESCRIPTION:
#Sta/Elev= 25
    4582   15.86  4613.6   16.21  4793.6    15.5  4813.6    13.9  4833.6   11.69
  4873.6    6.36  4893.6    3.04  4913.6    1.99  4933.6    2.74  4953.6    2.15
  4991.2    2.55  4992.7   -0.45  5007.4   -0.45  5008.9    2.55  5013.6    3.25
  5033.6    2.38  5038.8    2.43  5058.8    2.17  5238.8    2.36  5258.8    3.89
  5278.8    7.42  5298.8   11.89  5318.8   14.24  5398.8   14.99  5418.8   14.73
#Mann= 3 , 1 , 0
 4582.00    0.14       0  4991.2   0.045       0  5008.9    0.14       0
Bank Sta=4991.20,5008.90
Exp/Cntr=0.3,0.1

Type RM Length L Ch R = 1 ,14679.7,633.4,633.4,633.4
XS GIS Cut Line= 3
 2739626.7718179 873196.54362384 2739439.4065016 872737.49859905
 2739420.6699700 872281.57632953
BEGIN DESCRIPTION:
BETHEL CREEK 15.0
END DESCRIPTION:
#Sta/Elev= 30
  4484.7   15.71  4600.5   15.38  4640.5   15.87  4720.5   14.81  4740.5   13.53
  4780.5    8.74  4800.5    4.71  4820.5     2.8  4840.5    2.66  4860.5    3.17
  4900.5    1.53  4920.5    1.29  4940.5    2.18  4980.5    1.31  4991.1    2.14
  4992.6   -0.86  5007.4   -0.86  5008.9    2.14  5016.8    1.89  5036.8    2.44
  5076.8    1.73  5176.8    1.93  5256.8    2.71  5276.8    3.58  5296.8    7.75
  5316.8   11.37  5336.8   13.59  5356.8   14.75  5416.8   15.16  5436.8   14.96
#Mann= 3 , 1 , 0
 4484.70    0.14       0  4991.1   0.045       0  5008.9    0.14       0
Bank Sta=4991.10,5008.90
Exp/Cntr=0.3,0.1

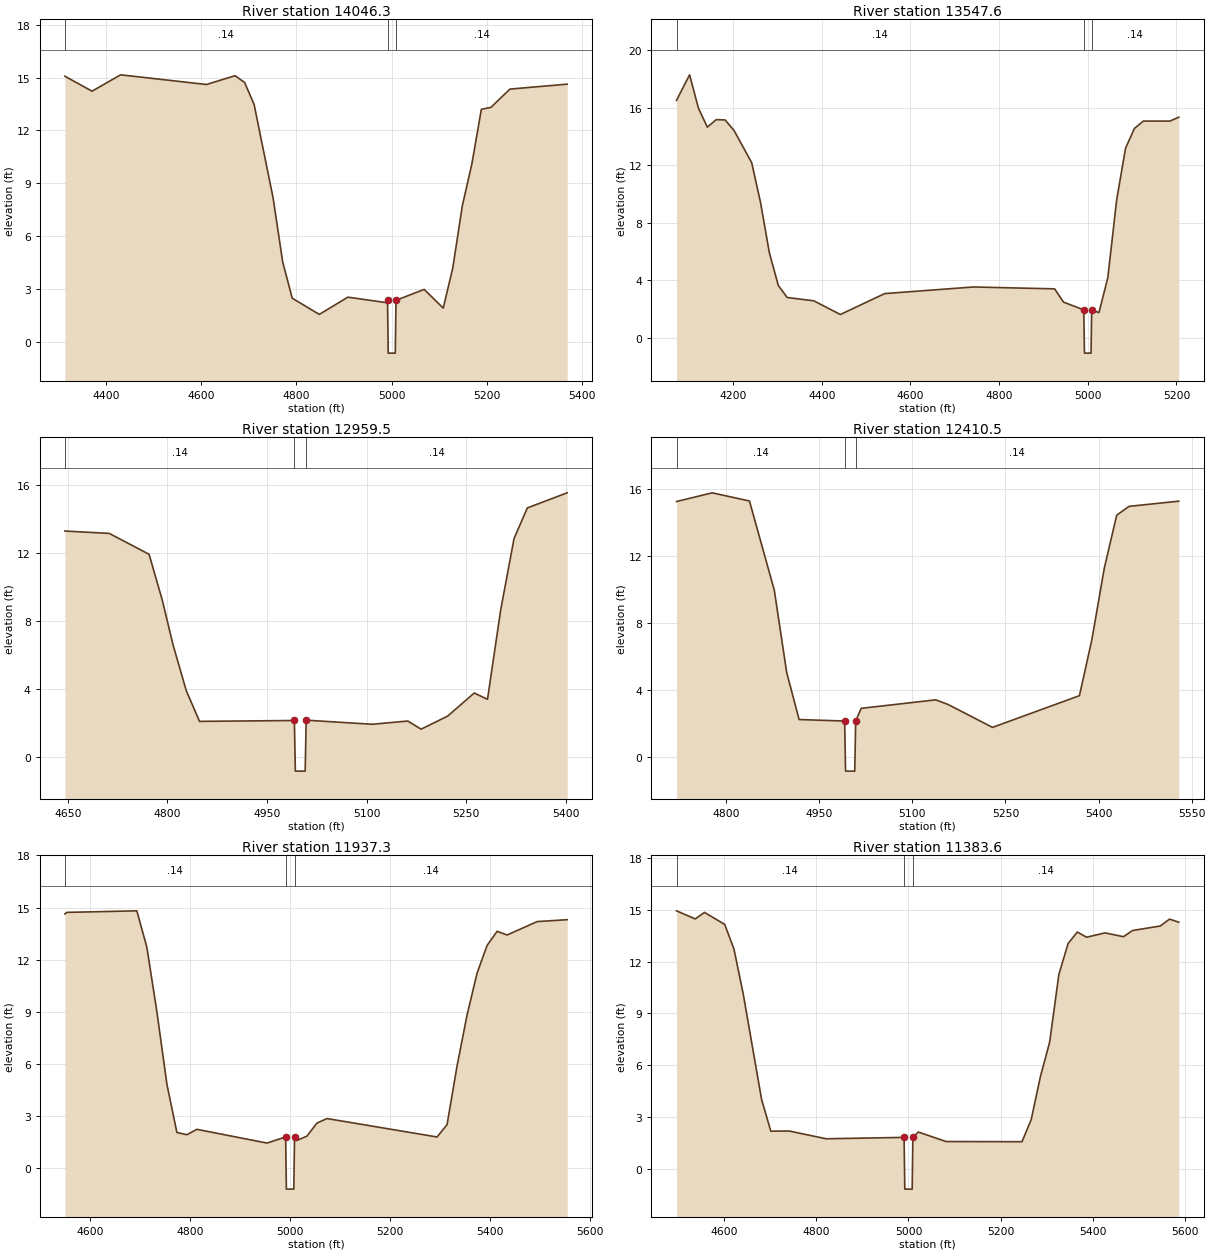
Type RM Length L Ch R = 1 ,14046.3,498.7,498.7,498.7
XS GIS Cut Line= 3
 2739882.8377501 873099.73821044 2739929.6790791  872625.0794093
 2739979.6431635  872050.4924395
BEGIN DESCRIPTION:
BETHEL CREEK 14.0
END DESCRIPTION:
#Sta/Elev= 26
  4314.3   15.08  4371.2   14.23  4431.2   15.16  4611.2   14.61  4671.2   15.11
  4691.2   14.73  4711.2   13.48  4751.2    8.15  4771.2    4.53  4791.2    2.47
    4848    1.55    4908    2.53    4988    2.22  4991.1    2.35  4992.6   -0.65
  5007.4   -0.65  5008.9    2.35    5068    2.97    5108    1.91    5128    4.18
    5148    7.71    5168   10.09    5188    13.2    5208   13.31    5248   14.35
    5368   14.63
#Mann= 3 , 1 , 0
 4314.30    0.14       0  4991.1   0.045       0  5008.9    0.14       0
Bank Sta=4991.10,5008.90
Exp/Cntr=0.3,0.1

Type RM Length L Ch R = 1 ,13547.6,588.1,588.1,588.1
XS GIS Cut Line= 3
 2740026.4844925 873177.80709221 2740426.1971672 872640.69318566
 2740457.4247199  872178.5254056
BEGIN DESCRIPTION:
BETHEL CREEK 13.0
END DESCRIPTION:
#Sta/Elev= 30
  4072.6    16.5  4102.1   18.27  4122.1   15.95  4142.1   14.64  4162.1   15.16
  4182.1   15.14  4202.1   14.42  4242.1   12.18  4262.1    9.41  4282.1    5.91
  4302.1    3.66  4322.1    2.82  4382.1    2.59  4442.1    1.64  4542.1    3.09
  4742.1    3.55  4925.3    3.42  4945.3     2.5  4991.1    1.96  4992.6   -1.04
  5007.4   -1.04  5008.9    1.96  5025.3    1.77  5045.3     4.2  5065.3    9.61
  5085.3   13.18  5105.3   14.55  5125.3   15.06  5185.3   15.06  5205.3   15.33
#Mann= 3 , 1 , 0
 4072.60    0.14       0  4991.1   0.045       0  5008.9    0.14       0
Bank Sta=4991.10,5008.90
Exp/Cntr=0.3,0.1

Type RM Length L Ch R = 1 ,12959.5,549,549,549
XS GIS Cut Line= 4
 2741056.9937318 872956.09146799 2740985.1703606  872828.0585019
  2740885.242192 872528.27399591 2740716.6134073 872287.82184007
BEGIN DESCRIPTION:
BETHEL CREEK 12.0
END DESCRIPTION:
#Sta/Elev= 22
  4645.5   13.31  4712.3   13.17  4772.3   11.94  4792.3    9.22  4808.3    6.62
  4828.3    3.91  4848.3     2.1  4988.3    2.15  4991.1    2.17  4992.6   -0.83
  5007.4   -0.83  5008.9    2.17  5108.3    1.93    5162    2.12    5182    1.64
    5222    2.41    5262    3.77    5282     3.4    5302    8.69    5322   12.87
    5342   14.67    5402   15.56
#Mann= 3 , 1 , 0
 4645.50    0.14       0  4991.1   0.045       0  5008.9    0.14       0
Bank Sta=4991.10,5008.90
Exp/Cntr=0.3,0.1

Type RM Length L Ch R = 1 ,12410.5,473.2,473.2,473.2
XS GIS Cut Line= 3
 2741603.4759042 872372.13623238 2741191.2722085 872225.36673466
 2740860.2601498 872056.73795004
BEGIN DESCRIPTION:
BETHEL CREEK 11.0
END DESCRIPTION:
#Sta/Elev= 20
  4720.3   15.28  4777.8    15.8  4837.8   15.31  4877.8    9.97  4897.8    5.03
  4917.8    2.22  4991.1    2.13  4992.6   -0.87  5007.4   -0.87  5008.9    2.13
  5017.8    2.89  5137.8     3.4  5157.8    3.12  5229.3    1.75  5369.3    3.65
  5389.3       7  5409.3   11.28  5429.3   14.46  5449.3   14.99  5529.3    15.3
#Mann= 3 , 1 , 0
 4720.30    0.14       0  4991.1   0.045       0  5008.9    0.14       0
Bank Sta=4991.10,5008.90
Exp/Cntr=0.3,0.1

Type RM Length L Ch R = 1 ,11937.3,553.7,553.7,553.7
XS GIS Cut Line= 3
 2741734.6316256 872169.15713978 2741453.5836512 871825.65406001
 2741016.3979133  871475.9054697
BEGIN DESCRIPTION:
BETHEL CREEK 10.0
END DESCRIPTION:
#Sta/Elev= 28
    4550   14.63  4553.8   14.72  4693.8   14.81  4713.8   12.71  4733.8    9.01
  4753.8    4.84  4773.8    2.06  4793.8    1.93  4813.8    2.24  4953.8    1.45
  4991.1     1.8  4992.6    -1.2  5007.4    -1.2  5008.9     1.8  5013.7     1.6
  5033.7    1.85  5053.7     2.6  5073.7    2.86  5293.7     1.8  5313.7    2.51
  5333.7    5.89  5353.7    8.82  5373.7   11.23  5393.7   12.82  5413.7   13.63
  5433.7   13.42  5493.7   14.19  5553.7    14.3
#Mann= 3 , 1 , 0
 4550.00    0.14       0  4991.1   0.045       0  5008.9    0.14       0
Bank Sta=4991.10,5008.90
Exp/Cntr=0.3,0.1

Type RM Length L Ch R = 1 ,11383.6,509.3,509.3,509.3
XS GIS Cut Line= 4
 2742206.1676714 871813.16303893 2742106.2395028 871800.67201785
 2741712.7723387 871316.64495089 2741609.7214147 870966.89636058
BEGIN DESCRIPTION:
BETHEL CREEK 9.0
END DESCRIPTION:
#Sta/Elev= 30
    4497   14.95  4537.7   14.48  4557.7   14.86  4601.5   14.16  4621.5   12.74
  4641.5   10.15  4681.5    4.01  4701.5    2.17  4741.5    2.18  4821.5    1.73
  4990.5    1.81    4992   -1.19    5008   -1.19  5009.5    1.81  5021.5    2.12
  5081.5    1.57  5246.1    1.56  5266.1    2.84  5286.1    5.34  5306.1    7.33
  5326.1   11.26  5346.1   13.05  5366.1   13.72  5386.1   13.42  5426.1   13.67
  5466.1   13.45  5486.1   13.81  5546.1   14.07  5566.1   14.47  5586.1   14.29
#Mann= 3 , 1 , 0
 4497.00    0.14       0  4990.5   0.045       0  5009.5    0.14       0
Bank Sta=4990.50,5009.50
Exp/Cntr=0.3,0.1