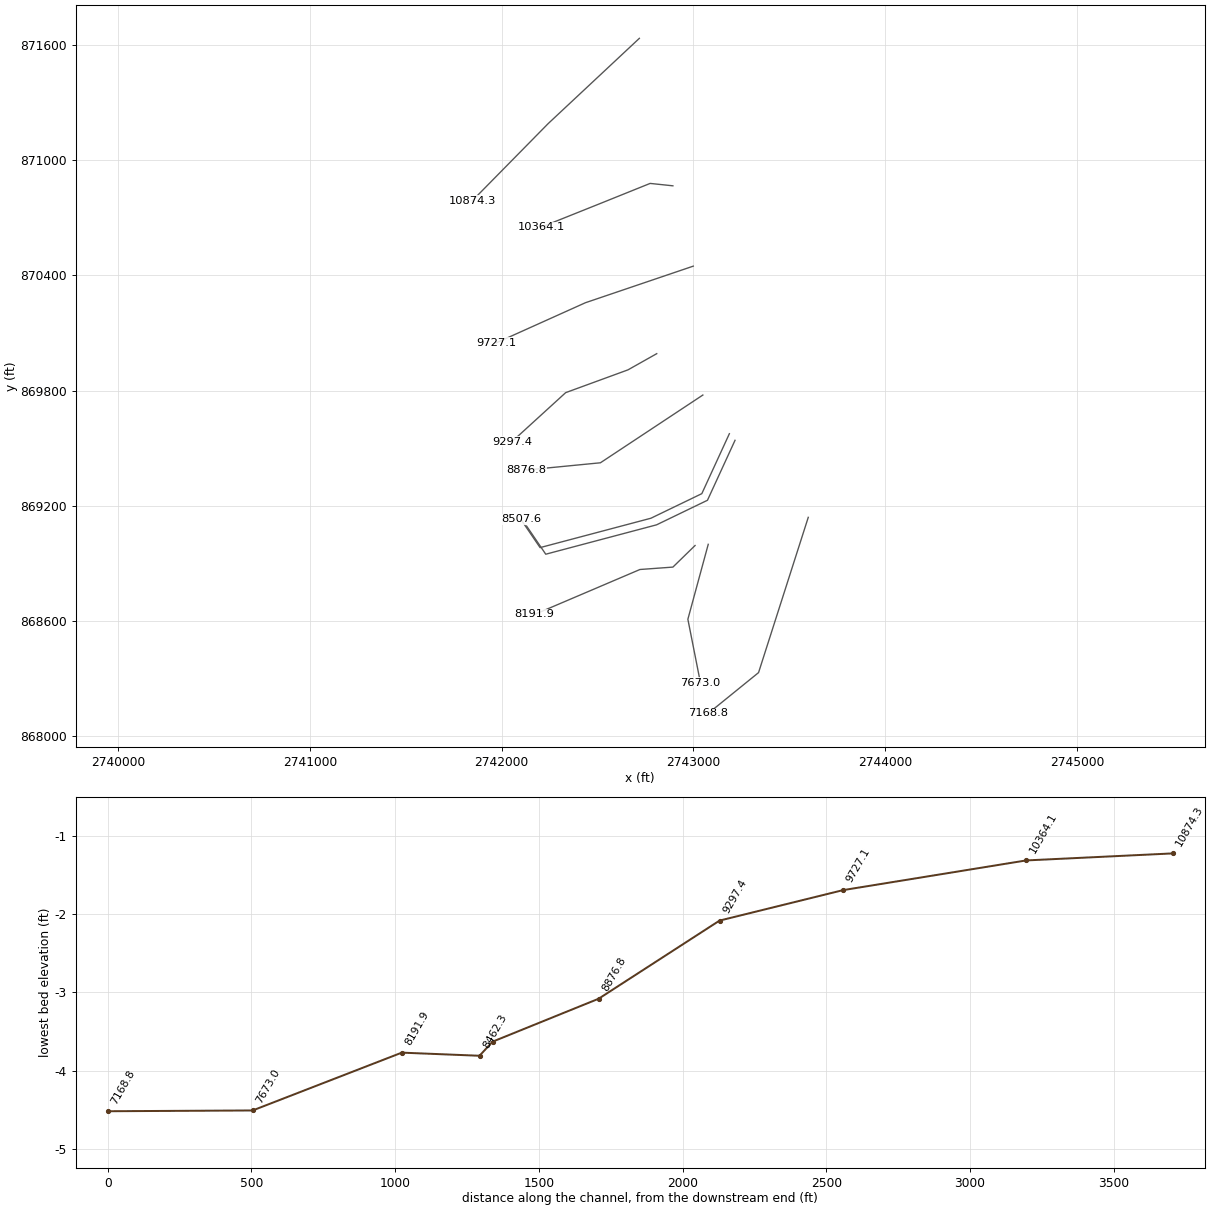
HEC-RAS study BETHEL CREEK.PRJ: Bethel Creek

--- BETHEL CREEK.g01 (geometry) --- (continued)

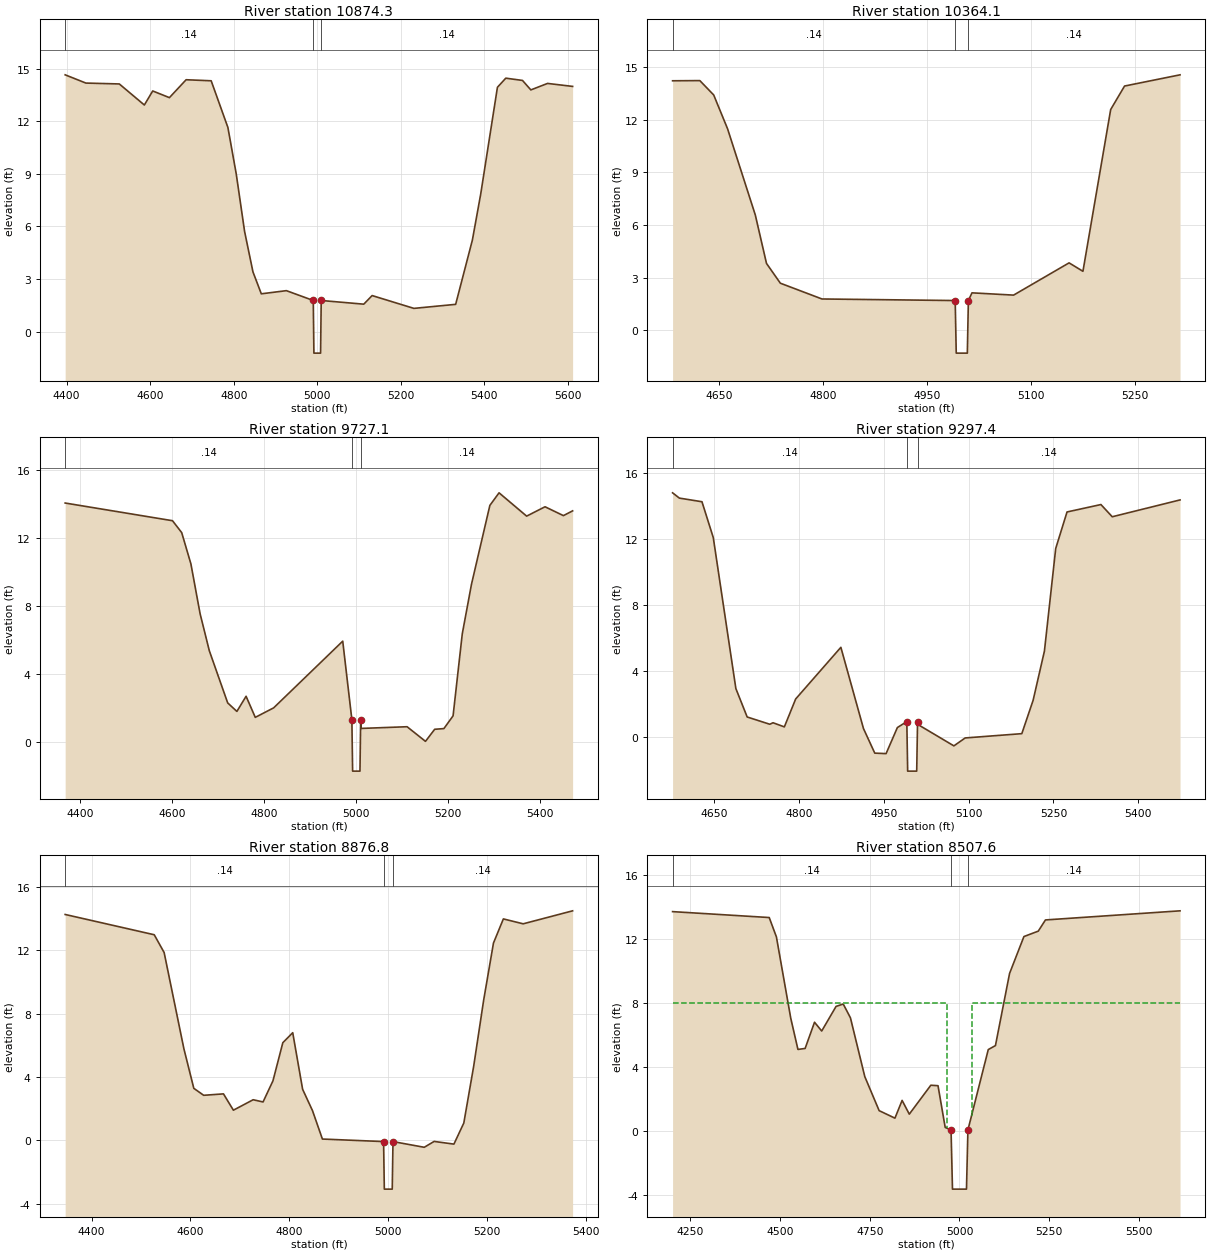
Type RM Length L Ch R = 1 ,10874.3,510.2,510.2,510.2
XS GIS Cut Line= 3
 2742718.2995358  871635.1659885 2742243.6407347 871191.73474006
 2741847.0508153 870788.89931015
BEGIN DESCRIPTION:
BETHEL CREEK 8.0
END DESCRIPTION:
#Sta/Elev= 30
  4396.5   14.64  4446.1   14.17  4526.1   14.12  4586.1   12.92  4606.1   13.72
  4646.1   13.34  4686.1   14.36  4746.1    14.3  4786.1   11.64  4806.1    8.99
  4826.1    5.71  4846.1    3.41  4866.1    2.16  4926.1    2.34  4990.5    1.78
    4992   -1.22    5008   -1.22  5009.5    1.78  5111.4    1.57  5131.4    2.06
  5231.4    1.33  5331.4    1.56  5371.4    5.22  5391.4    7.85  5431.4   13.93
  5451.4   14.45  5491.4   14.32  5511.4   13.78  5551.4   14.15  5611.4   13.98
#Mann= 3 , 1 , 0
 4396.50    0.14       0  4990.5   0.045       0  5009.5    0.14       0
Bank Sta=4990.50,5009.50
Exp/Cntr=0.3,0.1

Type RM Length L Ch R = 1 ,10364.1,637,637,637
XS GIS Cut Line= 4
 2742893.1738310 870866.96819191 2742774.5091307   870879.459213
 2742518.4431985 870776.40828906 2742206.1676714 870651.49807824
BEGIN DESCRIPTION:
BETHEL CREEK 7.0
END DESCRIPTION:
#Sta/Elev= 19
    4583   14.23  4622.3   14.24  4642.3   13.42  4662.3   11.49  4702.3    6.57
  4718.4    3.81  4738.4    2.68  4798.4    1.78  4990.5    1.69    4992   -1.31
    5008   -1.31  5009.5    1.69  5014.7    2.13  5074.7       2  5154.7    3.84
  5174.7    3.36  5214.7   12.59  5234.7   13.93  5314.7   14.57
#Mann= 3 , 1 , 0
 4583.00    0.14       0  4990.5   0.045       0  5009.5    0.14       0
Bank Sta=4990.50,5009.50
Exp/Cntr=0.3,0.1

Type RM Length L Ch R = 1 ,9727.1,429.7,429.7,429.7
XS GIS Cut Line= 3
 2742999.3475102 870448.51898564 2742437.2515615 870258.03091413
 2741971.9610261   870048.806311
BEGIN DESCRIPTION:
BETHEL CREEK 6.0
END DESCRIPTION:
#Sta/Elev= 30
  4366.8   14.07  4600.3   13.03  4620.3   12.33  4640.3   10.49  4660.3    7.56
  4680.3    5.39  4720.3    2.32  4740.3    1.82  4760.3    2.71  4780.3    1.47
  4820.3    2.03  4970.5    5.95  4990.4    1.33    4992   -1.69    5008   -1.69
  5009.5    1.31  5010.5    0.82  5110.5    0.92  5150.5    0.06  5170.5    0.77
  5190.5    0.81  5210.5    1.56  5230.5    6.38  5250.5    9.29  5290.5   13.93
  5310.5   14.67  5370.5    13.3  5410.5   13.85  5450.5   13.33  5470.5   13.61
#Mann= 3 , 1 , 0
 4366.80    0.14       0  4990.4   0.045       0  5009.5    0.14       0
Bank Sta=4990.40,5009.50
Exp/Cntr=0.3,0.1

Type RM Length L Ch R = 1 ,9297.4,420.6,420.6,420.6
XS GIS Cut Line= 4
 2742808.8594387 869992.59671613 2742658.9671857 869908.28232382
 2742334.2006375 869789.61762353 2742053.1526632 869533.55169134
BEGIN DESCRIPTION:
BETHEL CREEK 5.0
END DESCRIPTION:
#Sta/Elev= 30
    4576   14.78    4588   14.46    4628   14.24    4648   12.07    4688    2.92
    4708     1.2    4748    0.76  4753.8    0.85  4773.8     0.6  4793.8    2.29
  4873.8    5.42  4913.8     0.5  4933.8   -0.99  4953.8   -1.02  4973.8    0.56
  4990.5    0.92    4992   -2.08    5008   -2.08  5009.5    0.92  5013.8    0.67
  5073.8   -0.55  5093.8   -0.07    5194    0.19    5214    2.21    5234    5.19
    5254   11.41    5274   13.62    5334   14.07    5354   13.33    5474   14.35
#Mann= 3 , 1 , 0
 4576.00    0.14       0  4990.5   0.045       0  5009.5    0.14       0
Bank Sta=4990.50,5009.50
Exp/Cntr=0.3,0.1

Type RM Length L Ch R = 1 ,8876.8,369.25,369.25,369.25
XS GIS Cut Line= 3
 2743049.3115945 869777.12660245 2742515.3204432 869424.25525686
  2742131.221545 869386.78219362
BEGIN DESCRIPTION:
BETHEL CREEK 4.0
END DESCRIPTION:
#Sta/Elev= 30
  4346.7   14.25  4526.8   12.97  4546.8   11.85  4586.8    5.77  4606.8    3.28
  4626.8    2.84  4666.8    2.93  4686.8     1.9  4726.8    2.56  4746.8    2.42
  4766.8    3.75  4786.8    6.16  4806.8    6.79  4826.8    3.22  4846.8    1.87
  4866.8    0.08  4990.5   -0.08    4992   -3.08    5008   -3.08  5009.5   -0.08
  5072.7   -0.44  5092.7   -0.07  5132.7   -0.24  5152.7    1.09  5172.7    4.68
  5192.7    8.82  5212.7   12.45  5232.7   13.97  5272.7   13.66  5372.7   14.48
#Mann= 3 , 1 , 0
 4346.70    0.14       0  4990.5   0.045       0  5009.5    0.14       0
Bank Sta=4990.50,5009.50
Exp/Cntr=0.3,0.1

Type RM Length L Ch R = 1 ,8507.6,45.3,45.3,45.3
XS GIS Cut Line= 5
 2743187.5865062 869575.73117667 2743043.9397637 869263.45564961
 2742778.5055657 869135.42268351 2742200.7958406 868982.40767524
 2742100.8676720 869129.17717297
BEGIN DESCRIPTION:
Upstream Section of Bridge/Culvert/Weir
END DESCRIPTION:
#Sta/Elev= 30
  4200.8   13.73    4470   13.36    4490   12.15    4530    7.06    4550    5.11
    4570    5.17  4596.2    6.81  4616.2    6.26  4656.2     7.8  4676.2    7.95
  4696.2    7.09  4736.2    3.41  4776.2    1.28  4820.2    0.81  4840.2    1.92
  4860.2    1.06  4920.2    2.87  4940.2    2.84  4960.2    0.23  4976.5    0.07
  4980.5   -3.63  5019.5   -3.63  5023.5    0.07  5080.2     5.1  5100.2    5.35
  5139.5    9.86  5179.5   12.17  5219.5   12.51  5239.5   13.21  5614.4   13.78
#Mann= 3 , 1 , 0
 4200.80    0.14       0  4976.5   0.045       0  5023.5    0.14       0
#XS Ineff= 2 , 0
       0  4966.5       8  5033.5       0       8
Bank Sta=4976.50,5023.50
Exp/Cntr=0.5,0.3

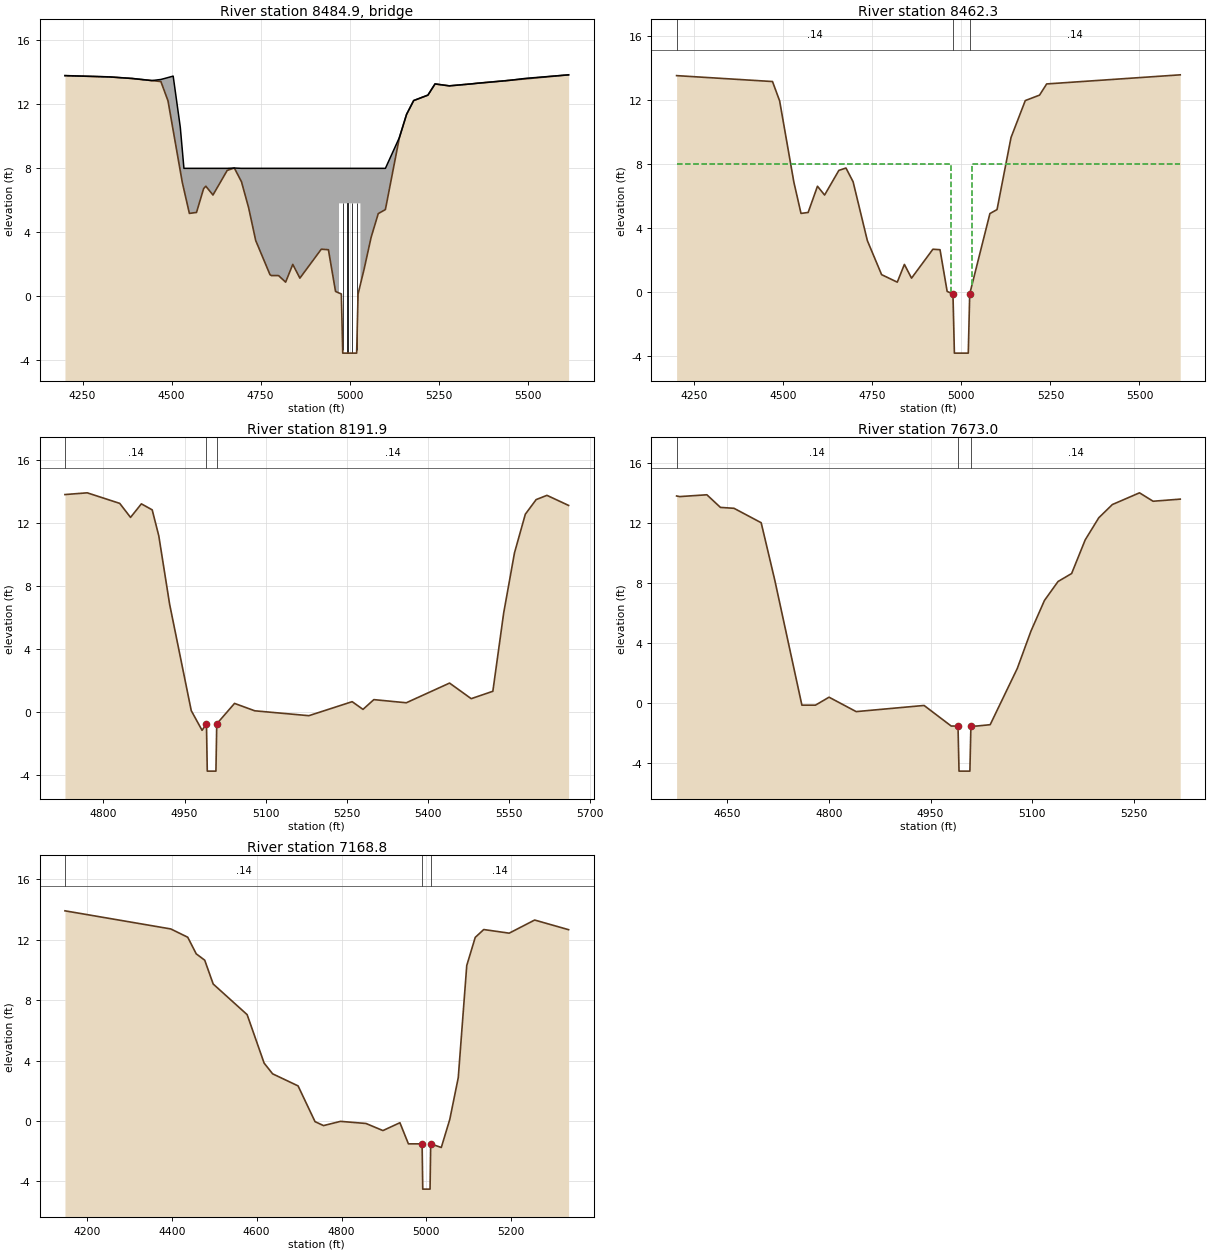
Type RM Length L Ch R = 3 ,8484.9,,,
BEGIN DESCRIPTION:
BURNT MILL CREEK RD-TOR
Structure ID: 125
Approximate Survey Structure
END DESCRIPTION:
Bridge Culvert--1,0,-1,-1, 0
Deck Dist Width WeirC Skew NumUp NumDn MinLoCord MaxHiCord MaxSubmerge Is_Ogee
10,25.3,2.6,,59,59,,,0.95,0,1,1,,
  4200.8  4325.4    4390  4444.5    4470    4490  4504.5  4524.5    4530  4534.7
    4550    4570    4590  4596.2  4616.2  4656.2  4676.2  4696.2  4716.2  4736.2
  4776.2  4780.2  4800.2  4820.2  4840.2  4860.2  4920.2  4940.2  4960.2 4969.91
    4970  4973.7  4976.5  4980.5    5000  5019.5  5023.5  5026.2 5029.89    5030
  5040.2  5060.2  5080.2  5100.2  5139.5  5159.5  5179.5  5219.5  5239.5  5279.5
  5344.9  5356.8  5376.8  5396.8  5416.8  5436.8  5454.4  5494.4  5614.4
    13.8   13.72   13.62   13.49   13.56   13.68   13.77   10.57    9.18       8
       8       8       8       8       8       8    8.02       8       8       8
       8       8       8       8       8       8       8       8       8       8
       8       8       8       8       8       8       8       8       8       8
       8       8       8       8    9.93   11.37   12.24   12.58   13.28   13.16
   13.29   13.32   13.36    13.4   13.44   13.48   13.52   13.63   13.85
    13.8   13.72   13.62   13.49   13.43   12.22   10.37    7.83    7.13    6.67
    5.18    5.24    6.73    6.88    6.33    7.87    8.02    7.16    5.54    3.48
    1.35    1.29    1.29    0.88    1.99    1.13    2.94    2.91     0.3     0.2
    5.81    5.81    5.81    5.81    5.81    5.81    5.81    5.81    5.81    0.74
    1.67    3.69    5.17    5.42    9.93   11.37   12.24   12.58   13.28   13.16
   13.29   13.32   13.36    13.4   13.44   13.48   13.52    13.6   13.85
  4200.8  4325.4    4390  4444.5    4470    4490  4504.5  4524.5    4530  4534.7
    4550    4570    4590  4596.2  4616.2  4656.2  4676.2  4696.2  4716.2  4736.2
  4776.2  4780.2  4800.2  4820.2  4840.2  4860.2  4920.2  4940.2  4960.2 4969.91
    4970  4973.7  4976.5  4980.5    5000  5019.5  5023.5  5026.2 5029.89    5030
  5040.2  5060.2  5080.2  5100.2  5139.5  5159.5  5179.5  5219.5  5239.5  5279.5
  5344.9  5356.8  5376.8  5396.8  5416.8  5436.8  5454.4  5494.4  5614.4
   13.79   13.72   13.62   13.49   13.56   13.68   13.77   10.57    9.18       8
       8       8       8       8       8       8    8.02       8       8       8
       8       8       8       8       8       8       8       8       8       8
       8       8       8       8       8       8       8       8       8       8
       8       8       8       8    9.93   11.37   12.24   12.58   13.28   13.16
   13.29   13.32   13.36    13.4   13.44   13.48   13.52   13.63   13.84
   13.54   13.46   13.36   13.23   13.17   11.96   10.11    7.57    6.87    6.41
    4.92    4.98    6.47    6.62    6.07    7.61    7.76     6.9    5.28    3.22
    1.09    1.03    1.03    0.62    1.73    0.87    2.68    2.65    0.04   -0.06
    5.55    5.55    5.55    5.55    5.55    5.55    5.55    5.55    5.55    0.48
    1.41    3.43    4.91    5.16    9.67   11.11   11.98   12.32   13.02    12.9
   13.03   13.06    13.1   13.14   13.18   13.22   13.26   13.34   13.59
Pier Skew, UpSta & Num, DnSta & Num=,4980.3, 2 ,4980.3, 2 , 0 , 0 , 0 ,,
       1       1
   -4.56    6.81
       1       1
   -4.82    6.55
Pier Skew, UpSta & Num, DnSta & Num=,4993.4, 2 ,4993.4, 2 , 0 , 0 , 0 ,,
       1       1
   -4.56    6.81
       1       1
   -4.82    6.55
Pier Skew, UpSta & Num, DnSta & Num=,5006.5, 2 ,5006.5, 2 , 0 , 0 , 0 ,,
       1       1
   -4.56    6.81
       1       1
   -4.82    6.55
Pier Skew, UpSta & Num, DnSta & Num=,5019.7, 2 ,5019.7, 2 , 0 , 0 , 0 ,,
       1       1
   -4.56    6.81
       1       1
   -4.82    6.55
Abutment Skew #Up #Dn=, 2 , 2
 4969.80 4973.70
    5.81    0.17
 4969.80 4973.70
    5.55   -0.09
Abutment Skew #Up #Dn=, 2 , 2
 5026.20 5030.09
    0.39    5.81
 5026.20 5030.09
    0.13    5.55
BR Coef= 1 , 1 , 0 ,1.25, 0 ,,,0.8,0,2,0,
Wspro=,,,, 1 ,,,, 0 ,,,, 0 ,,,,-1 ,-1 ,-1 , 0 , 0 , 0 , 0 , 0
BC Design=,, 0 ,, 0 ,,,,,,
BR U #Sta/Elev= 59
  4200.8    13.8  4325.4   13.72    4390   13.62  4444.5   13.49    4470   13.43
    4490   12.22  4504.5   10.37  4524.5    7.83    4530    7.13  4534.7    6.67
    4550    5.18    4570    5.24    4590    6.73  4596.2    6.88  4616.2    6.33
  4656.2    7.87  4676.2    8.02  4696.2    7.16  4716.2    5.54  4736.2    3.48
  4776.2    1.35  4780.2    1.29  4800.2    1.29  4820.2    0.88  4840.2    1.99
  4860.2    1.13  4920.2    2.94  4940.2    2.91  4960.2     0.3 4969.91     0.2
    4970     0.2  4973.7    0.17  4976.5    0.14  4980.5   -3.56    5000   -3.56
  5019.5   -3.56  5023.5    0.14  5026.2    0.39 5029.89    0.73    5030    0.74
  5040.2    1.67  5060.2    3.69  5080.2    5.17  5100.2    5.42  5139.5    9.93
  5159.5   11.37  5179.5   12.24  5219.5   12.58  5239.5   13.28  5279.5   13.16
  5344.9   13.29  5356.8   13.32  5376.8   13.36  5396.8    13.4  5416.8   13.44
  5436.8   13.48  5454.4   13.52  5494.4    13.6  5614.4   13.85
BR U #Mann= 3
 4200.80    0.14  4976.5   0.045  5023.5    0.14
BR U Banks=4976.50,5023.50
BR D #Sta/Elev= 59
  4200.8   13.54  4325.4   13.46    4390   13.36  4444.5   13.23    4470   13.17
    4490   11.96  4504.5   10.11  4524.5    7.57    4530    6.87  4534.7    6.41
    4550    4.92    4570    4.98    4590    6.47  4596.2    6.62  4616.2    6.07
  4656.2    7.61  4676.2    7.76  4696.2     6.9  4716.2    5.28  4736.2    3.22
  4776.2    1.09  4780.2    1.03  4800.2    1.03  4820.2    0.62  4840.2    1.73
  4860.2    0.87  4920.2    2.68  4940.2    2.65  4960.2    0.04 4969.91   -0.06
    4970   -0.06  4973.7   -0.09  4976.5   -0.12  4980.5   -3.82    5000   -3.82
  5019.5   -3.82  5023.5   -0.12  5026.2    0.13 5029.89    0.47    5030    0.48
  5040.2    1.41  5060.2    3.43  5080.2    4.91  5100.2    5.16  5139.5    9.67
  5159.5   11.11  5179.5   11.98  5219.5   12.32  5239.5   13.02  5279.5    12.9
  5344.9   13.03  5356.8   13.06  5376.8    13.1  5396.8   13.14  5416.8   13.18
  5436.8   13.22  5454.4   13.26  5494.4   13.34  5614.4   13.59
BR D #Mann= 3
 4200.80    0.14  4976.5   0.045  5023.5    0.14
BR D Banks=4976.50,5023.50

Type RM Length L Ch R = 1 ,8462.3,270.35,270.35,270.35
XS GIS Cut Line= 5
 2743217.0666994 869541.33629032 2743073.4199570 869229.06076326
  2742807.985759 869101.02779716 2742230.2760339 868948.01278889
 2742130.3478652 869094.78228662
BEGIN DESCRIPTION:
Downstream Section of Bridge/Culvert/Weir
END DESCRIPTION:
#Sta/Elev= 30
  4200.8   13.55    4470   13.18    4490   11.97    4530    6.88    4550    4.93
    4570    4.99  4596.2    6.63  4616.2    6.08  4656.2    7.62  4676.2    7.77
  4696.2    6.91  4736.2    3.23  4776.2     1.1  4820.2    0.63  4840.2    1.74
  4860.2    0.88  4920.2    2.69  4940.2    2.66  4960.2    0.05  4976.5   -0.11
  4980.5   -3.81  5019.5   -3.81  5023.5   -0.11  5080.2    4.92  5100.2    5.17
  5139.5    9.68  5179.5   11.99  5219.5   12.33  5239.5   13.03  5614.4    13.6
#Mann= 3 , 1 , 0
 4200.80    0.14       0  4976.5   0.045       0  5023.5    0.14       0
#XS Ineff= 2 , 0
       0 4969.83       8 5030.17       0       8
Bank Sta=4976.50,5023.50
Exp/Cntr=0.5,0.3

Type RM Length L Ch R = 1 ,8191.9,518.9,518.9,518.9
XS GIS Cut Line= 4
 2743008.7157760 868993.31502951 2742893.1738310 868880.89583977
 2742721.4222911 868868.40481868 2742171.8173635 868634.19817338
BEGIN DESCRIPTION:
BETHEL CREEK 3.0
END DESCRIPTION:
#Sta/Elev= 30
    4729   13.79  4770.2    13.9  4830.2   13.23  4850.2   12.34  4870.2    13.2
  4890.2   12.82  4902.4   11.17  4922.4    6.83  4962.4    0.07  4982.4   -1.18
  4990.5   -0.77    4992   -3.77    5008   -3.77  5009.5   -0.77  5042.4    0.53
  5079.8    0.06  5179.8   -0.25  5259.8    0.64  5279.8    0.15  5299.8    0.77
  5359.8    0.57  5439.8    1.82  5479.8    0.83  5519.8     1.3  5539.8    6.27
  5559.8   10.09  5579.8   12.54  5599.8   13.47  5619.8   13.74  5659.8    13.1
#Mann= 3 , 1 , 0
 4729.00    0.14       0  4990.5   0.045       0  5009.5    0.14       0
Bank Sta=4990.50,5009.50
Exp/Cntr=0.3,0.1

Type RM Length L Ch R = 1 ,7673.0,504.2,504.2,504.2
XS GIS Cut Line= 3
 2743077.4163920 868999.56054005 2742971.2427128 868609.21613122
 2743036.8205735 868278.20407253
BEGIN DESCRIPTION:
BETHEL CREEK 2.0
END DESCRIPTION:
#Sta/Elev= 30
  4575.9    13.8  4580.5   13.76  4620.5   13.88  4640.5   13.04  4660.5   12.98
  4700.5   12.02  4720.5    8.21  4760.5   -0.12  4780.5   -0.12  4800.5    0.41
  4840.5   -0.55  4940.5   -0.14  4980.5   -1.51  4990.5   -1.51    4992   -4.51
    5008   -4.51  5009.5   -1.51  5017.9   -1.51  5037.9   -1.42  5077.9    2.33
  5097.9     4.8  5117.9    6.85  5137.9    8.11  5157.9    8.64  5177.9   10.88
  5197.9   12.35  5217.9   13.23  5257.9   14.01  5277.9   13.45  5317.9   13.59
#Mann= 3 , 1 , 0
 4575.90    0.14       0  4990.5   0.045       0  5009.5    0.14       0
Bank Sta=4990.50,5009.50
Exp/Cntr=0.3,0.1

Type RM Length L Ch R = 1 ,7168.8,0,0,0
XS GIS Cut Line= 3
 2743598.9165222 869140.08452723 2743339.7278347 868331.29091213
 2743077.4163920 868118.94355372
BEGIN DESCRIPTION:
BETHEL CREEK 1.0
END DESCRIPTION:
#Sta/Elev= 30
  4148.3   13.92  4397.6   12.72  4437.6   12.17  4457.6   11.07  4477.6   10.65
  4497.6    9.07  4577.6    7.04  4617.6    3.83  4637.6    3.12  4697.6    2.32
  4737.6   -0.05  4757.6   -0.31  4797.6   -0.03  4857.6   -0.17  4897.6   -0.64
  4937.6   -0.12  4957.6   -1.52  4989.9   -1.52  4991.4   -4.52  5008.6   -4.52
  5010.1   -1.52  5035.1   -1.76  5055.1     0.1  5075.1    2.87  5095.1    10.3
  5115.1   12.16  5135.1   12.68  5195.1   12.44  5255.1   13.31  5335.1   12.67
#Mann= 3 , 1 , 0
 4148.30    0.14       0  4989.9   0.045       0  5010.1    0.14       0
Bank Sta=4989.90,5010.10
Exp/Cntr=0.3,0.1

Chan Stop Cuts=-1