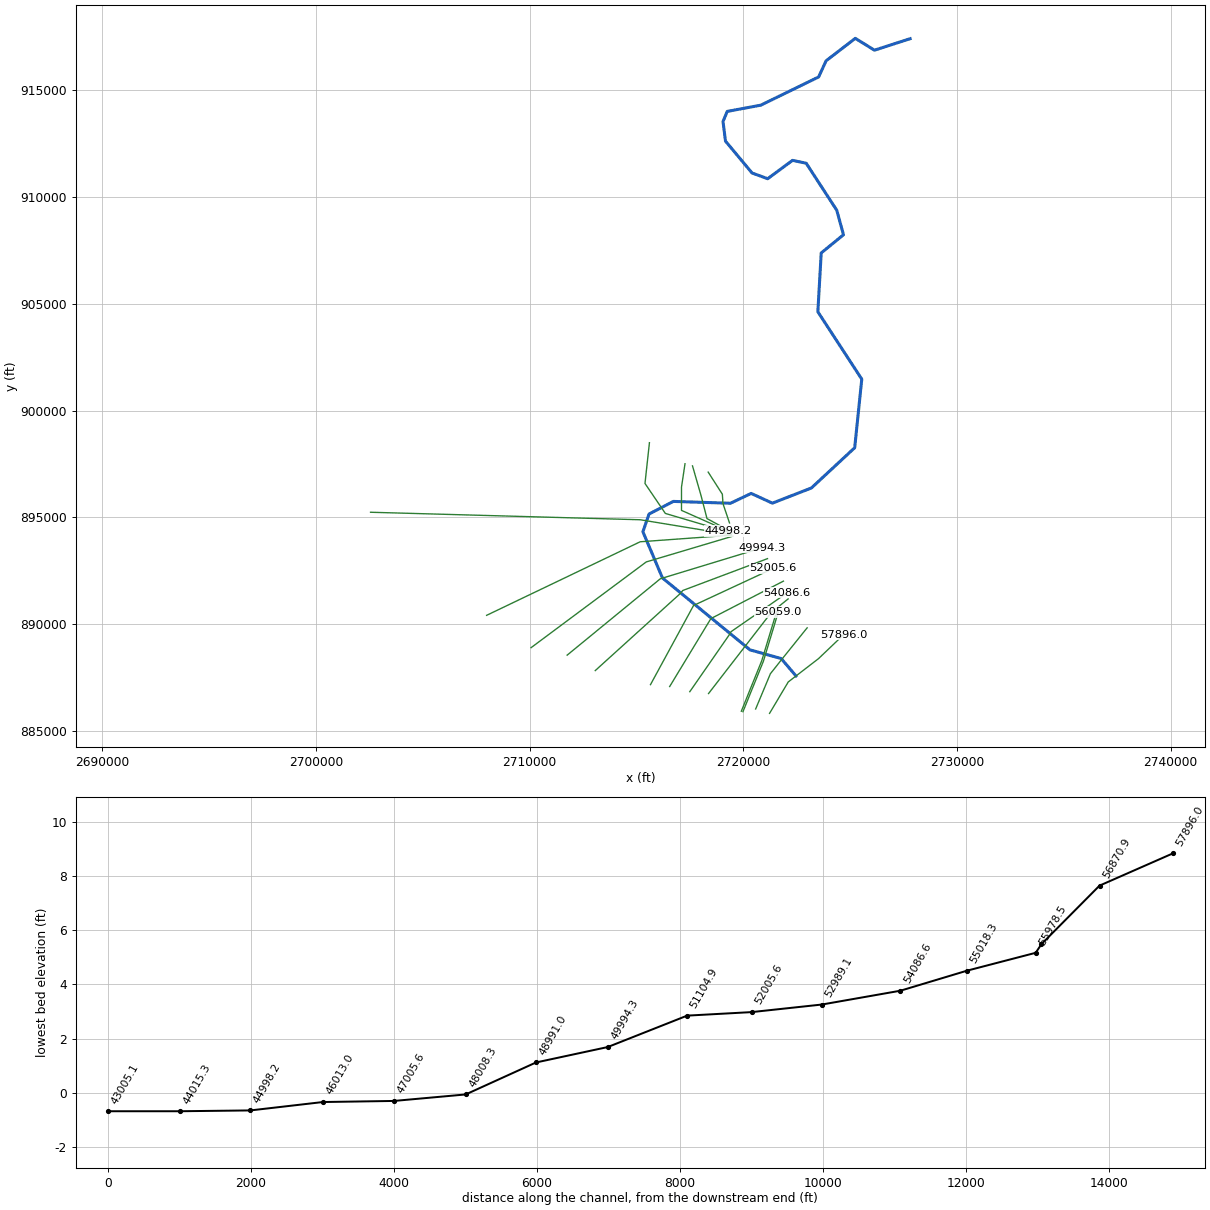
--- GOODWIN MILL CREEK.PRJ (project) ---

Proj Title=Goodwin Mill Creek
Current Plan=p01
Default Exp/Contr=.3,.1
English Units
Geom File=g01
Flow File=f01
Plan File=p01
Y Axis Title=Elevation
X Axis Title(PF)=Main Channel Distance
X Axis Title(XS)=Station
BEGIN DESCRIPTION:
####(Watershed Name)####
GOODWIN MILL CREEK
HCFCD Unit X###-##-##
(Flood Hazard, Floodway) Model
10, 2, 1, 0.2% Event
Filename:  N:\NC_flood\60227\Baker\ENG\Goodwin Mill Creek Basin\Goodwin Mill Creek.prj
Prepared by:  ________     Date: ________
Reviewed by:  ________     Date: ________
STATUS (Draft RAS, SVSQ, FINAL)
END DESCRIPTION:
DSS Export Rating Curves= 0
DSS Export Rating Curve Sorted= 0
DSS Export Volume Flow Curves= 0
DXF OffsetX= 0
DXF OffsetY= 0
DXF ScaleX= 1
DXF ScaleY= 10

--- GOODWIN MILL CREEK.p01 (plan) ---

Plan Title=100 Year Single
Version=Version 3.0.1  Mar 2001
Short Identifier=Plan01
Geom File=g01
Flow File=f01
Subcritical Flow
K Sum by GR= 0
Std Step Tol= 0.01
Critical Tol= 0.01
Num of Std Step Trials= 20
Max Error Tol= 0.3
Flow Tol Ratio= 0.001
Split Flow NTrial= 30
Split Flow Tol= 0.02
Split Flow Ratio= 0.02
Log Output Level= 0
Friction Slope Method= 1
Unsteady Friction Slope Method= 2
Parabolic Critical Depth
Global Vel Dist= 0 , 0 , 0
Global Log Level= 0
CheckData=True
Encroach Param=-1 ,0,0, 2
Encroach River=Goodwin Mill Cre
Encroach Reach=Reach - 1
Encroach Node=57896.0
       1    4700    5500
Encroach Node=56870.9
       1    4663    5400
Encroach Node=56059.0
       1    4646    5481
Encroach Node=56018.7
       4     .75
Encroach Node=55978.5
       1    4646    5481
Encroach Node=55018.3
       1 4956.87 5818.04
Encroach Node=54086.6
       1 4479.76 5630.46
Encroach Node=52989.1
       1 4386.56 6234.39
Encroach Node=52005.6
       1 3975.59  5975.7
Encroach Node=51104.9
       1 3095.16  5561.6
Encroach Node=49994.3
       1 2759.85 5793.94
Encroach Node=48991.0
       1  2150.6  5779.9
Encroach Node=48008.3
       1  1116.9 5584.08
Encroach Node=47005.6
       1   -1686    7752
Encroach Node=46013.0
       1 4157.12  5741.4
Encroach Node=44998.2
       1  4797.6 5375.46
Encroach Node=44015.3
       1 4833.28  5098.5
Encroach Node=43005.1
       1 4838.76 5118.22
Encroach Node=41928.2
       1 4801.07  5221.6
Encroach Node=41905.2
       1 4801.07  5221.6
Encroach Node=41882.2
       1 4801.07  5221.6
Encroach Node=41166.8
       1  4875.7 5083.07
Encroach Node=41141.6
       1  4875.7 5083.07
Encroach Node=41116.5
       1  4875.7 5083.07
Encroach Node=40006.4
       1 4910.46  5177.6
Encroach Node=38980.6
       1 4923.38 5199.13
Encroach Node=37976.7
       1 4829.99 5289.35
Encroach Node=37026.8
       1 4693.34 5137.89
Encroach Node=36008.4
       1  4587.9 5072.89
Encroach Node=35066.1
       1 4660.38 5109.66
Encroach Node=34048.6
       1 4872.41 5669.71
Encroach Node=32991.9
       1 4796.35 5331.66
Encroach Node=31976.8
       1 4834.62 5298.43
Encroach Node=31671.4
       1    4947    5049
Encroach Node=31646.0
       1    4947    5049
Encroach Node=31620.7
       1    4947    5049
Encroach Node=30995.2
       1  4765.5 5218.94
Encroach Node=29994.7
       1 4702.95 5270.18
Encroach Node=28997.0
       1 4845.71 5308.48
Encroach Node=27922.9
       1 4834.54 5278.21
Encroach Node=26992.5
       1 4764.11 5438.54
Encroach Node=26002.8
       1 4841.52 5373.57
Encroach Node=25019.8
       1  4762.2 5184.74
Encroach Node=23998.9
       1 4871.36 5232.87
Encroach Node=22996.5
       1 4801.33 5295.96
Encroach Node=21991.6
       1 4912.53 5329.92
Encroach Node=21000.3
       1 4821.95  5238.8
Encroach Node=19992.1
       1 4786.03 5430.45
Encroach Node=18999.2
       1 4348.65 5316.99
Encroach Node=18010.2
       1  4540.3 5586.31
Encroach Node=16996.4
       1 4665.66 5741.38
Encroach Node=16001.5
       1 4500.58 5459.42
Encroach Node=14996.6
       1 4133.26 5550.94
Encroach Node=13998.1
       1 4609.75 5529.72
Encroach Node=12993.0
       1 4374.95 5369.07
Encroach Node=12001.5
       1 4328.98    5315
Encroach Node=11036.1
       1 4121.78 5535.21
Encroach Node=10138.1
       1 4603.72  5812.4
Encroach Node=9600.1
       1  4951.5  5048.5
Encroach Node=9570.7
       1  4951.5  5048.5
Encroach Node=9541.3
       1  4951.5  5048.5
Encroach Node=8990.0
       1  4786.8 5402.25
Encroach Node=7994.5
       1 4639.57 5342.46
Encroach Node=6999.5
       1 4306.94  5070.5
Encroach Node=6000.0
       1 4637.25 5166.63
Encroach Node=5009.4
       1 4708.64 5351.48
Encroach Node=4004.2
       1 4503.87 5583.95
Encroach Node=2997.9
       1 4331.78 5764.58
Encroach Node=2006.1
       1 4087.64 6169.31
Computation Interval=1HOUR
Output Interval=1HOUR
Run HTab= 0
Run UNet= 0
Run PostProcess= 0
UNET Theta= 1
UNET ZTol= 0.02
UNET ZSATol= 0.1
UNET MxIter= 20
UNET MaxInSteps= 20
UNET DtIC= 0
UNET DtMin= 0
UNET MaxCRTS= 20
UNET WFStab= 2
UNET SFStab= 1
UNET WFX= 1
UNET SFX= 1
UNET Convert EG Bridges=-1
UNET Use Existing IB Tables=-1
Instantaneous Interval=1HOUR
Write IC File= 0
Write Velocity= 0
Write Detailed= 0

--- Goodwin Mill Creek.f01 (steady flow) ---

Flow Title= 100 Year Single
Version=Version 3.0.1  Mar 2001
Number of Profiles= 2
Profile Names=100-Year,Floodway
River Rch & RM=Goodwin Mill Cre,Reach - 1       ,57896.0
     490     490
River Rch & RM=Goodwin Mill Cre,Reach - 1       ,56870.9
     696     696
River Rch & RM=Goodwin Mill Cre,Reach - 1       ,52989.1
     841     841
River Rch & RM=Goodwin Mill Cre,Reach - 1       ,51104.9
     993     993
River Rch & RM=Goodwin Mill Cre,Reach - 1       ,47005.6
    1269    1269
River Rch & RM=Goodwin Mill Cre,Reach - 1       ,46013
    1998    1998
River Rch & RM=Goodwin Mill Cre,Reach - 1       ,43005.1
    2052    2052
River Rch & RM=Goodwin Mill Cre,Reach - 1       ,37976.7
    2496    2496
River Rch & RM=Goodwin Mill Cre,Reach - 1       ,32991.9
    2587    2587
River Rch & RM=Goodwin Mill Cre,Reach - 1       ,28997
    2651    2651
River Rch & RM=Goodwin Mill Cre,Reach - 1       ,26992.5
    2718    2718
River Rch & RM=Goodwin Mill Cre,Reach - 1       ,23998.9
    2780    2780
River Rch & RM=Goodwin Mill Cre,Reach - 1       ,21991.6
    2851    2851
River Rch & RM=Goodwin Mill Cre,Reach - 1       ,13998.1
    3097    3097
River Rch & RM=Goodwin Mill Cre,Reach - 1       ,12993
    3217    3217
River Rch & RM=Goodwin Mill Cre,Reach - 1       ,5009.4
    3355    3355
Boundary for River Rch & Prof#=Goodwin Mill Cre,Reach - 1       , 1
Up Type= 0
Dn Type= 3
Dn Slope=.00006
Boundary for River Rch & Prof#=Goodwin Mill Cre,Reach - 1       , 2
Up Type= 0
Dn Type= 1
Dn Known WS=5.44
DSS Import GetInterval= 0
DSS Import GetPeak= 0
DSS Import FillOption= 0

--- Goodwin Mill Creek.f02 (steady flow) ---

Flow Title=100 Year Single
Version=Version 3.0.1  Mar 2001
Number of Profiles= 2
Profile Names=100-Year,PF 2
River Rch & RM=Goodwin Mill Cre,Reach - 1       ,59083.4
     490     490
River Rch & RM=Goodwin Mill Cre,Reach - 1       ,56870.9
     696     696
River Rch & RM=Goodwin Mill Cre,Reach - 1       ,52989.1
     841     841
River Rch & RM=Goodwin Mill Cre,Reach - 1       ,51104.9
     993     993
River Rch & RM=Goodwin Mill Cre,Reach - 1       ,47005.6
    1269    1269
River Rch & RM=Goodwin Mill Cre,Reach - 1       ,46013
    1998    1998
River Rch & RM=Goodwin Mill Cre,Reach - 1       ,43005.1
    2052    2052
River Rch & RM=Goodwin Mill Cre,Reach - 1       ,37976.7
    2496    2496
River Rch & RM=Goodwin Mill Cre,Reach - 1       ,32991.9
    2587    2587
River Rch & RM=Goodwin Mill Cre,Reach - 1       ,28997
    2651    2651
River Rch & RM=Goodwin Mill Cre,Reach - 1       ,26992.5
    2718    2718
River Rch & RM=Goodwin Mill Cre,Reach - 1       ,23998.9
    2780    2780
River Rch & RM=Goodwin Mill Cre,Reach - 1       ,21991.6
    2851    2851
River Rch & RM=Goodwin Mill Cre,Reach - 1       ,13998.1
    3097    3097
River Rch & RM=Goodwin Mill Cre,Reach - 1       ,12993
    3217    3217
River Rch & RM=Goodwin Mill Cre,Reach - 1       ,5009.4
    3355    3355
Boundary for River Rch & Prof#=Goodwin Mill Cre,Reach - 1       , 1
Up Type= 0
Dn Type= 3
Dn Slope=.005
DSS Import GetInterval= 0
DSS Import GetPeak= 0
DSS Import FillOption= 0

--- GOODWIN MILL CREEK.g01 (geometry) ---

Geom Title=Geom 01 by CodeH2 for Windows

River Reach=Goodwin Mill Cre,Reach - 1
Reach XY= 30
 2722467.2221372 887584.72961483      2721774.28       888398.35
         2720314       888805.13         2716215       892169.69
       2715299.5       894330.44         2715588       895161.19
      2716725.75       895749.88      2719398.75       895663.69
       2720367.5       896123.13         2721361       895668.75
      2723186.75       896377.56      2725214.25       898259.75
       2725545.5       901468.69       2723489.5       904619.06
         2723647       907371.63      2724689.25       908221.81
      2724374.25       909370.88      2722944.25       911568.06
      2722303.75       911703.06      2721141.25       910843.94
       2720408.5       911113.13      2719166.75       912600.94
         2719050       913519.69       2719246.5       913992.88
      2720818.25       914284.38      2723525.25       915604.06
       2723875.5          916360      2725242.75       917410.81
         2726140       916856.19 2727809.5601705 917394.23158439

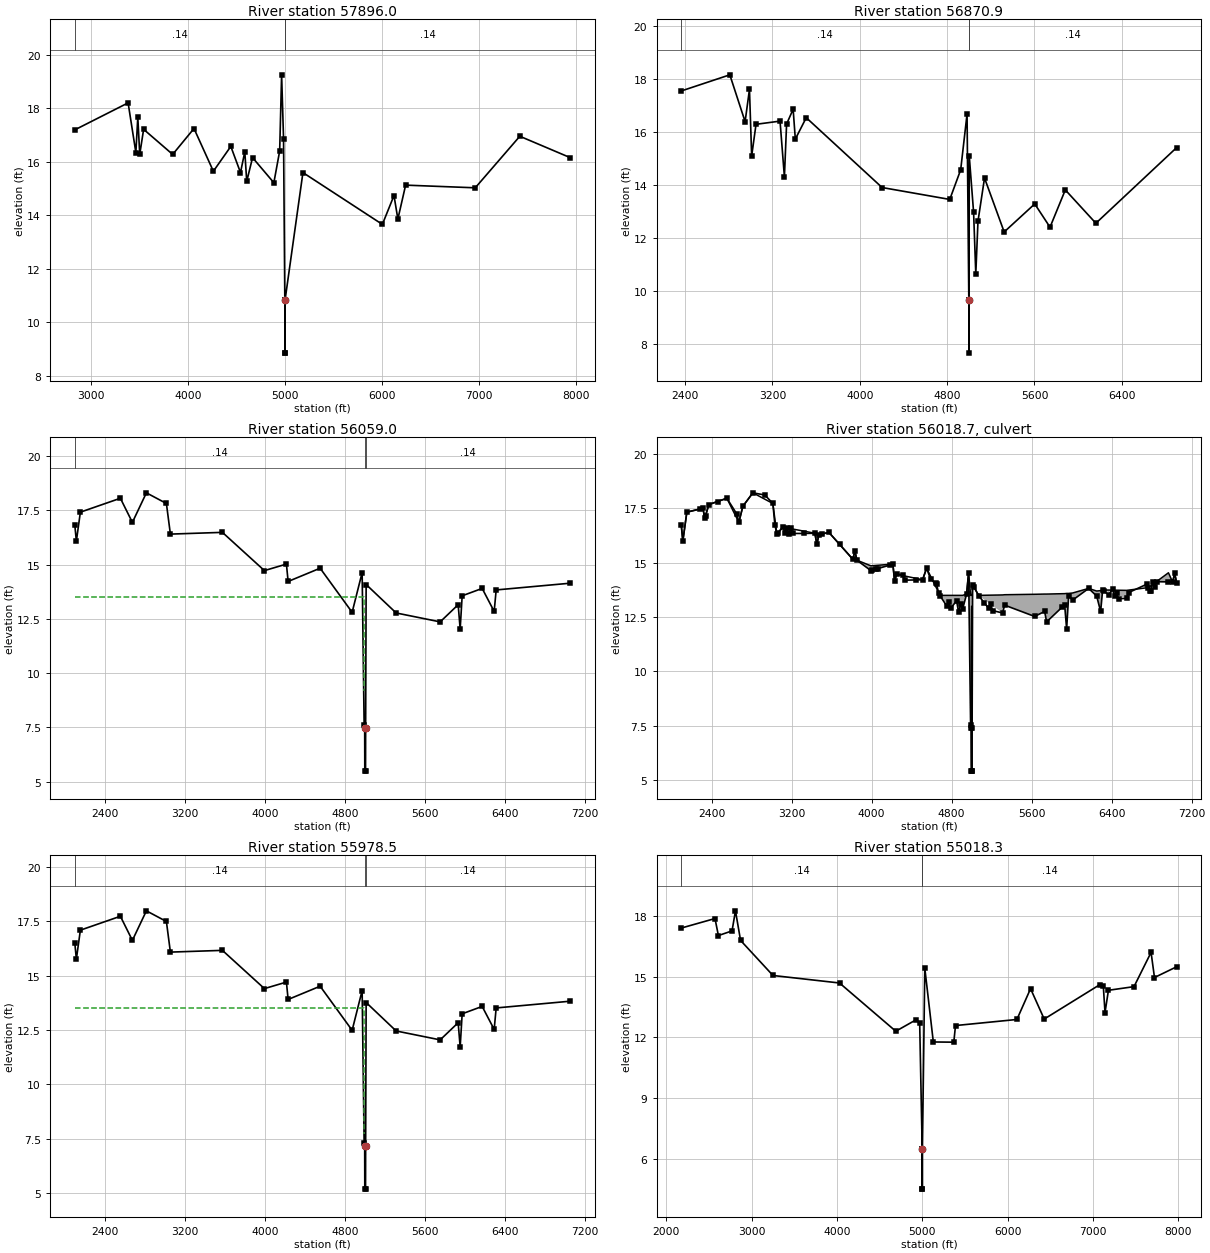
Type RM Length L Ch R = 1 ,57896.0,1025.1,1025.1,1025.1
XS GIS Cut Line= 4
 2721229.0491165 885835.00154039 2722103.5009156 887304.82477723
 2723517.5080802  888393.2381868 2724689.6455982 889509.55963251
BEGIN DESCRIPTION:
Goodwin Mill 58.0
END DESCRIPTION:
#Sta/Elev= 30
  2830.8    17.2    3381   18.21    3461   16.35    3481   17.67    3501   16.28
    3541   17.22    3841   16.28    4061   17.25    4261   15.65    4441   16.58
    4541    15.6  4585.4   16.38  4605.4   15.27  4665.4   16.16  4885.4   15.22
  4945.4   16.41  4965.4   19.26  4985.4   16.87  4998.5   10.84  4999.5    8.84
  5000.5    8.84  5001.5   10.84  5185.4    15.6  6005.4   13.66  6125.4   14.74
  6165.4   13.86  6245.4   15.13  6964.1   15.03  7424.1   16.96  7944.1   16.16
#Mann= 3 , 1 , 0
 2830.80    0.14       0  4998.5   0.045       0  5001.5    0.14       0
Bank Sta=4998.50,5001.50
Exp/Cntr=0.3,0.1

Type RM Length L Ch R = 1 ,56870.9,811.95,811.95,811.95
XS GIS Cut Line= 4
 2720577.8616065  886039.6604721 2721266.2598314 887686.23460452
 2721759.3018032 888309.51407837 2722987.2553935  889835.1533875
BEGIN DESCRIPTION:
Goodwin Mill 57.0
END DESCRIPTION:
#Sta/Elev= 30
  2364.7   17.56  2809.4   18.17  2949.4    16.4  2989.4   17.62  3009.4    15.1
  3049.4    16.3  3269.4   16.42  3309.4   14.31  3329.4   16.31  3389.4   16.87
  3409.4   15.74  3509.4   16.55  4204.1   13.91  4824.1   13.46  4924.1   14.58
  4982.5   16.69  4998.7    9.65  4999.7    7.65  5001.3    9.65  5002.5   15.11
  5042.5   12.97  5062.5   10.64  5082.5   12.63  5142.5   14.27  5322.5   12.23
  5602.5   13.29  5742.5   12.41  5882.5   13.82  6162.5   12.56  6902.5   15.42
#Mann= 3 , 1 , 0
 2364.70    0.14       0  4998.7   0.045       0  5001.3    0.14       0
Bank Sta=4998.70,5001.30
Exp/Cntr=0.3,0.1

Type RM Length L Ch R = 1 ,56059.0,80.5,80.5,80.5
XS GIS Cut Line= 3
 2719984.3031287 885914.28004103 2720938.9442126 888270.67258979
 2721638.2532541 890577.16556878
BEGIN DESCRIPTION:
Upstream Section of Bridge/Culvert/Weir
END DESCRIPTION:
#Sta/Elev= 30
  2097.1   16.81  2112.7   16.08  2152.7   17.41  2552.7   18.05  2672.7   16.94
  2812.7    18.3  3012.7   17.81  3052.7    16.4  3572.7   16.48  3992.7   14.72
  4212.7   15.02  4229.7   14.22  4549.7   14.83  4869.7    12.8  4969.7   14.63
  4989.7    7.62  4995.2    7.49  4996.2    5.49  5003.7    5.49  5004.7    7.49
  5009.7   14.08  5309.7   12.77  5749.7   12.36  5929.7   13.15  5949.7   12.03
  5969.7   13.56  6169.7    13.9  6289.7   12.84  6309.7   13.83  7049.7   14.14
#Mann= 3 , 1 , 0
 2097.10    0.14       0  4995.2   0.045       0  5004.7    0.14       0
#XS Ineff= 2 , 0
       0  4985.2    13.5  5014.7       0    13.5
Bank Sta=4995.20,5004.70
Exp/Cntr=0.5,0.3

Type RM Length L Ch R = 2 ,56018.7,,,
BEGIN DESCRIPTION:
Bear Swamp Rd - TOR
Structure ID: 122
Approximate Survey Structure
END DESCRIPTION:
Bridge Culvert--1,0,-1,-1, 0
Deck Dist Width WeirC Skew NumUp NumDn MinLoCord MaxHiCord MaxSubmerge Is_Ogee
10,60.5,3,, 60, 60,,,0.95,0,1,1,,
  2097.1  2112.7  2152.7  2312.7  2332.7  2372.7  2552.7  2672.7  2712.7  2812.7
  3012.7  3052.7  3112.7  3432.7  3452.7  3472.7  3572.7  3812.7  3832.7  3852.7
  3992.7  4212.7  4229.7  4249.7  4509.7  4549.7  4684.5  4789.7  4849.7  4869.7
  4889.7  4909.7  4949.7  4969.7  4989.7  4995.2  4996.2  5003.7  5004.7  5009.7
  5069.7  5309.7  5329.7  5629.7  5729.7  5749.7  5929.7  5949.7  5969.7  6009.7
  6169.7  6249.7  6289.7  6309.7  6549.7  6767.6  6967.6  7009.7  7029.7  7049.7
   16.73      16   17.33   17.51   17.06   17.68   17.97   16.86    17.6   18.22
   17.73   16.32   16.64   16.36   15.85   16.29    16.4   15.16   15.55   15.12
   14.86   14.94   14.14   14.47   14.22   14.75    13.5    13.5    13.5    13.5
    13.5    13.5   13.56   14.55    13.5    13.5    13.5    13.5    13.5      14
    13.5   13.52   13.53   13.55   13.56   13.56   13.58   13.59   13.59   13.61
   13.82    13.7   13.72   13.75   13.73   13.86   14.54   14.11   14.52   14.06
   16.73      16   17.33   17.51   17.06   17.68   17.97   16.86    17.6   18.22
   17.73   16.32   16.64   16.36   15.85   16.29    16.4   15.16   15.55   15.12
   14.64   14.94   14.14   14.47   14.22   14.75   13.48    12.9   13.25   12.72
    13.1   12.87   13.56   14.55    7.54    7.41    5.41    5.41    7.41      14
   13.49   12.69   13.05   12.53   12.76   12.28   13.07   11.95   13.48   13.28
   13.82   13.47   12.76   13.75   13.36   13.86   14.12   14.11   14.52   14.06
  2097.1  2112.7  2152.7  2312.7  2332.7  2372.7  2552.7  2672.7  2712.7  2812.7
  3012.7  3052.7  3112.7  3432.7  3452.7  3472.7  3572.7  3812.7  3832.7  3852.7
  3992.7  4212.7  4229.7  4249.7  4509.7  4549.7  4684.5  4789.7  4849.7  4869.7
  4889.7  4909.7  4949.7  4969.7  4989.7  4995.2  4996.2  5003.7  5004.7  5009.7
  5169.7  5309.7  5329.7  5629.7  5729.7  5749.7  5929.7  5949.7  5969.7  6009.7
  6169.7  6249.7  6289.7  6309.7  6549.7  6767.6  6967.6  7009.7  7029.7  7049.7
    16.6   15.87    17.2   17.39   16.94   17.56   17.85   16.74   17.48    18.1
   17.61    16.2   16.52   16.24   15.73   16.17   16.28   15.05   15.43   15.01
   14.86   14.82   14.02   14.35    14.1   14.63    13.5    13.5    13.5    13.5
    13.5    13.5    13.5   14.43    13.5    13.5    13.5    13.5    13.5   13.88
   13.51   13.52   13.53   13.55   13.56   13.56   13.58   13.59   13.59   13.61
    13.7    13.7   13.72   13.72   13.73   13.73   14.54   13.98   14.39   13.93
   16.43    15.7   17.03   17.21   16.76   17.38   17.67   16.56    17.3   17.92
   17.43   16.02   16.34   16.06   15.55   15.99    16.1   14.86   15.25   14.82
   14.34   14.64   13.84   14.17   13.92   14.45   13.18    12.6   12.95   12.42
    12.8   12.57   13.26   14.25    7.24    7.11    5.11    5.11    7.11    13.7
   12.61   12.39   12.75   12.23   12.46   11.98   12.77   11.65   13.18   12.98
   13.52   13.17   12.46   13.45   13.06   13.56   13.82   13.81   14.22   13.76
BR Coef= 1 , 0 , 0 ,1.25, 0 ,,,0.8,-1,2,0,
Wspro=,,,, 1 ,,,, 0 ,,,, 0 ,,,,-1 ,-1 ,-1 , 0 , 0 , 0 , 0 , 0
Culvert=1,7.5,,60.5,0.015,0.4,1.0,1,3,5.52,4999.96,5.22,4999.96,Culvert #1  ,0,10
BC Design=,, 0 ,, 0 ,,,,,,
BR U #Sta/Elev= 108
  2097.1   16.73  2112.7      16  2152.7   17.33  2279.6   17.47  2312.7   17.51
  2332.7   17.06  2339.6   17.17  2372.7   17.68  2459.6   17.82  2552.7   17.97
  2652.7   17.24  2672.7   16.86  2712.7    17.6  2812.7   18.22  2932.7   18.12
  3012.7   17.73  3032.7   16.76  3052.7   16.32  3059.6   16.36  3112.7   16.64
  3132.7   16.38  3152.7    16.6  3172.7   16.33  3192.7    16.6  3212.7   16.35
  3319.6   16.35  3432.7   16.36  3452.7   15.85  3472.7   16.29  3499.6   16.32
  3572.7    16.4  3679.6   15.85  3812.7   15.16  3832.7   15.55  3852.7   15.12
  3992.7   14.64  3999.6   14.65  4039.6    14.7  4059.6   14.73  4179.6   14.89
  4212.7   14.94  4229.7   14.14  4249.7   14.47  4309.7   14.46  4329.7    14.2
  4439.6   14.21  4509.7   14.22  4549.7   14.75  4589.7   14.25  4639.6   14.06
  4649.7   14.02  4669.7   13.59  4684.5   13.48  4749.7   13.02  4769.7   13.18
  4789.7    12.9  4849.7   13.25  4869.7   12.72  4889.7    13.1  4909.7   12.87
  4949.7   13.56  4969.7   14.55  4989.7    7.54  4995.2    7.41  4996.2    5.41
    5000    5.41  5003.7    5.41  5004.7    7.41  5009.7      14  5025.1   13.87
  5069.7   13.49  5127.6   13.15  5169.7   12.91  5189.7   13.11  5209.7    12.8
  5309.7   12.69  5329.7   13.05  5629.7   12.53  5729.7   12.76  5749.7   12.28
  5907.6   12.97  5929.7   13.07  5949.7   11.95  5969.7   13.48  6009.7   13.28
  6169.7   13.82  6249.7   13.47  6289.7   12.76  6309.7   13.75  6327.6   13.68
  6369.7   13.53  6409.7   13.79  6429.7   13.46  6449.7   13.62  6469.7   13.35
  6549.7   13.36  6569.7   13.63  6749.7   14.01  6767.6   13.86  6787.6    13.7
  6789.7   13.68  6809.7    14.1  6829.7   13.89  6849.7   14.13  6967.6   14.12
  7009.7   14.11  7029.7   14.52  7049.7   14.06
BR U #Mann= 3
 2097.10    0.14  4995.2   0.045  5004.7    0.14
BR U Banks=4995.20,5004.70
BR D #Sta/Elev= 108
  2097.1   16.43  2112.7    15.7  2152.7   17.03  2279.6   17.17  2312.7   17.21
  2332.7   16.76  2339.6   16.87  2372.7   17.38  2459.6   17.52  2552.7   17.67
  2652.7   16.94  2672.7   16.56  2712.7    17.3  2812.7   17.92  2932.7   17.82
  3012.7   17.43  3032.7   16.46  3052.7   16.02  3059.6   16.06  3112.7   16.34
  3132.7   16.08  3152.7    16.3  3172.7   16.03  3192.7    16.3  3212.7   16.05
  3319.6   16.05  3432.7   16.06  3452.7   15.55  3472.7   15.99  3499.6   16.02
  3572.7    16.1  3679.6   15.55  3812.7   14.86  3832.7   15.25  3852.7   14.82
  3992.7   14.34  3999.6   14.35  4039.6    14.4  4059.6   14.43  4179.6   14.59
  4212.7   14.64  4229.7   13.84  4249.7   14.17  4309.7   14.16  4329.7    13.9
  4439.6   13.91  4509.7   13.92  4549.7   14.45  4589.7   13.95  4639.6   13.76
  4649.7   13.72  4669.7   13.29  4684.5   13.18  4749.7   12.72  4769.7   12.88
  4789.7    12.6  4849.7   12.95  4869.7   12.42  4889.7    12.8  4909.7   12.57
  4949.7   13.26  4969.7   14.25  4989.7    7.24  4995.2    7.11  4996.2    5.11
    5000    5.11  5003.7    5.11  5004.7    7.11  5009.7    13.7  5025.1   13.57
  5069.7   13.19  5127.6   12.85  5169.7   12.61  5189.7   12.81  5209.7    12.5
  5309.7   12.39  5329.7   12.75  5629.7   12.23  5729.7   12.46  5749.7   11.98
  5907.6   12.67  5929.7   12.77  5949.7   11.65  5969.7   13.18  6009.7   12.98
  6169.7   13.52  6249.7   13.17  6289.7   12.46  6309.7   13.45  6327.6   13.38
  6369.7   13.23  6409.7   13.49  6429.7   13.16  6449.7   13.32  6469.7   13.05
  6549.7   13.06  6569.7   13.33  6749.7   13.71  6767.6   13.56  6787.6    13.4
  6789.7   13.38  6809.7    13.8  6829.7   13.59  6849.7   13.83  6967.6   13.82
  7009.7   13.81  7029.7   14.22  7049.7   13.76
BR D #Mann= 3
 2097.10    0.14  4995.2   0.045  5004.7    0.14
BR D Banks=4995.20,5004.70

Type RM Length L Ch R = 1 ,55978.5,960.15,960.15,960.15
XS GIS Cut Line= 3
 2719907.1421653 885937.22422830 2720861.7832492 888293.61677706
 2721561.0922907 890600.10975605
BEGIN DESCRIPTION:
Downstream Section of Bridge/Culvert/Weir
END DESCRIPTION:
#Sta/Elev= 30
  2097.1   16.49  2112.7   15.76  2152.7   17.09  2552.7   17.73  2672.7   16.62
  2812.7   17.98  3012.7   17.49  3052.7   16.08  3572.7   16.16  3992.7    14.4
  4212.7    14.7  4229.7    13.9  4549.7   14.51  4869.7   12.48  4969.7   14.31
  4989.7     7.3  4995.2    7.17  4996.2    5.17  5003.7    5.17  5004.7    7.17
  5009.7   13.76  5309.7   12.45  5749.7   12.04  5929.7   12.83  5949.7   11.71
  5969.7   13.24  6169.7   13.58  6289.7   12.52  6309.7   13.51  7049.7   13.82
#Mann= 3 , 1 , 0
 2097.10    0.14       0  4995.2   0.045       0  5004.7    0.14       0
#XS Ineff= 2 , 0
       0 4988.53    13.5 5011.37       0    13.5
Bank Sta=4995.20,5004.70
Exp/Cntr=0.5,0.3

Type RM Length L Ch R = 1 ,55018.3,931.7,931.7,931.7
XS GIS Cut Line= 3
 2718371.9358100 886762.15345533 2721308.2910753 890553.11958145
 2722097.1626391 891188.59945231
BEGIN DESCRIPTION:
Goodwin Mill 55.0
END DESCRIPTION:
#Sta/Elev= 30
    2174   17.39  2569.2   17.86  2609.2   17.02  2769.2   17.25  2809.2   18.24
  2869.2   16.78  3249.2   15.05  4029.2   14.68  4689.2    12.3  4929.2   12.87
  4969.2    12.7  4998.7    6.51  4999.7    4.51  5000.3    4.51  5001.3    6.51
  5029.2   15.41  5129.2   11.77  5369.2   11.76  5389.2   12.58  6109.2   12.88
  6269.2    14.4  6429.2    12.9  7082.2    14.6  7122.2   14.53  7142.2   13.22
  7182.2   14.32  7482.2    14.5  7682.2   16.19  7722.2   14.95  7982.2   15.48
#Mann= 3 , 1 , 0
 2174.00    0.14       0  4998.7   0.045       0  5001.3    0.14       0
Bank Sta=4998.70,5001.30
Exp/Cntr=0.3,0.1

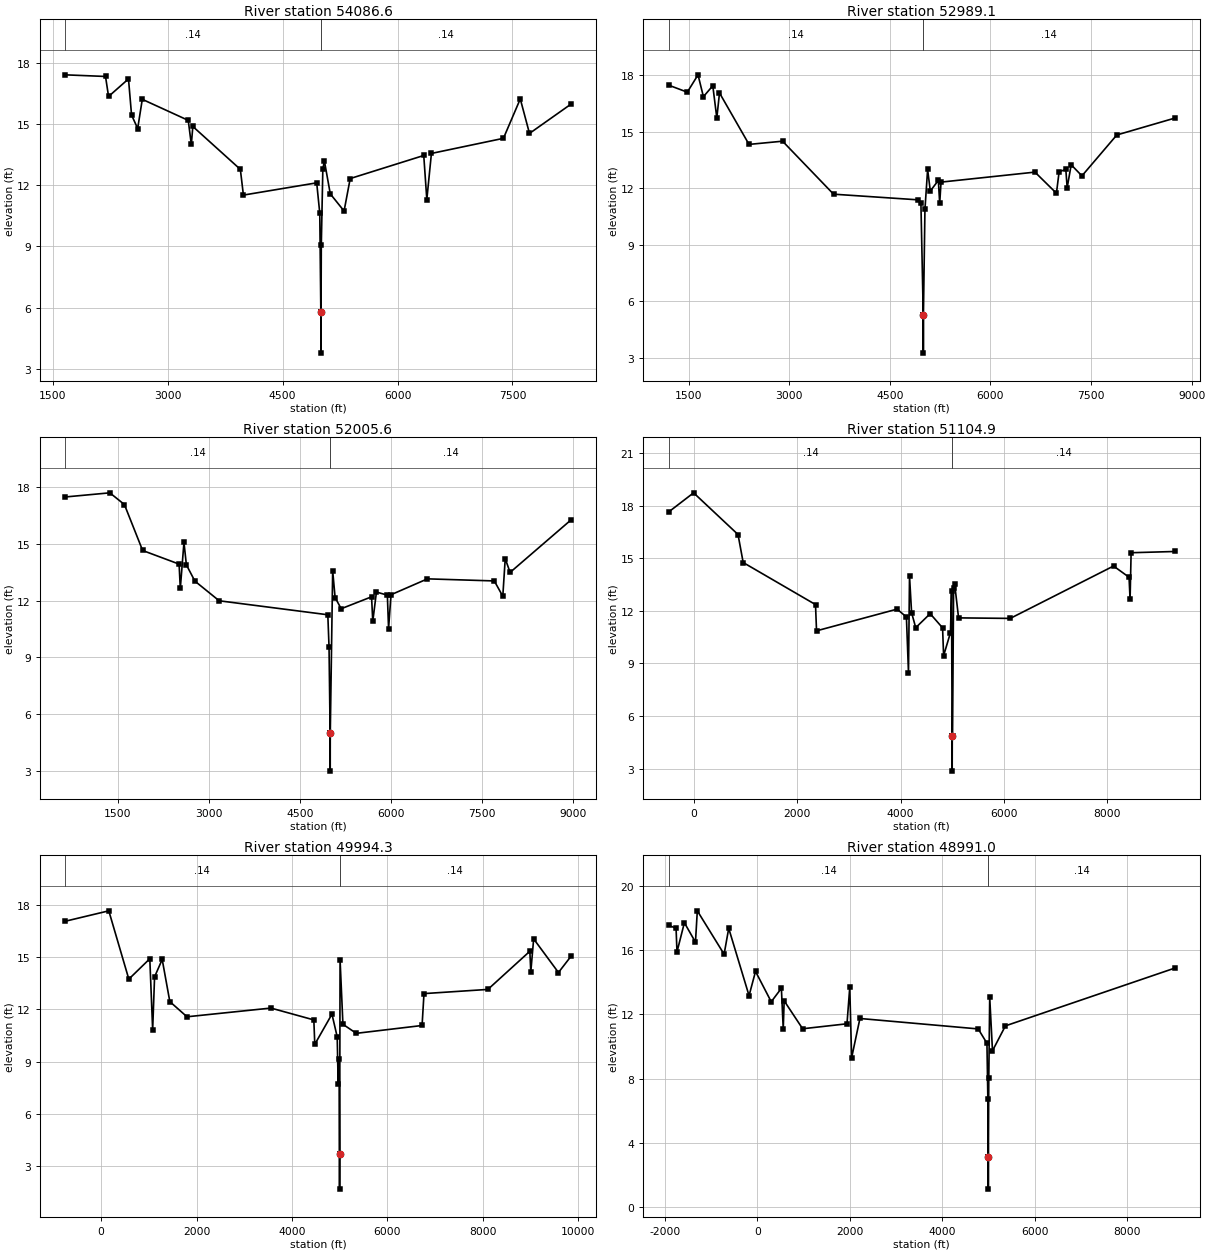
Type RM Length L Ch R = 1 ,54086.6,1097.5,1097.5,1097.5
XS GIS Cut Line= 4
 2717495.4118502  886849.8058513 2719336.1121657  889501.2908297
 2719423.7645617 889654.68252266 2722053.3364411 891473.46973924
BEGIN DESCRIPTION:
Goodwin Mill 54.0
END DESCRIPTION:
#Sta/Elev= 30
  1660.3    17.4    2188   17.32    2228   16.34    2488    17.2    2528   15.43
    2608   14.77    2668    16.2    3268   15.17    3308   13.99    3328   14.87
    3948   12.77    3988   11.51  4944.7   12.11  4984.7   10.62  4998.7    5.77
  4999.7    3.77  5001.3    5.77  5004.7    9.07  5024.7   12.78  5044.7   13.19
    5122   11.57    5302   10.73    5382   12.32    6342   13.45    6382   11.29
    6442   13.55    7382   14.29    7602   16.22    7722   14.53    8262   15.96
#Mann= 3 , 1 , 0
 1660.30    0.14       0  4998.7   0.045       0  5001.3    0.14       0
Bank Sta=4998.70,5001.30
Exp/Cntr=0.3,0.1

Type RM Length L Ch R = 1 ,52989.1,983.5,983.5,983.5
XS GIS Cut Line= 3
 2716553.1485934 887090.84994025 2718481.5013049 890268.24929452
 2721878.0316492 892021.29721412
BEGIN DESCRIPTION:
Goodwin Mill 53.0
END DESCRIPTION:
#Sta/Elev= 30
  1204.8   17.47  1481.5    17.1  1641.5   18.02  1721.5   16.86  1861.5   17.44
  1921.5   15.73  1961.5   17.06  2401.5   14.33  2901.5    14.5  3661.5   11.69
  4921.5   11.39  4963.8    11.2  4998.9    5.26  4999.9    3.26  5001.1    5.26
  5023.8   10.88  5063.8      13  5103.8   11.86  5223.8   12.42  5243.8    11.2
  5263.8   12.33  6663.8   12.86  6983.8   11.74  7023.8   12.88  7123.8      13
  7143.8   12.03  7203.8   13.25  7363.8   12.66  7883.8   14.83  8743.8   15.72
#Mann= 3 , 1 , 0
 1204.80    0.14       0  4998.9   0.045       0  5001.1    0.14       0
Bank Sta=4998.90,5001.10
Exp/Cntr=0.3,0.1

Type RM Length L Ch R = 1 ,52005.6,900.7,900.7,900.7
XS GIS Cut Line= 3
 2715654.7115346 887178.50233623 2717670.7166421 890881.81606638
 2721395.9434713 892612.95088698
BEGIN DESCRIPTION:
Goodwin Mill 52.0
END DESCRIPTION:
#Sta/Elev= 30
   636.4   17.48  1372.9    17.7  1612.9   17.08  1912.9   14.65  2512.9   13.93
  2532.9   12.64  2592.9   15.08  2632.9   13.89  2772.9   13.03  3172.9   11.99
  4960.7   11.25  4980.7    9.55  4998.9    4.98  4999.9    2.98  5001.1    4.98
  5040.7   13.58  5080.7   12.16  5180.7   11.57  5680.7    12.2  5700.7    10.9
  5760.7   12.45  5940.7   12.29  5960.7   10.52  6000.7   12.31  6600.7   13.15
  7700.7   13.04  7840.7   12.23  7880.7   14.22  7960.7   13.49  8960.7   16.26
#Mann= 3 , 1 , 0
  636.40    0.14       0  4998.9   0.045       0  5001.1    0.14       0
Bank Sta=4998.90,5001.10
Exp/Cntr=0.3,0.1

Type RM Length L Ch R = 1 ,51104.9,1110.6,1110.6,1110.6
XS GIS Cut Line= 4
 2713068.9658532 887835.89530608 2717013.3236723 891407.73044226
 2717166.7153652 891583.03523422 2721132.9862833 893073.12596587
BEGIN DESCRIPTION:
Goodwin Mill 51.0
END DESCRIPTION:
#Sta/Elev= 30
  -487.6   17.65    -6.3   18.74   853.7   16.36   953.7   14.76  2353.7   12.36
  2373.7   10.86  3933.7    12.1  4113.7   11.65  4153.7    8.47  4173.7   13.99
  4213.7    11.9  4293.7   11.04  4573.7   11.84  4813.7   11.03  4833.7    9.44
  4966.7   10.76  4986.7   13.12  4998.6    4.85  4999.6    2.85  5001.3    4.85
  5006.7    4.88  5026.7   13.28  5046.7   13.55  5123.6    11.6  6123.6   11.57
  8123.6   14.56  8423.6   13.92  8443.6   12.65  8463.6   15.32  9303.6   15.39
#Mann= 3 , 1 , 0
 -487.60    0.14       0  4998.6   0.045       0  5001.3    0.14       0
Bank Sta=4998.60,5001.30
Exp/Cntr=0.3,0.1

Type RM Length L Ch R = 1 ,49994.3,1003.3,1003.3,1003.3
XS GIS Cut Line= 3
 2711754.1799135 888559.02757291 2716114.8866135 892130.86270909
 2720870.0290954 893577.12724276
BEGIN DESCRIPTION:
Goodwin Mill 50.0
END DESCRIPTION:
#Sta/Elev= 30
  -756.8   17.06     160   17.66     580   13.74    1020   14.91    1080   10.83
    1120   13.87    1280   14.87    1440   12.45    1800   11.58    3560   12.08
    4460    11.4    4480      10    4840   11.73  4950.2   10.43  4970.2    7.71
  4990.2    9.13  4998.7    3.69  4999.7    1.69  5001.4    3.69  5010.2   14.86
  5070.2   11.15  5350.2   10.63  6730.2   11.08  6770.2   12.91  8110.2   13.15
  8990.2   15.34  9010.2   14.15  9070.2   16.05  9590.2   14.12  9850.2   15.04
#Mann= 3 , 1 , 0
 -756.80    0.14       0  4998.7   0.045       0  5001.4    0.14       0
Bank Sta=4998.70,5001.40
Exp/Cntr=0.3,0.1

Type RM Length L Ch R = 1 ,48991.0,982.7,982.7,982.7
XS GIS Cut Line= 3
 2710066.8712909 888909.63715683 2715457.4936436 892919.73427291
 2719511.4169577 894124.95471763
BEGIN DESCRIPTION:
Goodwin Mill 49.0
END DESCRIPTION:
#Sta/Elev= 30
   -1918   17.53 -1759.4   17.36 -1739.4   15.88 -1579.4    17.7 -1339.4   16.49
 -1299.4   18.44  -719.4   15.74  -619.4   17.35  -179.4   13.16   -39.4   14.67
   300.6   12.78   520.6   13.62   560.6   11.08   580.6   12.84   980.6    11.1
  1940.6   11.41  2000.6   13.68  2040.6    9.29  2220.6   11.74  4780.6   11.09
  4969.9    10.2  4989.9     6.7  4998.7    3.12  4999.7    1.12  5001.4    3.12
  5009.9    8.04  5029.9   13.06  5089.9    9.73  5369.9   11.28  9029.9   14.87
#Mann= 3 , 1 , 0
-1918.00    0.14       0  4998.7   0.045       0  5001.4    0.14       0
Bank Sta=4998.70,5001.40
Exp/Cntr=0.3,0.1

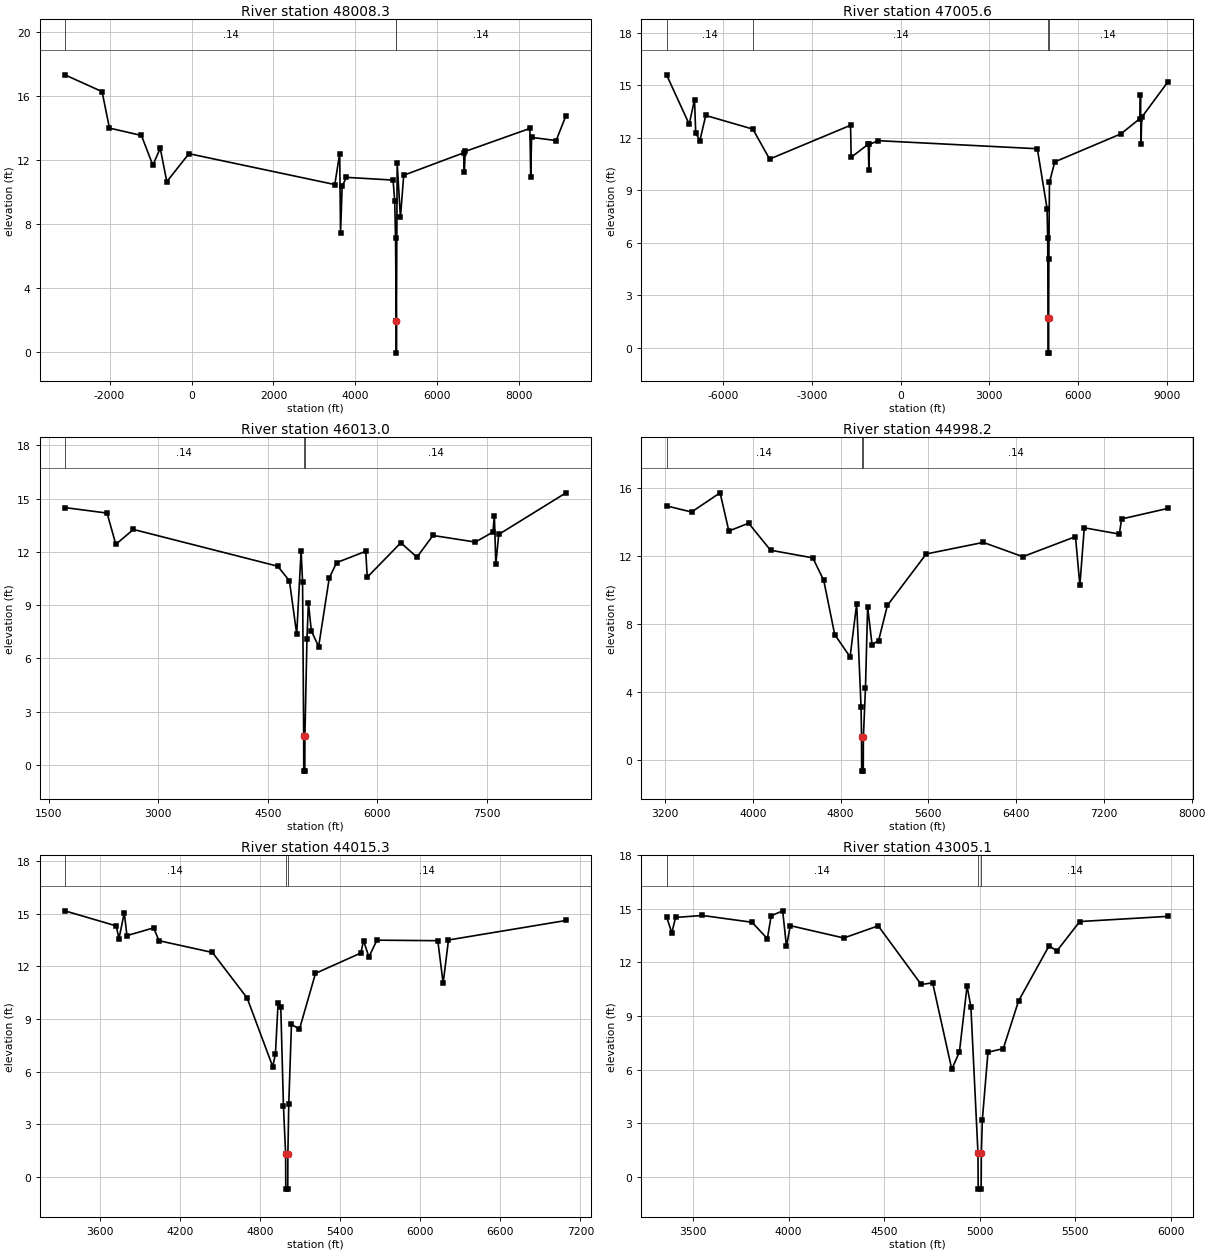
Type RM Length L Ch R = 1 ,48008.3,1002.7,1002.7,1002.7
XS GIS Cut Line= 3
 2707985.1268864 890421.64098748 2715172.6233567 893861.99752969
 2719423.7645617 894168.78091562
BEGIN DESCRIPTION:
Goodwin Mill 48.0
END DESCRIPTION:
#Sta/Elev= 30
 -3091.5   17.34 -2183.1   16.29 -2003.1   14.01 -1223.1   13.55  -943.1   11.69
  -763.1   12.75  -603.1   10.66   -63.1   12.41  3496.9   10.48  3616.9   12.42
  3636.9    7.45  3676.9   10.36  3776.9   10.93  4919.1   10.76  4959.1    9.46
  4979.1    7.15  4998.7    1.94  4999.7   -0.06  5001.4    1.94  5019.1   11.81
  5099.1    8.42  5179.1   11.06  6639.1   12.46  6659.1   11.28  6679.1   12.55
  8259.1   13.99  8279.1   10.98  8299.1   13.43  8899.1   13.23  9139.1   14.79
#Mann= 3 , 1 , 0
-3091.50    0.14       0  4998.7   0.045       0  5001.4    0.14       0
Bank Sta=4998.70,5001.40
Exp/Cntr=0.3,0.1

Type RM Length L Ch R = 1 ,47005.6,992.6,992.6,992.6
XS GIS Cut Line= 3
 2702550.6783356 895242.52276638 2715172.6233567 894891.91318246
 2719445.6776607 894190.69401462
BEGIN DESCRIPTION:
Goodwin Mill 47.0
END DESCRIPTION:
#Sta/Elev= 30
 -7921.4   15.59 -7154.6   12.77 -6974.6   14.17 -6934.6   12.28 -6794.6   11.83
 -6594.6   13.27 -5000.1   12.49 -4434.6   10.78 -1694.6   12.71 -1674.6   10.88
 -1094.6   11.63 -1074.6   10.16 -1054.6   11.62  -754.6   11.83  4625.4   11.37
  4955.6    7.95  4975.6    6.28  4991.6     1.7  4992.6    -0.3  5007.5    -0.3
  5008.5     1.7  5015.6     5.1  5035.6    9.45  5215.6   10.62  7455.6   12.22
  8095.6   13.09  8115.6   14.46  8135.6   11.65  8155.6   13.16  9035.6   15.17
#Mann= 4 , 1 , 0
-7921.40    0.14       0 -5000.1    0.14       0  4991.6   0.045       0
  5008.5    0.14       0
Bank Sta=4991.60,5008.50
Exp/Cntr=0.3,0.1

Type RM Length L Ch R = 1 ,46013.0,1014.8,1014.8,1014.8
XS GIS Cut Line= 4
 2715605.4070619 898496.61796713 2715397.2326214 896590.17835457
 2716350.4524277 895187.74001889 2719462.1124850  894267.3898611
BEGIN DESCRIPTION:
Goodwin Mill 46.0
END DESCRIPTION:
#Sta/Elev= 30
    1723   14.49  2300.8   14.18  2420.8   12.42  2660.8   13.26  4636.5   11.19
  4796.5   10.37  4896.5    7.37  4956.5   12.07  4976.5   10.31  4991.6    1.66
  4992.6   -0.34  5007.5   -0.34  5008.5    1.66  5036.5     7.1  5056.5    9.14
  5096.5    7.55  5196.5    6.67  5341.4   10.52  5441.4   11.39  5841.4   12.03
  5861.4   10.57  6321.4   12.51  6541.4    11.7  6761.4   12.92  7341.4   12.55
  7581.4   13.11  7601.4   14.04  7621.4   11.32  7661.4   12.98  8581.4   15.32
#Mann= 3 , 1 , 0
 1723.00    0.14       0  4991.6   0.045       0  5008.5    0.14       0
Bank Sta=4991.60,5008.50
Exp/Cntr=0.3,0.1

Type RM Length L Ch R = 1 ,44998.2,982.9,982.9,982.9
XS GIS Cut Line= 4
 2717270.8025855 897510.52851236 2717106.4543430 896414.87356261
 2717106.4543430 895330.17516236 2719275.8511435 894365.99880658
BEGIN DESCRIPTION:
Goodwin Mill 45.0
END DESCRIPTION:
#Sta/Elev= 30
  3214.7   14.97  3442.6   14.61  3702.6   15.74  3782.6   13.49  3962.6   13.95
  4162.6   12.36  4547.3   11.91  4647.3   10.58  4747.3    7.39  4887.3    6.08
  4947.3    9.19  4987.3    3.12  4991.6    1.35  4992.6   -0.65  5007.4   -0.65
  5008.4    1.35  5027.3    4.22  5047.3    9.03  5087.3     6.8  5147.3    7.04
  5227.3    9.11  5581.3   12.14  6101.3   12.82  6461.3   11.98  6941.3   13.16
  6981.3   10.29  7021.3   13.68  7341.3   13.31  7361.3    14.2  7781.3   14.82
#Mann= 3 , 1 , 0
 3214.70    0.14       0  4991.6   0.045       0  5008.4    0.14       0
Bank Sta=4991.60,5008.40
Exp/Cntr=0.3,0.1

Type RM Length L Ch R = 1 ,44015.3,1010.2,1010.2,1010.2
XS GIS Cut Line= 4
 2717621.4121694 897411.91956688 2718015.8479513 896042.35087969
 2718300.7182382 894946.69592994 2719352.5469900 894376.95535608
BEGIN DESCRIPTION:
Goodwin Mill 44.0
END DESCRIPTION:
#Sta/Elev= 30
  3337.9   15.16  3723.1    14.3  3743.1   13.57  3783.1   15.05  3803.1   13.75
  4003.1   14.19  4043.1   13.46  4443.1   12.79  4703.1    10.2  4895.2    6.29
  4915.2    7.02  4935.2    9.93  4955.2    9.71  4975.2    4.04  4991.6    1.32
  4992.6   -0.68  5007.5   -0.68  5008.5    1.32  5015.2    4.18  5035.2     8.7
  5095.2    8.42  5215.2    11.6  5555.2   12.76  5575.2   13.47  5615.2   12.53
  5675.2   13.49  6131.4   13.46  6171.4   11.04  6211.4    13.5  7091.4   14.61
#Mann= 3 , 1 , 0
 3337.90    0.14       0  4991.6   0.045       0  5008.5    0.14       0
Bank Sta=4991.60,5008.50
Exp/Cntr=0.3,0.1

Type RM Length L Ch R = 1 ,43005.1,1076.9,1076.9,1076.9
XS GIS Cut Line= 4
 2718356.7483777  897119.4606297 2719019.2431770 896086.21186019
 2719049.6328467 895642.52268269 2719353.5295436 894742.98845983
BEGIN DESCRIPTION:
Goodwin Mill 43.0
END DESCRIPTION:
#Sta/Elev= 30
  3361.9   14.56  3389.3   13.66  3409.3   14.52  3549.3   14.63  3809.3   14.25
  3889.3   13.33  3909.3   14.61  3969.3   14.89  3989.3    12.9  4009.3   14.06
  4289.3   13.37  4469.3   14.05    4694   10.77    4754   10.86    4854    6.03
    4894    6.99    4934   10.68    4954    9.53  4991.2    1.32  4992.2   -0.68
  5007.8   -0.68  5008.8    1.32    5014     3.2  5043.5    6.98  5123.5    7.18
  5203.5    9.85  5363.5   12.94  5403.5   12.64  5523.5   14.29  5983.5   14.58
#Mann= 3 , 1 , 0
 3361.90    0.14       0  4991.2   0.045       0  5008.8    0.14       0
Bank Sta=4991.20,5008.80
Exp/Cntr=0.3,0.1