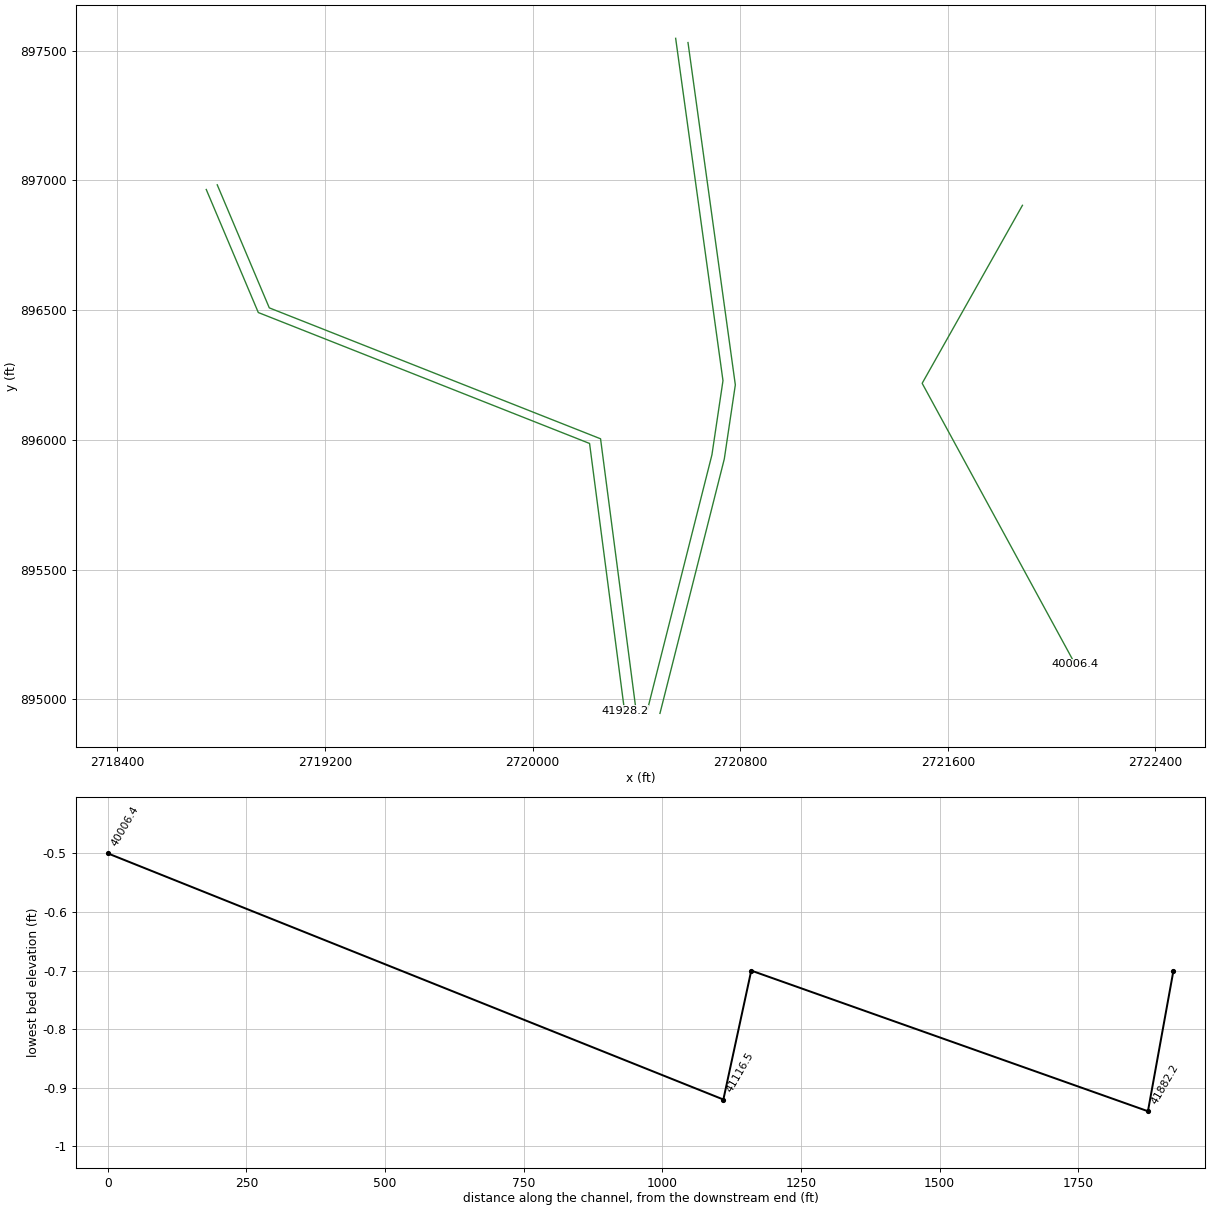
HEC-RAS study GOODWIN MILL CREEK.PRJ: Goodwin Mill Creek

--- GOODWIN MILL CREEK.g01 (geometry) --- (continued)

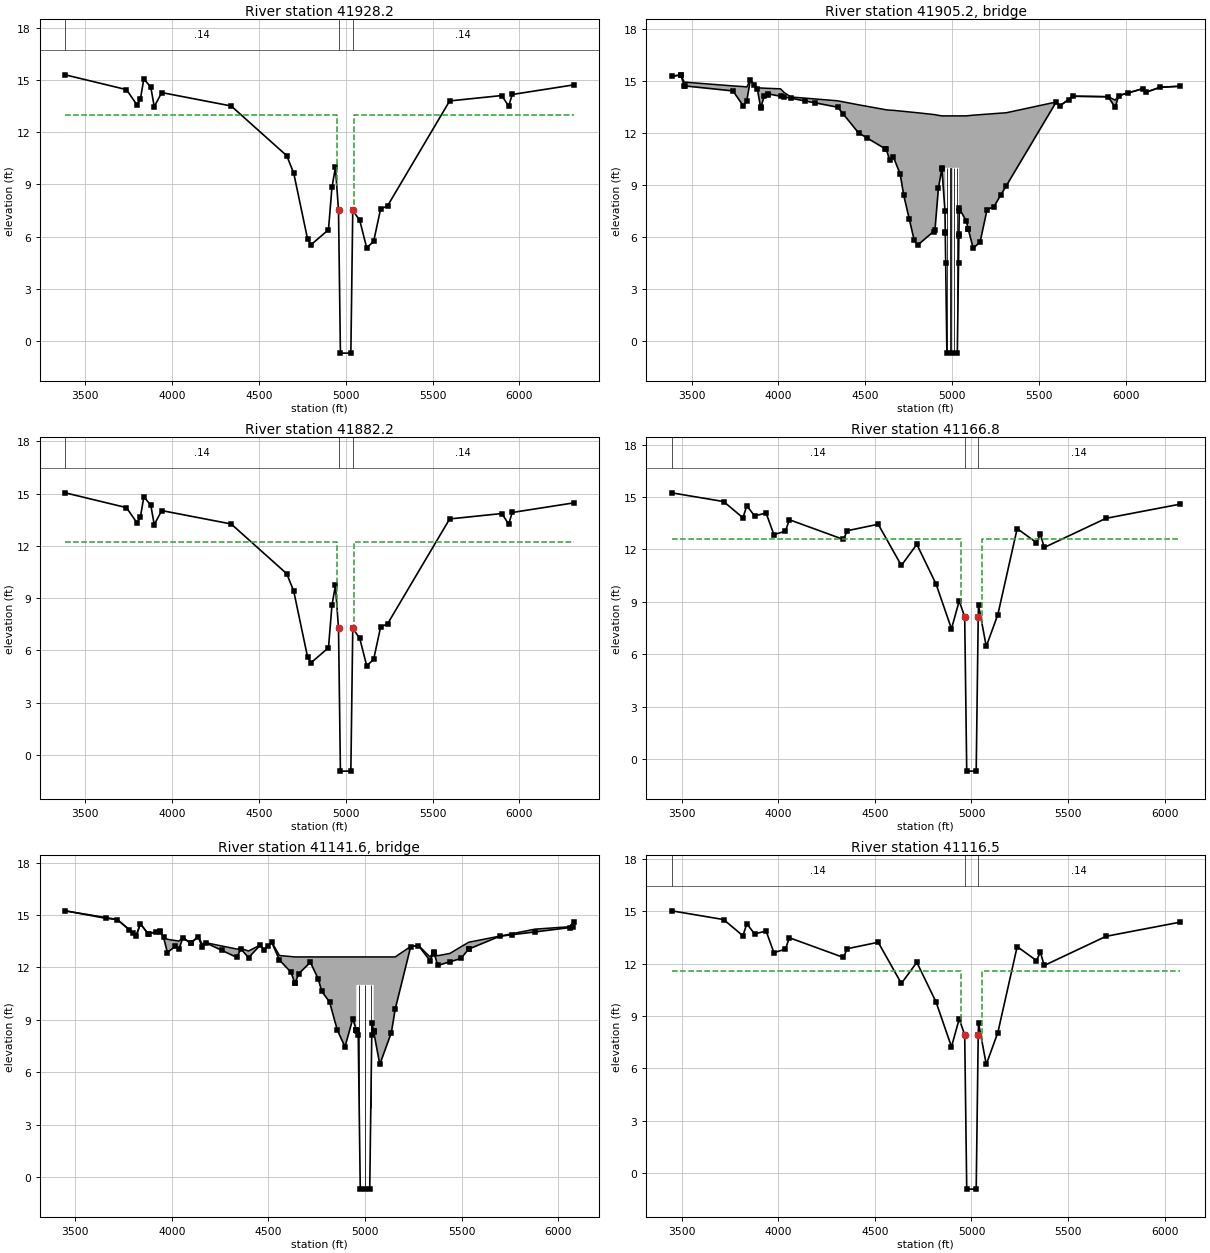
Type RM Length L Ch R = 1 ,41928.2,46,46,46
XS GIS Cut Line= 4
 2718742.8024584 896964.59370291 2718943.3742784 896490.51485572
 2720219.7404054 895986.04633884 2720354.3526533 894955.97000728
BEGIN DESCRIPTION:
Upstream Section of Bridge/Culvert/Weir
END DESCRIPTION:
#Sta/Elev= 30
  3385.8   15.29  3738.4   14.44  3798.4   13.57  3818.4   13.88  3838.4   15.06
  3878.4   14.58  3898.4   13.46  3941.2   14.27  4341.2    13.5  4661.2   10.64
  4701.2    9.64  4781.2    5.84  4801.2    5.53  4901.2    6.39  4921.2    8.82
  4941.2    9.97    4959     7.5    4970    -0.7    5030    -0.7    5041     7.5
  5081.2    6.93  5121.2    5.35  5161.2    5.72  5201.2    7.58  5241.2    7.76
  5598.7   13.79  5898.7    14.1  5938.7   13.49  5958.7   14.16  6311.8   14.71
#Mann= 3 , 1 , 0
 3385.80    0.14       0    4959   0.045       0    5041    0.14       0
#XS Ineff= 2 , 0
       0    4949      13    5051       0      13
Bank Sta=4959.00,5041.00
Exp/Cntr=0.5,0.3

Type RM Length L Ch R = 3 ,41905.2,,,
BEGIN DESCRIPTION:
Center Hill Road - TOR
Structure ID: 119
Approximate Survey Structure
END DESCRIPTION:
Bridge Culvert--1,0,-1,-1, 0
Deck Dist Width WeirC Skew NumUp NumDn MinLoCord MaxHiCord MaxSubmerge Is_Ogee
10,26,2.6,, 49, 49,,,0.95,0,1,1,,
  3385.8  3438.4  3458.4  3738.4  3798.4  3818.4  3838.4  3878.4  3898.4  3918.4
  3938.4  3941.2    4013    4033    4073  4341.2  4461.2  4621.2  4641.2  4661.2
  4701.2  4721.2  4781.2  4801.2  4901.2  4921.2    4941    4959 4960.61  4960.7
 5039.09  5039.2  5041.2  5081.2  5121.2  5161.2  5201.2  5241.2  5311.8  5598.7
  5618.7  5698.7  5898.7  5938.7  5958.7  6098.7  6118.7  6198.7  6311.8
   15.29   15.37   14.95   14.73   14.69   14.67   15.07   14.63   14.61    14.6
   14.59   14.59   14.56   14.35   14.09   13.87   13.64   13.35   13.33   13.32
   13.28   13.26    13.2   13.18   13.07   13.03      13      13      13      13
      13      13      13      13   13.04   13.07    13.1   13.13   13.18    13.8
   13.58   14.14   14.11   13.91   14.17   14.58   14.38   14.66   14.71
   15.29   15.36   14.73   14.44   13.57   13.88   15.06   14.58   13.46   14.14
   14.19   14.27   14.13   14.09   14.02    13.5   12.02   11.06   10.43   10.64
    9.64    8.43    5.84    5.53    6.39    8.82    9.96     7.5     6.3      10
      10    6.16    7.66    6.93    5.35    5.72    7.58    7.76    8.96   13.79
   13.57   14.13    14.1   13.49   14.16   14.57   14.37   14.65   14.71
  3385.8  3438.4  3458.4  3738.4  3798.4  3818.4  3838.4  3878.4  3898.4  3918.4
  3938.4  3941.2    4013    4033    4073  4341.2  4461.2  4621.2  4641.2  4661.2
  4701.2  4721.2  4781.2  4801.2  4901.2  4921.2    4941    4959 4960.61  4960.7
 5039.09  5039.2  5041.2  5081.2  5121.2  5161.2  5201.2  5241.2  5311.8  5598.7
  5618.7  5698.7  5898.7  5938.7  5958.7  6098.7  6118.7  6198.7  6311.8
   15.29   15.37   14.95   14.73   14.69   14.67   15.07   14.63   14.61    14.6
   14.59   14.59   14.56   14.35   14.09   13.87   13.64   13.35   13.33   13.32
   13.28   13.26    13.2   13.18   13.07   13.03      13      13      13      13
      13      13      13      13   13.04   13.07    13.1   13.13   13.18    13.8
   13.58   14.14   14.11   13.91   14.17   14.58   14.38   14.66   14.71
   15.04   15.11   14.48   14.19   13.32   13.63   14.81   14.33   13.21   13.89
   13.94   14.02   13.88   13.84   13.77   13.25   11.77   10.81   10.18   10.39
    9.39    8.18    5.59    5.28    6.14    8.57    9.71    7.25    6.05    9.75
    9.75    5.91    7.41    6.68     5.1    5.47    7.33    7.51    8.71   13.54
   13.32   13.88   13.85   13.24   13.91   14.32   14.12    14.4   14.46
Pier Skew, UpSta & Num, DnSta & Num=,4972.2, 2 ,4972.2, 2 , 0 , 0 , 0 ,,
       1       1
    -1.7      11
       1       1
   -1.95   10.75
Pier Skew, UpSta & Num, DnSta & Num=,4990.7, 2 ,4990.7, 2 , 0 , 0 , 0 ,,
       1       1
    -1.7      11
       1       1
   -1.95   10.75
Pier Skew, UpSta & Num, DnSta & Num=,5009.2, 2 ,5009.2, 2 , 0 , 0 , 0 ,,
       1       1
    -1.7      11
       1       1
   -1.95   10.75
Pier Skew, UpSta & Num, DnSta & Num=,5027.7, 2 ,5027.7, 2 , 0 , 0 , 0 ,,
       1       1
    -1.7      11
       1       1
   -1.95   10.75
Abutment Skew #Up #Dn=, 2 , 2
 4960.50 4963.00
   10.00    4.52
 4960.50 4963.00
    9.75    4.27
Abutment Skew #Up #Dn=, 2 , 2
 5037.00 5039.29
    4.52   10.00
 5037.00 5039.29
    4.27    9.75
BR Coef= 1 , 1 , 0 ,1.25, 0 ,,,0.8,0,2,0,
Wspro=,,,, 1 ,,,, 0 ,,,, 0 ,,,,-1 ,-1 ,-1 , 0 , 0 , 0 , 0 , 0
BC Design=,, 0 ,, 0 ,,,,,,
BR U #Sta/Elev= 72
  3385.8   15.29  3437.9   15.35  3438.4   15.36  3458.4   14.73  3460.5   14.73
  3738.4   14.44  3798.4   13.57  3818.4   13.88  3838.4   15.06  3860.5   14.79
  3878.4   14.58  3898.4   13.46  3900.5   13.53  3918.4   14.14  3938.4   14.19
  3941.2   14.27    4013   14.13    4033   14.09    4073   14.02    4153   13.86
    4213   13.75  4341.2    13.5    4373   13.11  4461.2   12.02    4513   11.71
    4613   11.11  4621.2   11.06  4641.2   10.43  4661.2   10.64  4701.2    9.64
  4721.2    8.43    4753    7.06  4781.2    5.84  4801.2    5.53    4893    6.32
  4901.2    6.39  4921.2    8.82    4941    9.96  4941.2    9.97    4959     7.5
 4960.61     6.3  4960.7    6.23    4963    4.52    4970    -0.7    5000    -0.7
    5030    -0.7    5037    4.52 5039.09    6.08  5039.2    6.16    5041     7.5
  5041.2    7.66  5081.2    6.93  5092.7    6.48    5093    6.46  5121.2    5.35
  5161.2    5.72  5201.2    7.58  5241.2    7.76  5281.2    8.45  5311.8    8.96
  5598.7   13.79  5618.7   13.57  5671.8   13.94  5698.7   14.13  5898.7    14.1
  5938.7   13.49  5958.7   14.16  6011.8   14.32  6098.7   14.57  6118.7   14.37
  6198.7   14.65  6311.8   14.71
BR U #Mann= 3
 3385.80    0.14    4959   0.045    5041    0.14
BR U Banks=4959.00,5041.00
BR D #Sta/Elev= 72
  3385.8   15.04  3437.9    15.1  3438.4   15.11  3458.4   14.48  3460.5   14.48
  3738.4   14.19  3798.4   13.32  3818.4   13.63  3838.4   14.81  3860.5   14.54
  3878.4   14.33  3898.4   13.21  3900.5   13.28  3918.4   13.89  3938.4   13.94
  3941.2   14.02    4013   13.88    4033   13.84    4073   13.77    4153   13.61
    4213    13.5  4341.2   13.25    4373   12.86  4461.2   11.77    4513   11.46
    4613   10.86  4621.2   10.81  4641.2   10.18  4661.2   10.39  4701.2    9.39
  4721.2    8.18    4753    6.81  4781.2    5.59  4801.2    5.28    4893    6.07
  4901.2    6.14  4921.2    8.57    4941    9.71  4941.2    9.72    4959    7.25
 4960.61    6.05  4960.7    5.98    4963    4.27    4970   -0.95    5000   -0.95
    5030   -0.95    5037    4.27 5039.09    5.83  5039.2    5.91    5041    7.25
  5041.2    7.41  5081.2    6.68  5092.7    6.23    5093    6.21  5121.2     5.1
  5161.2    5.47  5201.2    7.33  5241.2    7.51  5281.2     8.2  5311.8    8.71
  5598.7   13.54  5618.7   13.32  5671.8   13.69  5698.7   13.88  5898.7   13.85
  5938.7   13.24  5958.7   13.91  6011.8   14.07  6098.7   14.32  6118.7   14.12
  6198.7    14.4  6311.8   14.46
BR D #Mann= 3
 3385.80    0.14    4959   0.045    5041    0.14
BR D Banks=4959.00,5041.00

Type RM Length L Ch R = 1 ,41882.2,715.45,715.45,715.45
XS GIS Cut Line= 4
 2718785.1374448 896982.58672744 2718985.7092647 896508.50788025
 2720262.0753918 896004.03936337 2720396.6876396 894973.96303181
BEGIN DESCRIPTION:
Downstream Section of Bridge/Culvert/Weir
END DESCRIPTION:
#Sta/Elev= 30
  3385.8   15.05  3738.4    14.2  3798.4   13.33  3818.4   13.64  3838.4   14.82
  3878.4   14.34  3898.4   13.22  3941.2   14.03  4341.2   13.26  4661.2    10.4
  4701.2     9.4  4781.2     5.6  4801.2    5.29  4901.2    6.15  4921.2    8.58
  4941.2    9.73    4959    7.26    4970   -0.94    5030   -0.94    5041    7.26
  5081.2    6.69  5121.2    5.11  5161.2    5.48  5201.2    7.34  5241.2    7.52
  5598.7   13.55  5898.7   13.86  5938.7   13.25  5958.7   13.92  6311.8   14.47
#Mann= 3 , 1 , 0
 3385.80    0.14       0    4959   0.045       0    5041    0.14       0
#XS Ineff= 2 , 0
       0 4952.33   12.25 5047.67       0   12.25
Bank Sta=4959.00,5041.00
Exp/Cntr=0.5,0.3

Type RM Length L Ch R = 1 ,41166.8,50.3,50.3,50.3
XS GIS Cut Line= 4
 2720551.3996480 897546.98292818 2720733.7376661 896228.07126357
 2720691.1921286 895942.40836847 2720443.3679056 894962.37621413
BEGIN DESCRIPTION:
Upstream Section of Bridge/Culvert/Weir
END DESCRIPTION:
#Sta/Elev= 30
  3448.3   15.24  3717.2   14.74  3817.2   13.81  3837.2    14.5  3877.2   13.92
  3937.2   14.08  3977.2   12.85  4037.2   13.04  4057.2    13.7  4337.2   12.57
  4357.2   13.07  4517.2   13.44  4637.2   11.08  4717.2   12.29  4816.6   10.02
  4896.6    7.45  4936.6    9.05    4965    8.13  4975.5    -0.7  5024.5    -0.7
    5035    8.13  5036.6    8.82  5076.6    6.44  5136.6    8.27  5236.6   13.19
  5336.6   12.39  5356.6   12.87  5376.6   12.11  5696.6   13.78  6079.4   14.59
#Mann= 3 , 1 , 0
 3448.30    0.14       0    4965   0.045       0    5035    0.14       0
#XS Ineff= 2 , 0
       0    4945    12.6    5055       0    12.6
Bank Sta=4965.00,5035.00
Exp/Cntr=0.5,0.3

Type RM Length L Ch R = 3 ,41141.6,,,
BEGIN DESCRIPTION:
Great Hope Ch Rd 2 - TOR
Structure ID: 118
Approximate Survey Structure
END DESCRIPTION:
Bridge Culvert--1,0,-1,-1, 0
Deck Dist Width WeirC Skew NumUp NumDn MinLoCord MaxHiCord MaxSubmerge Is_Ogee
10,30.3,2.6,, 54, 54,,,0.95,0,1,1,,
  3448.3  3717.2  3799.7  3817.2  3837.2  3877.2  3937.2  3957.2  3977.2  4017.2
  4037.2  4057.2  4097.2  4137.2  4157.2  4177.2  4337.2  4357.2  4397.2  4457.2
  4477.2  4517.2  4557.2  4617.2  4637.2  4657.2  4717.2  4757.2  4776.6  4816.6
  4856.6  4896.6  4936.6 4954.91    4955 5044.89    5045  5076.6  5136.6  5156.6
  5236.6  5276.6  5336.6  5356.6  5359.4  5376.6  5439.4  5496.6  5536.6  5696.6
  5879.4  6059.4  6076.6  6079.4
   15.24   14.75   13.98   13.89   14.51   13.93   14.09   13.74   13.61   13.54
   13.51   13.71    13.4   13.77   13.33   13.41   13.05   13.08   12.94   13.28
   13.01   13.45   12.68   12.62    12.6    12.6    12.6    12.6    12.6    12.6
    12.6    12.6    12.6    12.6    12.6    12.6    12.6    12.6    12.6    12.6
    13.2   13.26    12.6   12.88   12.77   12.67    12.8   13.18   13.44   13.79
   14.19   14.33   14.55   14.59
   15.24   14.74   13.97   13.81    14.5   13.92   14.08   13.73   12.85    13.2
   13.04    13.7   13.38   13.76   13.14    13.4   12.57   13.07   12.55   13.27
      13   13.44   12.42   11.72   11.08   11.64   12.29   11.36   10.62   10.02
    8.41    7.45    9.05    8.43      11      11    8.32    6.44    8.27    9.62
   13.19   13.25   12.39   12.87   12.76   12.11   12.32   12.51   13.05   13.78
   14.03   14.28    14.3   14.59
  3448.3  3717.2  3799.7  3817.2  3837.2  3877.2  3937.2  3957.2  3977.2  4017.2
  4037.2  4057.2  4097.2  4137.2  4157.2  4177.2  4337.2  4357.2  4397.2  4457.2
  4477.2  4517.2  4557.2  4617.2  4637.2  4657.2  4717.2  4757.2  4776.6  4816.6
  4856.6  4896.6  4936.6 4954.91    4955 5044.89    5045  5076.6  5136.6  5156.6
  5236.6  5276.6  5336.6  5356.6  5359.4  5376.6  5439.4  5496.6  5536.6  5696.6
  5879.4  6059.4  6076.6  6079.4
   15.24   14.75   13.98   13.89   14.51   13.93   14.09   13.74   13.61   13.54
   13.51   13.71    13.4   13.77   13.33   13.41   13.05   13.08   12.94   13.28
   13.01   13.45   12.68   12.62    12.6    12.6    12.6    12.6    12.6    12.6
    12.6    12.6    12.6    12.6    12.6    12.6    12.6    12.6    12.6    12.6
    13.2   13.26    12.6   12.88   12.77   12.67    12.8   13.18   13.44   13.79
   14.19   14.33   14.55   14.59
   14.99   14.49   13.72   13.56   14.25   13.67   13.83   13.48    12.6   12.95
   12.79   13.45   13.13   13.51   12.89   13.15   12.32   12.82    12.3   13.02
   12.75   13.19   12.17   11.47   10.83   11.39   12.04   11.11   10.37    9.77
    8.16     7.2     8.8    8.18   10.75   10.75    8.07    6.19    8.02    9.37
   12.94      13   12.14   12.62   12.51   11.86   12.07   12.26    12.8   13.53
   13.78   14.03   14.05   14.34
Pier Skew, UpSta & Num, DnSta & Num=,4970.0, 2 ,4970.0, 2 , 0 , 0 , 0 ,,
       1       1
     2.5      12
       1       1
    2.25   11.75
Pier Skew, UpSta & Num, DnSta & Num=,5000.0, 2 ,5000.0, 2 , 0 , 0 , 0 ,,
       1       1
    -1.7      12
       1       1
   -1.95   11.75
Pier Skew, UpSta & Num, DnSta & Num=,5030.0, 2 ,5030.0, 2 , 0 , 0 , 0 ,,
       1       1
     2.5      12
       1       1
    2.25   11.75
BR Coef= 1 , 1 , 0 ,1.25, 0 ,,,0.8,0,2,0,
Wspro=,,,, 1 ,,,, 0 ,,,, 0 ,,,,-1 ,-1 ,-1 , 0 , 0 , 0 , 0 , 0
BC Design=,, 0 ,, 0 ,,,,,,
BR U #Sta/Elev= 75
  3448.3   15.24  3659.9   14.81  3717.2   14.74  3779.7   14.16  3799.7   13.97
  3817.2   13.81  3837.2    14.5  3877.2   13.92  3879.7   13.93  3919.7   14.03
  3937.2   14.08  3939.7   14.04  3957.2   13.73  3977.2   12.85  4017.2    13.2
  4037.2   13.04  4057.2    13.7  4097.2   13.38  4099.7    13.4  4137.2   13.76
  4157.2   13.14  4177.2    13.4  4259.7   12.97  4337.2   12.57  4357.2   13.07
  4397.2   12.55  4457.2   13.27  4477.2      13  4499.7   13.25  4517.2   13.44
  4557.2   12.42  4617.2   11.72  4637.2   11.08  4639.1   11.13  4657.2   11.64
  4717.2   12.29  4757.2   11.36  4776.6   10.62  4816.6   10.02  4856.6    8.41
  4896.6    7.45  4936.6    9.05 4954.91    8.43    4955    8.42  4955.1    8.42
  4956.6    8.37    4965    8.13  4975.5    -0.7    5000    -0.7  5024.5    -0.7
    5035    8.13  5036.6    8.82  5044.8    8.33 5044.89    8.33    5045    8.32
  5076.6    6.44  5136.6    8.27  5156.6    9.62  5236.6   13.19  5276.6   13.25
  5336.6   12.39  5356.6   12.87  5357.8   12.82  5359.4   12.76  5376.6   12.11
  5439.4   12.32  5496.6   12.51  5536.6   13.05  5539.4   13.06  5696.6   13.78
  5759.4   13.87  5879.4   14.03  6059.4   14.28  6076.6    14.3  6079.4   14.59
BR U #Mann= 3
 3448.30    0.14    4965   0.045    5035    0.14
BR U Banks=4965.00,5035.00
BR D #Sta/Elev= 75
  3448.3   14.99  3659.9   14.56  3717.2   14.49  3779.7   13.91  3799.7   13.72
  3817.2   13.56  3837.2   14.25  3877.2   13.67  3879.7   13.68  3919.7   13.78
  3937.2   13.83  3939.7   13.79  3957.2   13.48  3977.2    12.6  4017.2   12.95
  4037.2   12.79  4057.2   13.45  4097.2   13.13  4099.7   13.15  4137.2   13.51
  4157.2   12.89  4177.2   13.15  4259.7   12.72  4337.2   12.32  4357.2   12.82
  4397.2    12.3  4457.2   13.02  4477.2   12.75  4499.7      13  4517.2   13.19
  4557.2   12.17  4617.2   11.47  4637.2   10.83  4639.1   10.88  4657.2   11.39
  4717.2   12.04  4757.2   11.11  4776.6   10.37  4816.6    9.77  4856.6    8.16
  4896.6     7.2  4936.6     8.8 4954.91    8.18    4955    8.17  4955.1    8.17
  4956.6    8.12    4965    7.88  4975.5   -0.95    5000   -0.95  5024.5   -0.95
    5035    7.88  5036.6    8.57  5044.8    8.08 5044.89    8.08    5045    8.07
  5076.6    6.19  5136.6    8.02  5156.6    9.37  5236.6   12.94  5276.6      13
  5336.6   12.14  5356.6   12.62  5357.8   12.57  5359.4   12.51  5376.6   11.86
  5439.4   12.07  5496.6   12.26  5536.6    12.8  5539.4   12.81  5696.6   13.53
  5759.4   13.62  5879.4   13.78  6059.4   14.03  6076.6   14.05  6079.4   14.34
BR D #Mann= 3
 3448.30    0.14    4965   0.045    5035    0.14
BR D Banks=4965.00,5035.00

Type RM Length L Ch R = 1 ,41116.5,1110.05,1110.05,1110.05
XS GIS Cut Line= 4
 2720598.9888824 897530.69321469 2720781.3269006 896211.78155008
 2720738.7813630 895926.11865498 2720490.9571401 894946.08650063
BEGIN DESCRIPTION:
Downstream Section of Bridge/Culvert/Weir
END DESCRIPTION:
#Sta/Elev= 30
  3448.3   15.02  3717.2   14.52  3817.2   13.59  3837.2   14.28  3877.2    13.7
  3937.2   13.86  3977.2   12.63  4037.2   12.82  4057.2   13.48  4337.2   12.35
  4357.2   12.85  4517.2   13.22  4637.2   10.86  4717.2   12.07  4816.6     9.8
  4896.6    7.23  4936.6    8.83    4965    7.91  4975.5   -0.92  5024.5   -0.92
    5035    7.91  5036.6     8.6  5076.6    6.22  5136.6    8.05  5236.6   12.97
  5336.6   12.17  5356.6   12.65  5376.6   11.89  5696.6   13.56  6079.4   14.37
#Mann= 3 , 1 , 0
 3448.30    0.14       0    4965   0.045       0    5035    0.14       0
#XS Ineff= 2 , 0
       0    4945    11.6    5055       0    11.6
Bank Sta=4965.00,5035.00
Exp/Cntr=0.5,0.3

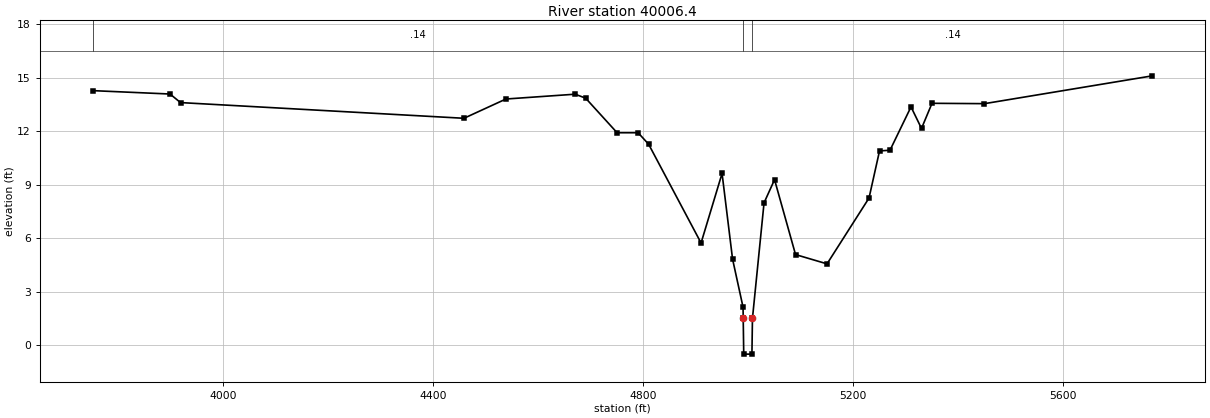
Type RM Length L Ch R = 1 ,40006.4,1025.8,1025.8,1025.8
XS GIS Cut Line= 3
 2721887.5575491 896903.58537262 2721501.2022935 896217.80479387
 2722090.3940583 895136.01007809
BEGIN DESCRIPTION:
Goodwin Mill 40.0
END DESCRIPTION:
#Sta/Elev= 30
  3751.9   14.27  3899.1   14.08  3919.1    13.6  4459.1   12.72  4539.1    13.8
  4670.9   14.07  4690.9   13.85  4750.9   11.91  4790.9   11.91  4810.9   11.27
  4910.9    5.73  4950.9    9.63  4970.9    4.83  4990.9    2.13  4991.2     1.5
  4992.2    -0.5  5007.8    -0.5  5008.8     1.5  5030.9    7.98  5050.9    9.28
  5090.9    5.08  5150.9    4.56  5230.9    8.25  5250.9   10.89  5270.9   10.93
  5310.9   13.36  5330.9   12.15  5350.9   13.56  5450.9   13.54  5770.9    15.1
#Mann= 3 , 1 , 0
 3751.90    0.14       0  4991.2   0.045       0  5008.8    0.14       0
Bank Sta=4991.20,5008.80
Exp/Cntr=0.3,0.1