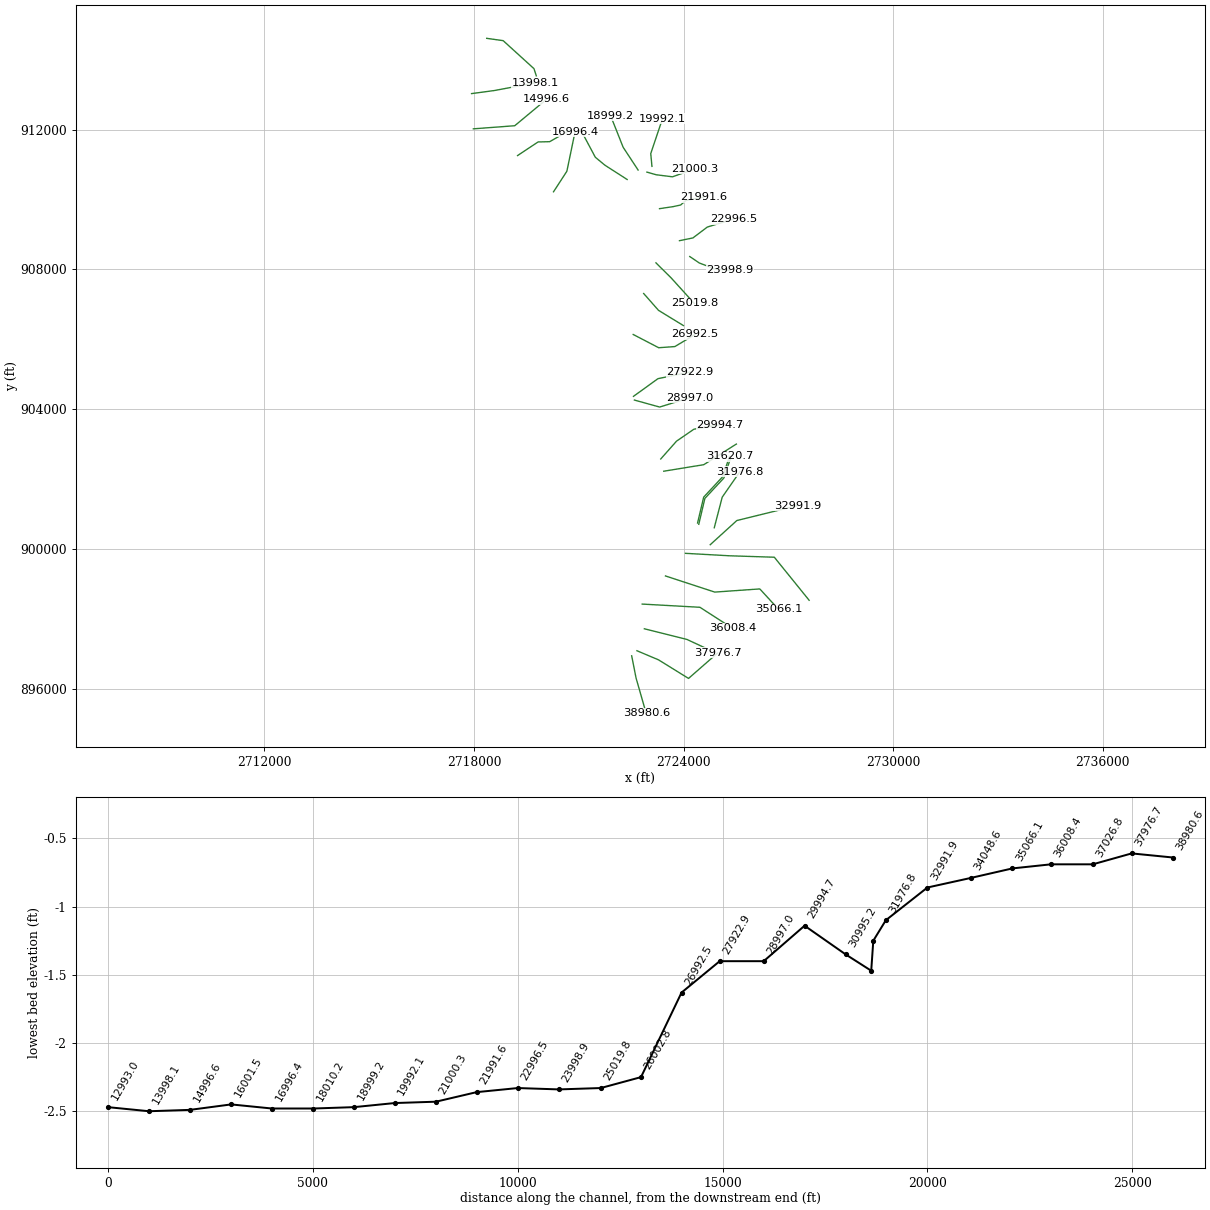
HEC-RAS study GOODWIN MILL CREEK.PRJ: Goodwin Mill Creek

--- GOODWIN MILL CREEK.g01 (geometry) --- (continued)

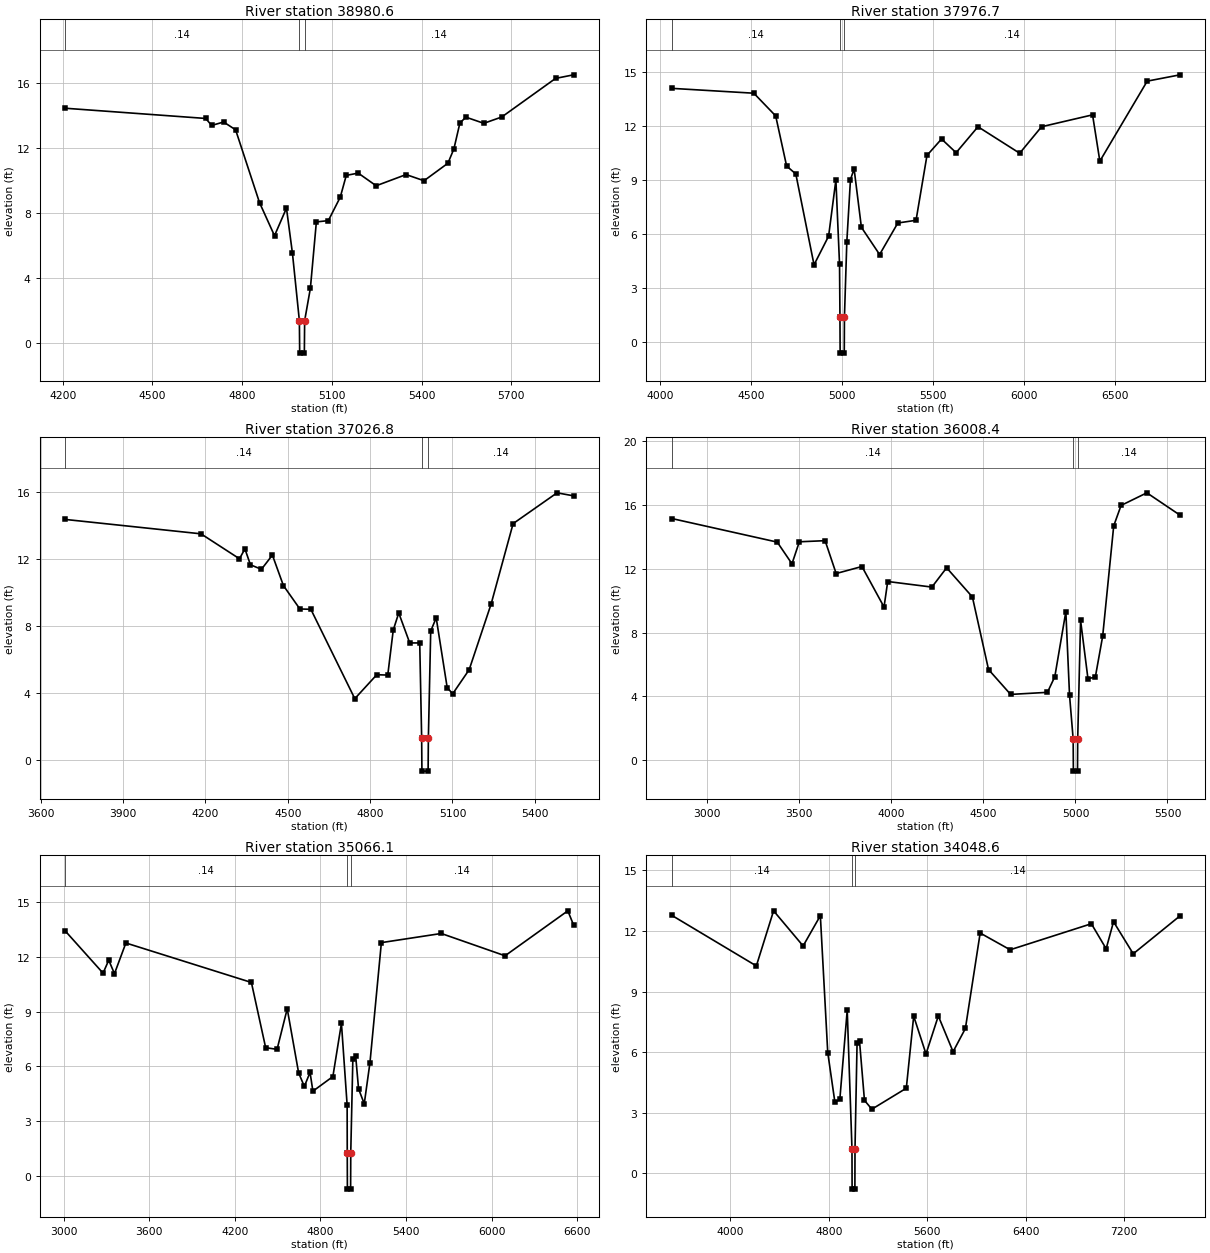
Type RM Length L Ch R = 1 ,38980.6,1003.9,1003.9,1003.9
XS GIS Cut Line= 3
 2722515.3848395 896951.87977957 2722640.9502976 896314.39360778
 2722930.7167393 895305.04050243
BEGIN DESCRIPTION:
Goodwin Mill 39.0
END DESCRIPTION:
#Sta/Elev= 30
  4208.1   14.46  4677.9   13.83  4697.9    13.4  4737.9   13.61  4777.9   13.13
  4857.9    8.64    4908     6.6    4948     8.3    4968    5.52  4991.2    1.36
  4992.2   -0.64  5007.8   -0.64  5008.8    1.36    5028    3.36    5048    7.45
    5088    7.53    5128    8.98    5148   10.32    5188   10.46    5248    9.68
    5348   10.37    5408    9.99    5488   11.07    5508   11.96    5528   13.55
    5548   13.91    5608   13.53    5668   13.92    5848    16.3    5908   16.52
#Mann= 3 , 1 , 0
 4208.10    0.14       0  4991.2   0.045       0  5008.8    0.14       0
Bank Sta=4991.20,5008.80
Exp/Cntr=0.3,0.1

Type RM Length L Ch R = 1 ,37976.7,949.9,949.9,949.9
XS GIS Cut Line= 4
 2722665.0975011 897096.76300044 2723283.2659101 896835.97320288
 2724142.9063539 896304.73472639 2724978.3995942  897033.9802714
BEGIN DESCRIPTION:
Goodwin Mill 38.0
END DESCRIPTION:
#Sta/Elev= 30
  4063.9   14.08  4514.9   13.81  4634.9   12.55  4694.9    9.77  4745.4    9.33
  4845.4    4.29  4925.4    5.88  4965.4       9  4985.4    4.32  4987.7    1.39
  4988.7   -0.61  5011.3   -0.61  5012.3    1.39  5025.4    5.57  5045.4    9.02
  5065.4    9.61  5105.4    6.37  5205.4    4.86  5305.4    6.61  5405.4    6.76
  5465.4   10.36  5545.4   11.27  5625.4   10.51  5745.4   11.95  5974.4   10.48
  6094.4   11.95  6374.4   12.61  6414.4   10.04  6674.4   14.48  6854.4   14.83
#Mann= 3 , 1 , 0
 4063.90    0.14       0  4987.7   0.045       0  5012.3    0.14       0
Bank Sta=4987.70,5012.30
Exp/Cntr=0.3,0.1

Type RM Length L Ch R = 1 ,37026.8,1018.4,1018.4,1018.4
XS GIS Cut Line= 3
 2722877.5928917 897724.59029084 2724094.6119469 897420.33552703
 2724635.5093048 897169.20461087
BEGIN DESCRIPTION:
Goodwin Mill 37.0
END DESCRIPTION:
#Sta/Elev= 30
  3689.9   14.35  4184.3   13.49  4324.3      12  4344.3   12.59  4364.3   11.64
  4404.3   11.37  4444.3   12.22  4484.3    10.4  4544.3       9  4584.3    8.98
  4744.3    3.64  4824.3    5.07  4864.3    5.05  4884.3    7.74  4904.3    8.76
  4944.3    6.97  4980.7    6.97  4987.7    1.31  4988.7   -0.69  5011.2   -0.69
  5012.2    1.31  5020.7    7.68  5040.7    8.47  5080.7     4.3  5100.7    3.93
  5160.7    5.37  5240.7     9.3  5320.7    14.1  5480.7   15.94  5540.7   15.76
#Mann= 3 , 1 , 0
 3689.90    0.14       0  4987.7   0.045       0  5012.2    0.14       0
Bank Sta=4987.70,5012.20
Exp/Cntr=0.3,0.1

Type RM Length L Ch R = 1 ,36008.4,942.3,942.3,942.3
XS GIS Cut Line= 3
 2722818.0583903 898430.54424469 2724468.9133309 898338.83008133
 2725400.1648359 897739.16055162
BEGIN DESCRIPTION:
Goodwin Mill 36.0
END DESCRIPTION:
#Sta/Elev= 30
  2806.9   15.15  3380.3   13.67  3460.3   12.31  3500.3   13.69  3640.3   13.76
  3700.3    11.7  3840.3   12.14  3960.3     9.6  3980.3    11.2  4220.3   10.85
  4300.3   12.06  4440.3   10.23  4527.9    5.68  4647.9    4.12  4847.9    4.25
  4887.9    5.23  4947.9    9.31  4967.9    4.07  4987.7    1.31  4988.7   -0.69
  5011.2   -0.69  5012.2    1.31  5027.9    8.76  5067.9    5.11  5107.9     5.2
  5147.9    7.77  5207.9   14.69  5247.9   15.97  5387.9   16.76  5567.9   15.36
#Mann= 3 , 1 , 0
 2806.90    0.14       0  4987.7   0.045       0  5012.2    0.14       0
Bank Sta=4987.70,5012.20
Exp/Cntr=0.3,0.1

Type RM Length L Ch R = 1 ,35066.1,1017.5,1017.5,1017.5
XS GIS Cut Line= 4
 2723482.3186677 899234.83322647 2724893.9195768 898772.97302119
  2726181.924093 898864.04404758 2726715.3401047 898285.09252265
BEGIN DESCRIPTION:
Goodwin Mill 35.0
END DESCRIPTION:
#Sta/Elev= 30
  3010.4   13.41  3275.7    11.1  3315.7   11.81  3355.7   11.07  3435.7   12.75
  4315.7   10.59  4415.7    7.02  4495.7    6.93  4566.9    9.15  4646.9    5.64
  4686.9     4.9  4726.9    5.67  4746.9    4.64  4886.9    5.44  4946.9    8.35
  4986.9    3.88  4987.7    1.28  4988.7   -0.72  5011.3   -0.72  5012.3    1.28
  5026.9    6.38  5046.9    6.55  5066.9    4.77  5106.9    3.95  5146.9     6.2
  5226.9   12.77  5646.9   13.27  6094.1   12.05  6534.1   14.51  6574.1   13.74
#Mann= 3 , 1 , 0
 3010.40    0.14       0  4987.7   0.045       0  5012.3    0.14       0
Bank Sta=4987.70,5012.30
Exp/Cntr=0.3,0.1

Type RM Length L Ch R = 1 ,34048.6,1056.7,1056.7,1056.7
XS GIS Cut Line= 4
 2724053.8402767 899881.74510199 2725319.7732661 899811.41549147
 2726597.4278573 899770.38988533 2727593.7640063 898539.62170116
BEGIN DESCRIPTION:
Goodwin Mill 34.0
END DESCRIPTION:
#Sta/Elev= 30
  3522.9   12.78  4210.8   10.27  4350.8      13  4590.8   11.26  4730.8   12.76
  4790.8    5.98  4849.1    3.51  4889.1    3.66  4949.1    8.08  4987.7    1.21
  4988.7   -0.79  5011.3   -0.79  5012.3    1.21  5029.1    6.46  5049.1    6.53
  5089.1    3.61  5149.1    3.17  5429.1    4.21  5489.1    7.78  5589.1    5.91
  5689.1    7.79  5809.1    6.02  5909.1    7.17  6029.1    11.9  6272.6   11.07
  6932.6   12.36  7052.6   11.12  7112.6   12.46  7272.6   10.87  7652.6   12.75
#Mann= 3 , 1 , 0
 3522.90    0.14       0  4987.7   0.045       0  5012.3    0.14       0
Bank Sta=4987.70,5012.30
Exp/Cntr=0.3,0.1

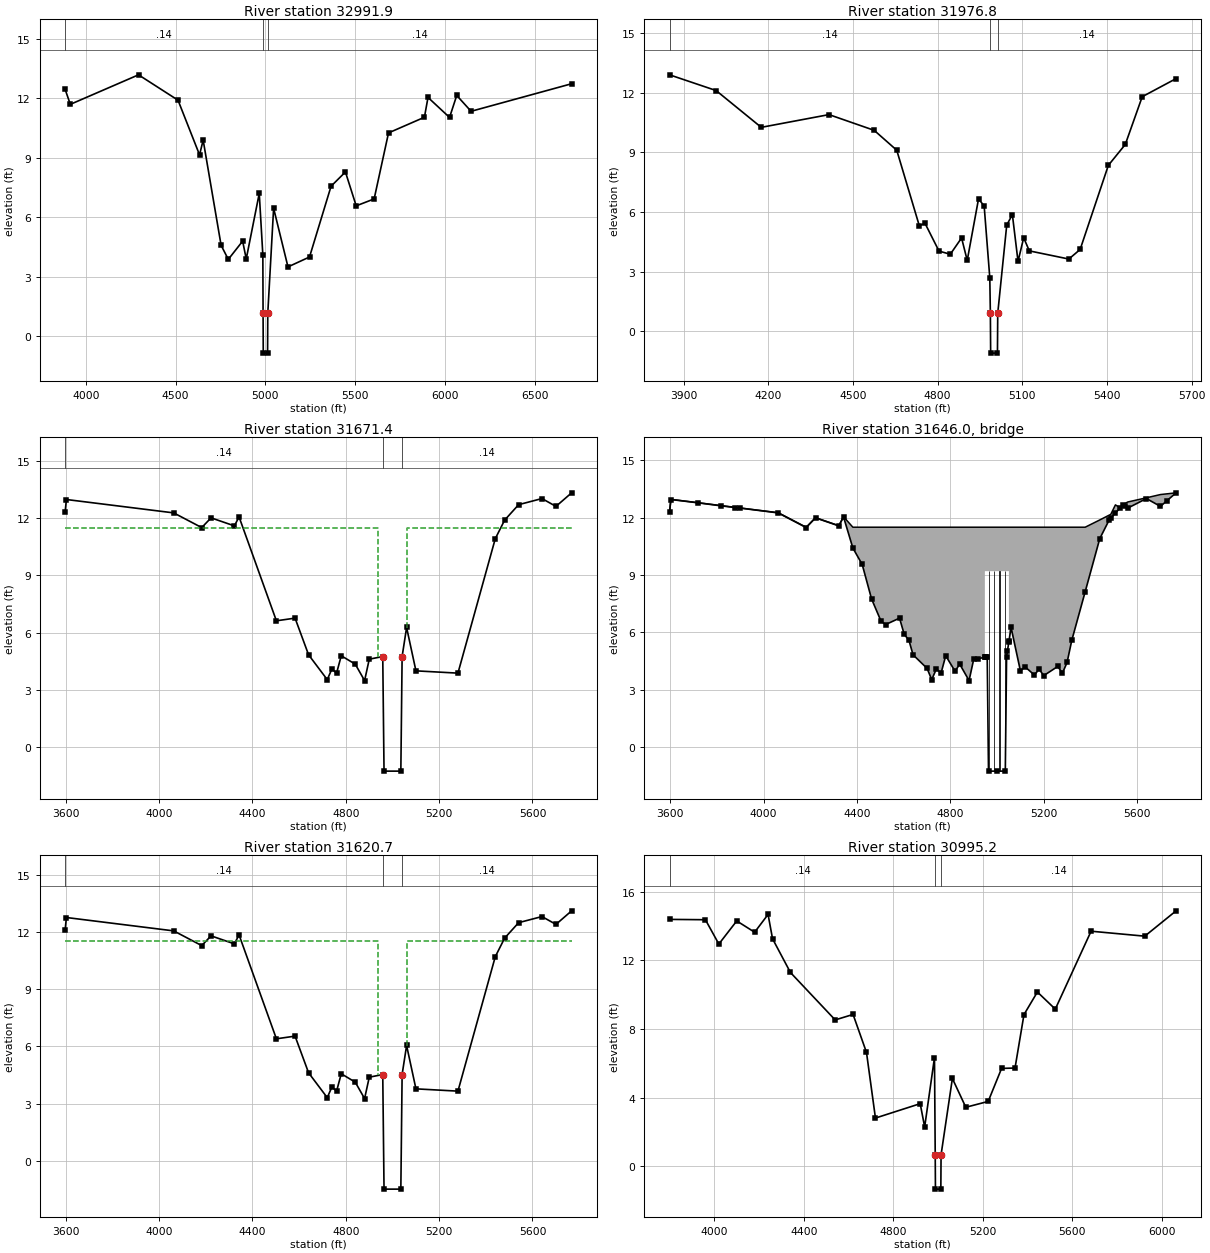
Type RM Length L Ch R = 1 ,32991.9,1015.1,1015.1,1015.1
XS GIS Cut Line= 3
 2724762.9971828 900127.89873882 2725524.9012968  900819.4732423
 2727265.5591572 901247.31170632
BEGIN DESCRIPTION:
Goodwin Mill 33.0
END DESCRIPTION:
#Sta/Elev= 30
  3884.2   12.45  3913.1   11.69  4293.1   13.18  4513.1    11.9  4633.1    9.14
  4653.1    9.89  4753.1    4.58  4793.1    3.87  4873.1    4.79  4893.1    3.89
  4965.6     7.2  4985.6    4.09  4986.9    1.14  4987.9   -0.86    5012   -0.86
    5013    1.14  5045.6    6.45  5125.6    3.49  5245.6    3.99  5365.6    7.56
  5445.6    8.28  5505.6    6.57  5605.6    6.92  5685.6   10.25  5885.6   11.04
  5905.6   12.04  6025.6   11.03  6065.6   12.14  6145.6   11.34  6705.6   12.73
#Mann= 3 , 1 , 0
 3884.20    0.14       0  4986.9   0.045       0    5013    0.14       0
Bank Sta=4986.90,5013.00
Exp/Cntr=0.3,0.1

Type RM Length L Ch R = 1 ,31976.8,305.45,305.45,305.45
XS GIS Cut Line= 3
 2724878.9924941  900613.4586234 2725106.9695427 901489.09774198
 2725614.7366055  902219.6605569
BEGIN DESCRIPTION:
Goodwin Mill 32.0
END DESCRIPTION:
#Sta/Elev= 30
  3850.4   12.89  4015.2    12.1  4175.2   10.25  4415.2   10.89  4575.2    10.1
  4655.2     9.1  4735.2     5.3  4755.2    5.43  4804.9    4.03  4844.9    3.87
  4884.9    4.69  4904.9    3.56  4944.9    6.65  4964.9     6.3  4984.9    2.68
  4986.9     0.9  4987.9    -1.1    5012    -1.1    5013     0.9  5044.9    5.34
  5064.9    5.86  5084.9    3.51  5104.9     4.7  5124.9    4.04  5264.9    3.63
  5304.9    4.11  5404.9    8.34  5464.9    9.39  5524.9   11.79  5644.9    12.7
#Mann= 3 , 1 , 0
 3850.40    0.14       0  4986.9   0.045       0    5013    0.14       0
Bank Sta=4986.90,5013.00
Exp/Cntr=0.3,0.1

Type RM Length L Ch R = 1 ,31671.4,50.7,50.7,50.7
XS GIS Cut Line= 4
 2724435.3218442 900711.76687684 2724610.2354102 901451.40138456
 2725155.2898917 902037.48147225 2725349.4825351 902615.64593317
BEGIN DESCRIPTION:
Upstream Section of Bridge/Culvert/Weir
END DESCRIPTION:
#Sta/Elev= 30
  3597.5   12.31    3603   12.97  4062.8   12.27  4182.8    11.5  4222.8   12.01
  4322.8   11.59  4342.8   12.06  4502.8    6.62  4582.8    6.76  4640.7    4.84
  4720.7    3.54  4740.7     4.1  4760.7    3.88  4780.7    4.79  4840.7    4.35
  4880.7    3.49  4900.7    4.61  4958.5    4.75    4964   -1.25    5036   -1.25
  5041.5    4.75  5060.7    6.27  5100.7       4  5280.7    3.88  5440.7   10.92
  5480.7   11.89  5540.7    12.7  5640.7   13.02  5700.7   12.61  5767.8   13.32
#Mann= 3 , 1 , 0
 3597.50    0.14       0  4958.5   0.045       0  5041.5    0.14       0
#XS Ineff= 2 , 0
       0  4938.5    11.5  5061.5       0    11.5
Bank Sta=4958.50,5041.50
Exp/Cntr=0.5,0.3

Type RM Length L Ch R = 3 ,31646.0,,,
BEGIN DESCRIPTION:
Great Hope Ch Rd - TOR
Structure ID: 116
Approximate Survey Structure
END DESCRIPTION:
Bridge Culvert--1,0,-1,-1, 0
Deck Dist Width WeirC Skew NumUp NumDn MinLoCord MaxHiCord MaxSubmerge Is_Ogee
10,30.7,2.6,, 50, 50,,,0.95,0,1,1,,
  3597.5    3603  4062.8  4182.8  4222.8  4322.8  4342.8  4382.8  4422.8  4462.8
  4502.8  4522.8  4582.8  4602.8  4622.8  4640.7  4700.7  4720.7  4740.7  4760.7
  4780.7  4820.7  4840.7  4880.7  4900.7 4948.41  4948.5 5051.39  5051.5  5060.7
  5100.7  5120.7  5160.7  5180.7  5200.7  5260.7  5280.7  5300.7  5320.7  5378.2
  5440.7  5480.7  5487.8  5507.8  5527.8  5540.7  5560.7  5640.7  5700.7  5767.8
   12.29   12.96   12.26    11.5      12   11.58   12.05    11.5    11.5    11.5
    11.5    11.5    11.5    11.5    11.5    11.5    11.5    11.5    11.5    11.5
    11.5    11.5    11.5    11.5    11.5    11.5    11.5    11.5    11.5    11.5
    11.5    11.5    11.5    11.5    11.5    11.5    11.5    11.5    11.5    11.5
   11.88   12.13   12.17   12.67   12.52   12.69   12.82   13.04   13.21    13.3
   12.29   12.95   12.25   11.48   11.99   11.57   12.04   10.41    9.55    7.75
     6.6     6.4    6.74    5.89    5.59    4.82    4.11    3.52    4.08    3.86
    4.77    3.96    4.33    3.47    4.59     4.7     9.2     9.2    5.52    6.25
    3.98    4.19    3.76    4.07    3.73    4.21    3.86    4.42    5.57    8.12
    10.9   11.87   11.97   12.24   12.51   12.68    12.5      13   12.59    13.3
  3597.5    3603  4062.8  4182.8  4222.8  4322.8  4342.8  4382.8  4422.8  4462.8
  4502.8  4522.8  4582.8  4602.8  4622.8  4640.7  4700.7  4720.7  4740.7  4760.7
  4780.7  4820.7  4840.7  4880.7  4900.7 4948.41  4948.5 5051.39  5051.5  5060.7
  5100.7  5120.7  5160.7  5180.7  5200.7  5260.7  5280.7  5300.7  5320.7  5378.2
  5440.7  5480.7  5487.8  5507.8  5527.8  5540.7  5560.7  5640.7  5700.7  5767.8
   12.29   12.96   12.26    11.5      12   11.58   12.05    11.5    11.5    11.5
    11.5    11.5    11.5    11.5    11.5    11.5    11.5    11.5    11.5    11.5
    11.5    11.5    11.5    11.5    11.5    11.5    11.5    11.5    11.5    11.5
    11.5    11.5    11.5    11.5    11.5    11.5    11.5    11.5    11.5    11.5
   11.88   12.13   12.17   12.67   12.52   12.69   12.82   13.04   13.21    13.3
   12.04    12.7      12   11.23   11.74   11.32   11.79   10.16     9.3     7.5
    6.35    6.15    6.49    5.64    5.34    4.57    3.86    3.27    3.83    3.61
    4.52    3.71    4.08    3.22    4.34    4.45    8.95    8.95    5.27       6
    3.73    3.94    3.51    3.82    3.48    3.96    3.61    4.17    5.32    7.87
   10.65   11.62   11.72   11.99   12.26   12.43   12.25   12.75   12.34   13.05
Pier Skew, UpSta & Num, DnSta & Num=,4966.3, 2 ,4966.3, 2 , 0 , 0 , 0 ,,
       1       1
   -2.27    10.2
       1       1
   -2.52    9.95
Pier Skew, UpSta & Num, DnSta & Num=,4988.8, 2 ,4988.8, 2 , 0 , 0 , 0 ,,
       1       1
   -2.27    10.2
       1       1
   -2.52    9.95
Pier Skew, UpSta & Num, DnSta & Num=,5011.3, 2 ,5011.3, 2 , 0 , 0 , 0 ,,
       1       1
   -2.27    10.2
       1       1
   -2.52    9.95
Pier Skew, UpSta & Num, DnSta & Num=,5033.8, 2 ,5033.8, 2 , 0 , 0 , 0 ,,
       1       1
   -2.27    10.2
       1       1
   -2.52    9.95
Abutment Skew #Up #Dn=, 2 , 2
 4948.30 4955.00
    9.20    4.72
 4948.30 4955.00
    8.95    4.47
Abutment Skew #Up #Dn=, 2 , 2
 5045.00 5051.59
    5.01    9.20
 5045.00 5051.59
    4.76    8.95
BR Coef= 1 , 1 , 0 ,1.25, 0 ,,,0.8,0,2,0,
Wspro=,,,, 1 ,,,, 0 ,,,, 0 ,,,,-1 ,-1 ,-1 , 0 , 0 , 0 , 0 , 0
BC Design=,, 0 ,, 0 ,,,,,,
BR U #Sta/Elev= 64
  3597.5   12.29    3603   12.95  3717.5   12.78  3817.5   12.62  3877.5   12.53
    3900    12.5  4062.8   12.25  4182.8   11.48  4222.8   11.99  4322.8   11.57
  4342.8   12.04  4382.8   10.41  4422.8    9.55  4462.8    7.75  4502.8     6.6
  4522.8     6.4  4582.8    6.74  4602.8    5.89  4622.8    5.59  4640.7    4.82
  4700.7    4.11  4720.7    3.52  4740.7    4.08  4760.7    3.86  4780.7    4.77
  4820.7    3.96  4840.7    4.33  4880.7    3.47  4900.7    4.59  4920.7    4.61
 4948.41     4.7  4948.5     4.7    4955    4.72  4958.5    4.73    4964   -1.27
    5000   -1.27    5036   -1.27  5041.5    4.73    5045    5.01 5051.39    5.51
  5051.5    5.52  5060.7    6.25  5100.7    3.98  5120.7    4.19  5160.7    3.76
  5180.7    4.07  5200.7    3.73  5260.7    4.21  5280.7    3.86  5300.7    4.42
  5320.7    5.57  5378.2    8.12  5440.7    10.9  5480.7   11.87  5487.8   11.97
  5507.8   12.24  5527.8   12.51  5540.7   12.68  5547.8   12.62  5560.7    12.5
  5640.7      13  5700.7   12.59  5727.8   12.88  5767.8    13.3
BR U #Mann= 3
 3597.50    0.14  4958.5   0.045  5041.5    0.14
BR U Banks=4958.50,5041.50
BR D #Sta/Elev= 64
  3597.5   12.04    3603    12.7  3717.5   12.53  3817.5   12.37  3877.5   12.28
    3900   12.25  4062.8      12  4182.8   11.23  4222.8   11.74  4322.8   11.32
  4342.8   11.79  4382.8   10.16  4422.8     9.3  4462.8     7.5  4502.8    6.35
  4522.8    6.15  4582.8    6.49  4602.8    5.64  4622.8    5.34  4640.7    4.57
  4700.7    3.86  4720.7    3.27  4740.7    3.83  4760.7    3.61  4780.7    4.52
  4820.7    3.71  4840.7    4.08  4880.7    3.22  4900.7    4.34  4920.7    4.36
 4948.41    4.45  4948.5    4.45    4955    4.47  4958.5    4.48    4964   -1.52
    5000   -1.52    5036   -1.52  5041.5    4.48    5045    4.76 5051.39    5.26
  5051.5    5.27  5060.7       6  5100.7    3.73  5120.7    3.94  5160.7    3.51
  5180.7    3.82  5200.7    3.48  5260.7    3.96  5280.7    3.61  5300.7    4.17
  5320.7    5.32  5378.2    7.87  5440.7   10.65  5480.7   11.62  5487.8   11.72
  5507.8   11.99  5527.8   12.26  5540.7   12.43  5547.8   12.37  5560.7   12.25
  5640.7   12.75  5700.7   12.34  5727.8   12.63  5767.8   13.05
BR D #Mann= 3
 3597.50    0.14  4958.5   0.045  5041.5    0.14
BR D Banks=4958.50,5041.50

Type RM Length L Ch R = 1 ,31620.7,625.45,625.45,625.45
XS GIS Cut Line= 4
 2724400.9189385 900749.00838700 2724575.8325045 901488.64289473
 2725120.8869860 902074.72298242 2725315.0796294 902652.88744334
BEGIN DESCRIPTION:
Downstream Section of Bridge/Culvert/Weir
END DESCRIPTION:
#Sta/Elev= 30
  3597.5   12.09    3603   12.75  4062.8   12.05  4182.8   11.28  4222.8   11.79
  4322.8   11.37  4342.8   11.84  4502.8     6.4  4582.8    6.54  4640.7    4.62
  4720.7    3.32  4740.7    3.88  4760.7    3.66  4780.7    4.57  4840.7    4.13
  4880.7    3.27  4900.7    4.39  4958.5    4.53    4964   -1.47    5036   -1.47
  5041.5    4.53  5060.7    6.05  5100.7    3.78  5280.7    3.66  5440.7    10.7
  5480.7   11.67  5540.7   12.48  5640.7    12.8  5700.7   12.39  5767.8    13.1
#Mann= 3 , 1 , 0
 3597.50    0.14       0  4958.5   0.045       0  5041.5    0.14       0
#XS Ineff= 2 , 0
       0 4938.34    11.5 5061.45       0    11.5
Bank Sta=4958.50,5041.50
Exp/Cntr=0.5,0.3

Type RM Length L Ch R = 1 ,30995.2,1000.5,1000.5,1000.5
XS GIS Cut Line= 3
 2723433.4107539 902230.02315002 2724578.4772936 902416.54982616
 2725511.1106743 903007.21763397
BEGIN DESCRIPTION:
Goodwin Mill 31.0
END DESCRIPTION:
#Sta/Elev= 30
  3799.6    14.4  3959.8   14.38  4019.8   12.96  4099.8   14.31  4179.8   13.65
  4239.8   14.69  4259.8   13.27  4339.8    11.3  4539.8    8.53  4619.8    8.85
  4679.8    6.63  4719.8     2.8  4919.8    3.64  4939.8    2.28  4983.7    6.33
    4987    0.65    4988   -1.35  5012.1   -1.35  5013.1    0.65  5063.7    5.11
  5123.7    3.43  5223.7    3.77  5283.7     5.7  5343.7    5.72  5383.7    8.84
  5443.7   10.16  5523.7    9.16  5683.7   13.71  5923.7   13.42  6063.7    14.9
#Mann= 3 , 1 , 0
 3799.60    0.14       0    4987   0.045       0  5013.1    0.14       0
Bank Sta=4987.00,5013.10
Exp/Cntr=0.3,0.1

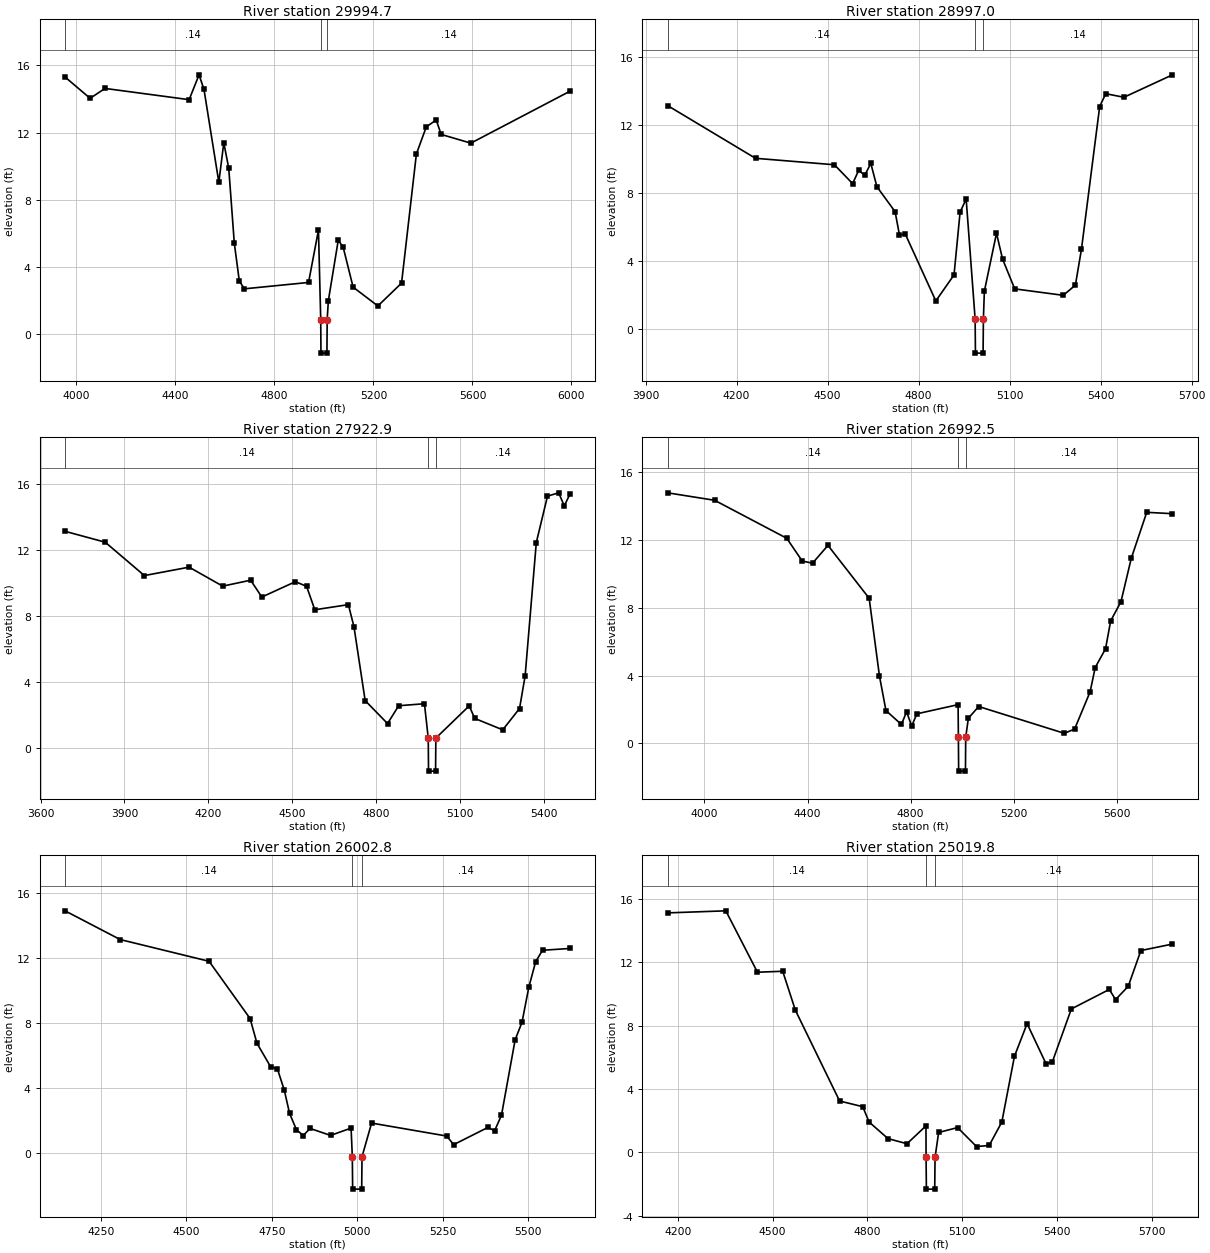
Type RM Length L Ch R = 1 ,29994.7,997.7,997.7,997.7
XS GIS Cut Line= 4
 2723347.0967437 902579.93475357 2723799.2441161 903089.70875188
 2724295.7196623 903431.03568988 2725040.4329815  903559.5873938
BEGIN DESCRIPTION:
Goodwin Mill 30.0
END DESCRIPTION:
#Sta/Elev= 30
    3954   15.31  4055.4   14.04  4115.4   14.63  4455.4   13.96  4495.4   15.44
  4515.4   14.57  4575.4    9.04  4595.4   11.39  4615.4    9.88  4637.9    5.41
  4657.9    3.18  4677.9    2.69  4937.9    3.07  4977.9    6.19    4987    0.86
    4988   -1.14  5012.1   -1.14  5013.1    0.86  5017.9    1.99  5057.9    5.59
  5077.9    5.16  5117.9    2.79  5217.9    1.67  5313.6    3.03  5373.6   10.73
  5413.6   12.34  5453.6   12.75  5473.6   11.89  5593.6   11.37  5993.6   14.46
#Mann= 3 , 1 , 0
 3954.00    0.14       0    4987   0.045       0  5013.1    0.14       0
Bank Sta=4987.00,5013.10
Exp/Cntr=0.3,0.1

Type RM Length L Ch R = 1 ,28997.0,1074.1,1074.1,1074.1
XS GIS Cut Line= 3
 2722593.5177897 904264.40535668 2723316.0670220 904064.92857473
 2724189.3320452  904335.3304347
BEGIN DESCRIPTION:
Goodwin Mill 29.0
END DESCRIPTION:
#Sta/Elev= 30
    3973   13.16  4262.6   10.06  4522.6    9.68  4582.6    8.57  4602.6    9.35
  4622.6    9.06  4642.6    9.76  4662.6    8.39  4722.6    6.92  4736.8    5.57
  4756.8    5.58  4856.8    1.67  4916.8     3.2  4936.8    6.89  4956.8    7.67
  4986.4     0.6  4987.4    -1.4  5012.6    -1.4  5013.6     0.6  5016.8    2.24
  5056.8    5.65  5076.8    4.13  5116.8    2.38  5276.8       2  5316.8     2.6
  5336.8    4.71  5396.8    13.1  5416.8   13.86  5476.8   13.65  5636.8   14.97
#Mann= 3 , 1 , 0
 3973.00    0.14       0  4986.4   0.045       0  5013.6    0.14       0
Bank Sta=4986.40,5013.60
Exp/Cntr=0.3,0.1

Type RM Length L Ch R = 1 ,27922.9,930.4,930.4,930.4
XS GIS Cut Line= 4
 2722566.9208854 904370.79297371 2723267.3060309 904876.13415464
 2723648.5283253 904955.92486742 2724189.3320452 905066.74530184
BEGIN DESCRIPTION:
Goodwin Mill 28.0
END DESCRIPTION:
#Sta/Elev= 30
  3687.6   13.12  3831.3   12.46  3971.3   10.44  4131.3   10.95  4251.3     9.8
  4351.3   10.16  4391.3    9.14  4511.3   10.07  4551.3    9.79  4580.8    8.37
  4700.8    8.68  4720.8    7.34  4760.8    2.87  4840.8    1.48  4880.8    2.56
  4972.8    2.68  4986.4     0.6  4987.4    -1.4  5012.6    -1.4  5013.6     0.6
  5132.8    2.55  5152.8    1.79  5252.8     1.1  5312.8    2.39  5332.8    4.36
  5372.8   12.44  5412.8   15.25  5452.8   15.45  5472.8   14.66  5492.8   15.36
#Mann= 3 , 1 , 0
 3687.60    0.14       0  4986.4   0.045       0  5013.6    0.14       0
Bank Sta=4986.40,5013.60
Exp/Cntr=0.3,0.1

Type RM Length L Ch R = 1 ,26992.5,989.7,989.7,989.7
XS GIS Cut Line= 4
 2722559.0364551 906140.19343501 2723288.8646937 905761.13535759
 2723752.7865198 905795.08085706 2724329.8600109 906140.19343501
BEGIN DESCRIPTION:
Goodwin Mill 27.0
END DESCRIPTION:
#Sta/Elev= 30
    3857   14.78  4039.4   14.34  4319.4    12.1  4379.4   10.76  4419.4   10.63
  4479.4   11.68  4639.4    8.56  4679.4    3.97  4704.6    1.94  4764.6    1.12
  4784.6    1.87  4804.6    1.03  4824.6    1.75  4984.6    2.29  4985.8    0.37
  4986.8   -1.63  5013.2   -1.63  5014.2    0.37  5024.6    1.49  5064.6    2.18
    5397     0.6    5437    0.85    5497    3.04    5517    4.48    5557    5.58
    5577    7.23    5617    8.36    5657   10.92    5717   13.63    5817   13.55
#Mann= 3 , 1 , 0
 3857.00    0.14       0  4985.8   0.045       0  5014.2    0.14       0
Bank Sta=4985.80,5014.20
Exp/Cntr=0.3,0.1

Type RM Length L Ch R = 1 ,26002.8,983,983,983
XS GIS Cut Line= 3
 2722858.8883671 907311.31316676 2723283.2071105 906830.41859092
 2723996.0625994 906394.78468105
BEGIN DESCRIPTION:
Goodwin Mill 26.0
END DESCRIPTION:
#Sta/Elev= 30
  4145.4    14.9  4306.8   13.13  4566.8   11.79  4686.8    8.26  4706.8    6.74
  4746.8    5.29  4766.8    5.15  4786.8    3.85  4802.2    2.42  4822.2    1.42
  4842.2    1.05  4862.2    1.49  4922.2    1.06  4982.2    1.51  4985.8   -0.25
  4986.8   -2.25  5013.2   -2.25  5014.2   -0.25  5042.2    1.82  5262.2    1.02
  5282.2    0.49  5382.2    1.55  5402.2    1.35  5422.2    2.31  5462.2    6.96
  5482.2    8.03  5502.2    10.2  5522.2   11.77  5542.2   12.47  5622.2   12.58
#Mann= 3 , 1 , 0
 4145.40    0.14       0  4985.8   0.045       0  5014.2    0.14       0
Bank Sta=4985.80,5014.20
Exp/Cntr=0.3,0.1

Type RM Length L Ch R = 1 ,25019.8,1020.9,1020.9,1020.9
XS GIS Cut Line= 3
 2723209.6585283 908188.23856976 2723639.6348549 907763.91982637
 2724307.2296779  907028.4340045
BEGIN DESCRIPTION:
Goodwin Mill 25.0
END DESCRIPTION:
#Sta/Elev= 30
  4168.1   15.13  4352.2   15.26  4452.2   11.38  4532.2   11.44  4572.2    8.98
  4712.2    3.24  4785.5    2.88  4805.5    1.91  4865.5    0.86  4925.5    0.54
  4985.5    1.67  4985.8   -0.33  4986.8   -2.33  5013.2   -2.33  5014.2   -0.33
  5025.5    1.25  5085.5    1.56  5145.5    0.36  5185.5    0.43  5225.5    1.91
  5265.5    6.07  5305.5    8.13  5365.5    5.59  5385.5    5.72  5445.5    9.06
  5565.5   10.29  5585.5    9.65  5625.5   10.49  5665.5   12.75  5765.5   13.16
#Mann= 3 , 1 , 0
 4168.10    0.14       0  4985.8   0.045       0  5014.2    0.14       0
Bank Sta=4985.80,5014.20
Exp/Cntr=0.3,0.1

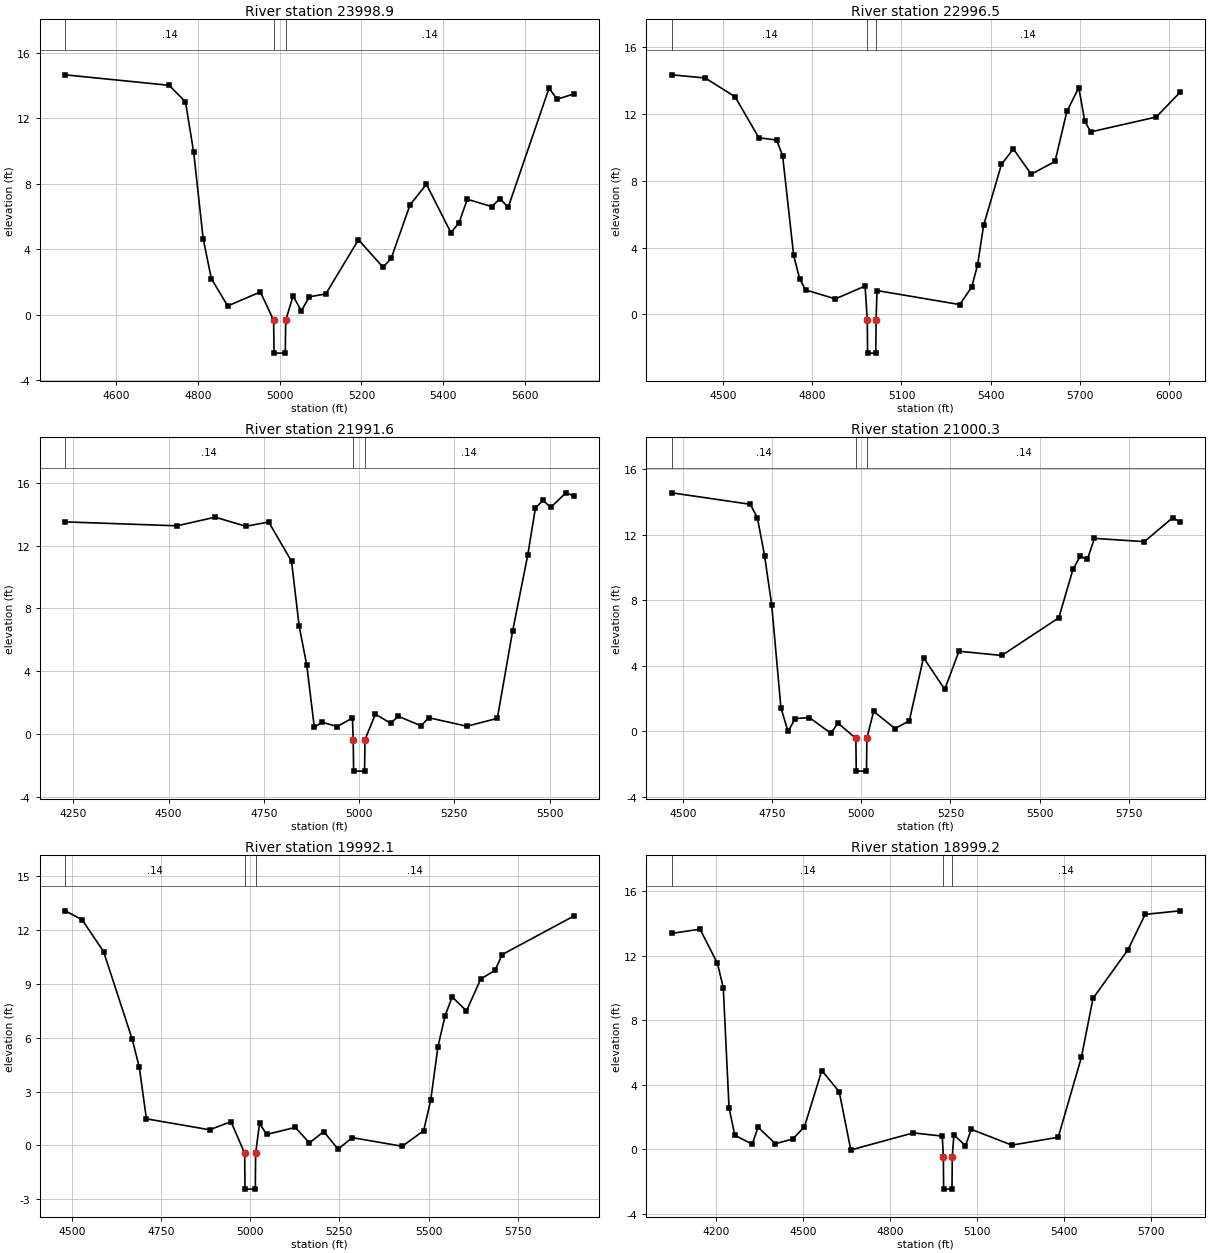
Type RM Length L Ch R = 1 ,23998.9,1002.4,1002.4,1002.4
XS GIS Cut Line= 4
 2724177.1052632 908369.28123361 2724454.3268422 908182.58098652
 2724906.9335019 908012.85348916 2725331.2522452 907973.25040644
BEGIN DESCRIPTION:
Goodwin Mill 24.0
END DESCRIPTION:
#Sta/Elev= 30
  4475.3   14.64  4729.6      14  4769.6   12.99  4789.6    9.92  4812.9    4.64
  4832.9     2.2  4872.9    0.54  4952.9    1.39  4985.3   -0.34  4986.3   -2.34
  5013.8   -2.34  5014.8   -0.34  5032.9    1.15  5052.9    0.24  5072.9     1.1
  5112.9    1.27  5192.9    4.58  5252.9     2.9  5272.9    3.44  5319.1    6.71
  5359.1    7.96  5419.1    5.01  5439.1    5.62  5459.1    7.05  5519.1     6.6
  5539.1    7.09  5559.1    6.55  5659.1   13.82  5679.1   13.15  5719.1   13.47
#Mann= 3 , 1 , 0
 4475.30    0.14       0  4985.3   0.045       0  5014.8    0.14       0
Bank Sta=4985.30,5014.80
Exp/Cntr=0.3,0.1

Type RM Length L Ch R = 1 ,22996.5,1004.9,1004.9,1004.9
XS GIS Cut Line= 4
 2723882.9109345 908821.88789322 2724267.6265952 908901.09405865
 2724680.6301721 909212.26113713 2725444.4039102 909444.22205018
BEGIN DESCRIPTION:
Goodwin Mill 23.0
END DESCRIPTION:
#Sta/Elev= 30
  4327.9   14.35  4440.7   14.16  4540.7   13.04  4620.7   10.58  4680.7   10.44
  4700.7     9.5  4737.8    3.53  4757.8    2.13  4777.8    1.46  4877.8    0.92
  4977.8    1.69  4985.2   -0.33  4986.2   -2.33  5013.8   -2.33  5014.8   -0.33
  5017.8    1.42    5296    0.58    5336    1.63    5356    2.97    5376    5.32
    5436    8.98    5476    9.91    5536    8.39    5616    9.16    5656   12.16
    5696   13.58    5716   11.57    5736   10.93    5956   11.82    6036    13.3
#Mann= 3 , 1 , 0
 4327.90    0.14       0  4985.2   0.045       0  5014.8    0.14       0
Bank Sta=4985.20,5014.80
Exp/Cntr=0.3,0.1

Type RM Length L Ch R = 1 ,21991.6,991.3,991.3,991.3
XS GIS Cut Line= 5
 2723312.0027150 909737.99868221 2723701.2858724 909795.97702479
 2723916.6340020 909842.91187355 2724068.4820421   909972.672926
 2724579.2436315 910072.06437043
BEGIN DESCRIPTION:
Goodwin Mill 22.0
END DESCRIPTION:
#Sta/Elev= 30
  4228.7   13.51  4522.3   13.26  4622.3   13.81  4702.7   13.23  4762.7    13.5
  4822.7      11  4842.7    6.87  4862.5    4.41  4882.5    0.43  4902.5    0.76
  4942.5    0.48  4982.5    1.02  4984.6   -0.36  4985.6   -2.36  5014.4   -2.36
  5015.4   -0.36  5042.8    1.27  5082.8    0.69  5102.8    1.13  5162.8    0.53
  5182.8    1.04  5282.8     0.5  5362.8       1  5402.8    6.54  5442.8   11.42
  5462.8    14.4  5482.8   14.88  5502.8   14.43  5542.8   15.36  5562.8   15.17
#Mann= 3 , 1 , 0
 4228.70    0.14       0  4984.6   0.045       0  5015.4    0.14       0
Bank Sta=4984.60,5015.40
Exp/Cntr=0.3,0.1

Type RM Length L Ch R = 1 ,21000.3,1008.2,1008.2,1008.2
XS GIS Cut Line= 4
 2722950.6899787 910783.83322056 2723220.4116423  910706.7698881
 2723682.7916371 910648.97238876 2724323.3805881 910875.34592786
BEGIN DESCRIPTION:
Goodwin Mill 21.0
END DESCRIPTION:
#Sta/Elev= 30
  4467.9   14.56  4688.4   13.86  4708.4   13.03  4728.4   10.73  4748.4    7.73
  4774.4    1.43  4794.4   -0.01  4814.4    0.78  4854.4    0.84  4914.4   -0.12
  4934.4     0.5  4984.6   -0.43  4985.6   -2.43  5014.4   -2.43  5015.4   -0.43
  5034.4    1.22  5094.4    0.17  5134.4    0.64  5174.4     4.5  5233.8    2.56
  5273.8    4.89  5393.8    4.63  5553.8    6.93  5593.8     9.9  5613.8   10.69
  5633.8   10.49  5653.8   11.78  5793.8   11.58  5873.8   13.05  5893.8   12.76
#Mann= 3 , 1 , 0
 4467.90    0.14       0  4984.6   0.045       0  5015.4    0.14       0
Bank Sta=4984.60,5015.40
Exp/Cntr=0.3,0.1

Type RM Length L Ch R = 1 ,19992.1,992.9,992.9,992.9
XS GIS Cut Line= 3
 2723095.1837271 910947.59280204 2723061.4685191 911313.64363122
 2723398.6205986 912315.46695318
BEGIN DESCRIPTION:
Goodwin Mill 20.0
END DESCRIPTION:
#Sta/Elev= 30
  4481.7   13.08  4529.3   12.58  4589.3    10.8  4669.3    5.93  4689.3    4.36
  4709.3    1.48  4886.3    0.87  4946.3    1.32  4984.6   -0.44  4985.6   -2.44
  5014.4   -2.44  5015.4   -0.44  5026.3    1.22  5046.3    0.61  5126.3       1
  5166.3    0.14  5206.3    0.77  5246.3   -0.21  5286.3    0.43  5426.3   -0.05
  5486.3    0.82  5506.3    2.55  5526.3     5.5  5546.3    7.23  5566.3    8.28
  5606.3     7.5  5646.3    9.28  5686.3    9.76  5706.3   10.64  5906.3   12.78
#Mann= 3 , 1 , 0
 4481.70    0.14       0  4984.6   0.045       0  5015.4    0.14       0
Bank Sta=4984.60,5015.40
Exp/Cntr=0.3,0.1

Type RM Length L Ch R = 1 ,18999.2,989,989,989
XS GIS Cut Line= 3
 2722698.6404672 910843.18898582 2722271.5339463 911493.34002317
 2721910.8662175 912399.75497306
BEGIN DESCRIPTION:
Goodwin Mill 19.0
END DESCRIPTION:
#Sta/Elev= 30
  4047.5    13.4  4145.4   13.66  4205.4   11.54  4225.4   10.04  4245.4    2.57
  4265.4    0.87  4325.4    0.32  4345.4    1.37  4405.4    0.35  4465.4    0.64
  4505.4     1.4  4565.4    4.89  4625.4    3.57  4665.4   -0.04  4880.9    1.02
  4980.9    0.82  4984.6   -0.47  4985.6   -2.47  5014.4   -2.47  5015.4   -0.47
  5020.9     0.9  5060.9    0.22  5080.9    1.24  5220.9    0.26  5380.9    0.75
  5460.9    5.72  5500.9    9.37  5620.9   12.37  5680.9   14.58  5800.9    14.8
#Mann= 3 , 1 , 0
 4047.50    0.14       0  4984.6   0.045       0  5015.4    0.14       0
Bank Sta=4984.60,5015.40
Exp/Cntr=0.3,0.1

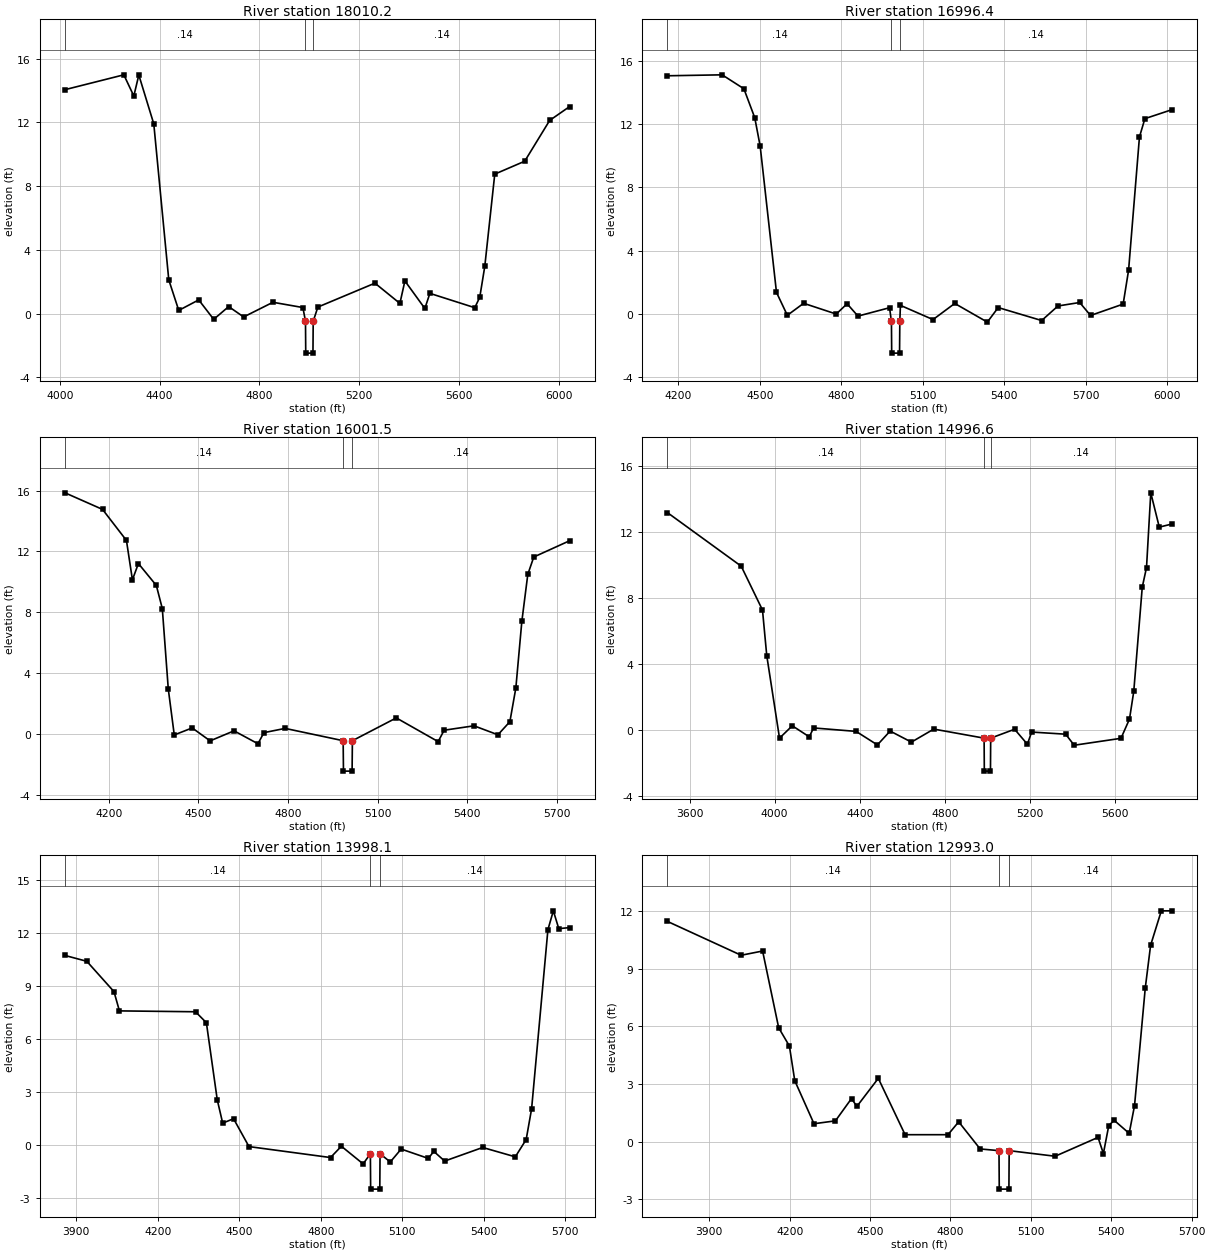
Type RM Length L Ch R = 1 ,18010.2,1013.8,1013.8,1013.8
XS GIS Cut Line= 4
 2722385.4290185 910572.68818926 2721749.5148652 910980.81219811
 2721474.2684406 911208.60234258 2721047.1619197 912010.61347625
BEGIN DESCRIPTION:
Goodwin Mill 18.0
END DESCRIPTION:
#Sta/Elev= 30
  4021.3   14.05  4256.9   14.98  4296.9   13.65  4316.9   14.97  4376.9    11.9
  4436.9    2.12  4476.9     0.2  4556.9    0.86  4616.9   -0.36  4676.9    0.44
  4736.9   -0.21  4854.2    0.71  4974.2    0.38  4984.6   -0.48  4985.6   -2.48
  5014.5   -2.48  5015.5   -0.48  5034.2    0.41  5262.8    1.91  5362.8    0.64
  5382.8    2.05  5462.8    0.32  5482.8    1.27  5662.8    0.37  5682.8    1.03
  5702.8    2.96  5742.8    8.75  5862.8    9.56  5962.8   12.12  6042.8   12.99
#Mann= 3 , 1 , 0
 4021.30    0.14       0  4984.6   0.045       0  5015.5    0.14       0
Bank Sta=4984.60,5015.50
Exp/Cntr=0.3,0.1

Type RM Length L Ch R = 1 ,16996.4,994.9,994.9,994.9
XS GIS Cut Line= 3
 2720278.3290351 910219.86583398 2720660.6126879  910807.9945307
 2720895.8641666 911940.14227187
BEGIN DESCRIPTION:
Goodwin Mill 17.0
END DESCRIPTION:
#Sta/Elev= 30
  4159.9   15.05  4361.4   15.11  4441.4   14.23  4481.4    12.4  4501.4    10.6
  4561.4    1.36  4601.4   -0.09  4661.4    0.67  4781.4   -0.01  4821.4    0.64
  4861.4   -0.14  4977.7    0.39  4984.6   -0.48  4985.6   -2.48  5014.5   -2.48
  5015.5   -0.48  5017.7    0.54  5137.7   -0.36  5217.7    0.66  5337.7   -0.52
  5377.7     0.4  5537.7   -0.42  5597.7     0.5  5677.7    0.72  5717.7    -0.1
  5837.7    0.62  5857.7    2.76  5897.7   11.18  5917.7   12.34  6017.7   12.91
#Mann= 3 , 1 , 0
 4159.90    0.14       0  4984.6   0.045       0  5015.5    0.14       0
Bank Sta=4984.60,5015.50
Exp/Cntr=0.3,0.1

Type RM Length L Ch R = 1 ,16001.5,1004.9,1004.9,1004.9
XS GIS Cut Line= 4
 2719249.1038158 911256.44266194 2719837.2325125 911646.07792352
 2720168.0549044 911653.42953222 2720734.1287750 911976.90031542
BEGIN DESCRIPTION:
Goodwin Mill 16.0
END DESCRIPTION:
#Sta/Elev= 30
    4054   15.85  4179.5   14.76  4259.5   12.72  4279.5   10.13  4299.5    11.2
  4359.5    9.76  4379.5    8.24  4399.5    2.95  4419.5   -0.07  4479.5    0.39
  4539.5   -0.46  4619.5     0.2  4699.5   -0.65  4719.5    0.08  4790.4    0.36
  4984.6   -0.45  4985.6   -2.45  5014.5   -2.45  5015.5   -0.45  5162.4    1.05
  5302.4   -0.51  5322.4    0.24  5422.4    0.53  5502.4   -0.06  5542.4     0.8
  5562.4    3.02  5582.4    7.39  5602.4   10.49  5622.4   11.63  5742.4    12.7
#Mann= 3 , 1 , 0
 4054.00    0.14       0  4984.6   0.045       0  5015.5    0.14       0
Bank Sta=4984.60,5015.50
Exp/Cntr=0.3,0.1

Type RM Length L Ch R = 1 ,14996.6,998.5,998.5,998.5
XS GIS Cut Line= 3
 2717984.6271179 912021.00996767 2719168.2361200 912109.22927218
 2720079.8355999  912866.4449692
BEGIN DESCRIPTION:
Goodwin Mill 15.0
END DESCRIPTION:
#Sta/Elev= 30
  3495.9   13.19  3842.8    9.94  3942.8    7.28  3962.8    4.52  4022.8   -0.49
  4082.8    0.26  4162.8   -0.41  4182.8    0.13  4382.8   -0.08  4482.8    -0.9
  4542.8   -0.06  4642.8   -0.73  4747.9    0.06  4984.5   -0.49  4985.5   -2.49
  5014.4   -2.49  5015.4   -0.49  5127.9    0.05  5187.9   -0.86  5207.9   -0.12
  5367.9   -0.25  5407.9   -0.92  5627.9    -0.5  5667.9    0.67  5687.9    2.34
  5727.9    8.67  5747.9    9.86  5767.9   14.39  5807.9   12.31  5867.9    12.5
#Mann= 3 , 1 , 0
 3495.90    0.14       0  4984.5   0.045       0  5015.4    0.14       0
Bank Sta=4984.50,5015.40
Exp/Cntr=0.3,0.1

Type RM Length L Ch R = 1 ,13998.1,1005.1,1005.1,1005.1
XS GIS Cut Line= 3
 2717933.1658569  913028.1803608 2718587.4590320  913116.3996653
 2719763.7164254 913336.94792657
BEGIN DESCRIPTION:
Goodwin Mill 14.0
END DESCRIPTION:
#Sta/Elev= 30
  3858.5   10.74  3938.7   10.41  4038.7    8.69  4058.7     7.6  4338.7    7.55
  4378.7    6.93  4418.7    2.56  4438.7    1.24  4478.7    1.49  4535.5   -0.09
  4835.5   -0.71  4875.5   -0.07  4955.5   -1.07  4982.2    -0.5  4983.2    -2.5
  5016.8    -2.5  5017.8    -0.5  5055.5   -0.96  5095.5   -0.23  5195.5   -0.76
  5215.5   -0.36  5255.5   -0.91  5395.5   -0.14  5515.5   -0.67  5555.5    0.31
  5575.5    2.05  5635.5    12.2  5655.5   13.27  5675.5   12.26  5715.5   12.32
#Mann= 3 , 1 , 0
 3858.50    0.14       0  4982.2   0.045       0  5017.8    0.14       0
Bank Sta=4982.20,5017.80
Exp/Cntr=0.3,0.1

Type RM Length L Ch R = 1 ,12993.0,991.5,991.5,991.5
XS GIS Cut Line= 4
 2718366.9107707 914608.77623322 2718837.4137281 914542.61175484
 2719719.6067732 913741.28640556 2719785.7712516 913535.44136171
BEGIN DESCRIPTION:
Goodwin Mill 13.0
END DESCRIPTION:
#Sta/Elev= 30
  3743.6   11.45  4018.8    9.69  4098.8    9.91  4158.8    5.92  4198.8    4.97
  4218.8    3.17  4290.6    0.93  4370.6    1.08  4430.6    2.24  4450.6    1.83
  4530.6    3.29  4630.6    0.36  4790.6    0.36  4830.6    1.03  4910.6   -0.38
    4981   -0.47    4982   -2.47    5018   -2.47    5019   -0.47  5190.6   -0.76
  5350.6    0.22  5370.6   -0.62  5390.6    0.83  5410.6    1.11  5466.8    0.43
  5486.8    1.87  5526.8    7.98  5546.8   10.21  5586.8      12  5626.8      12
#Mann= 3 , 1 , 0
 3743.60    0.14       0    4981   0.045       0    5019    0.14       0
Bank Sta=4981.00,5019.00
Exp/Cntr=0.3,0.1