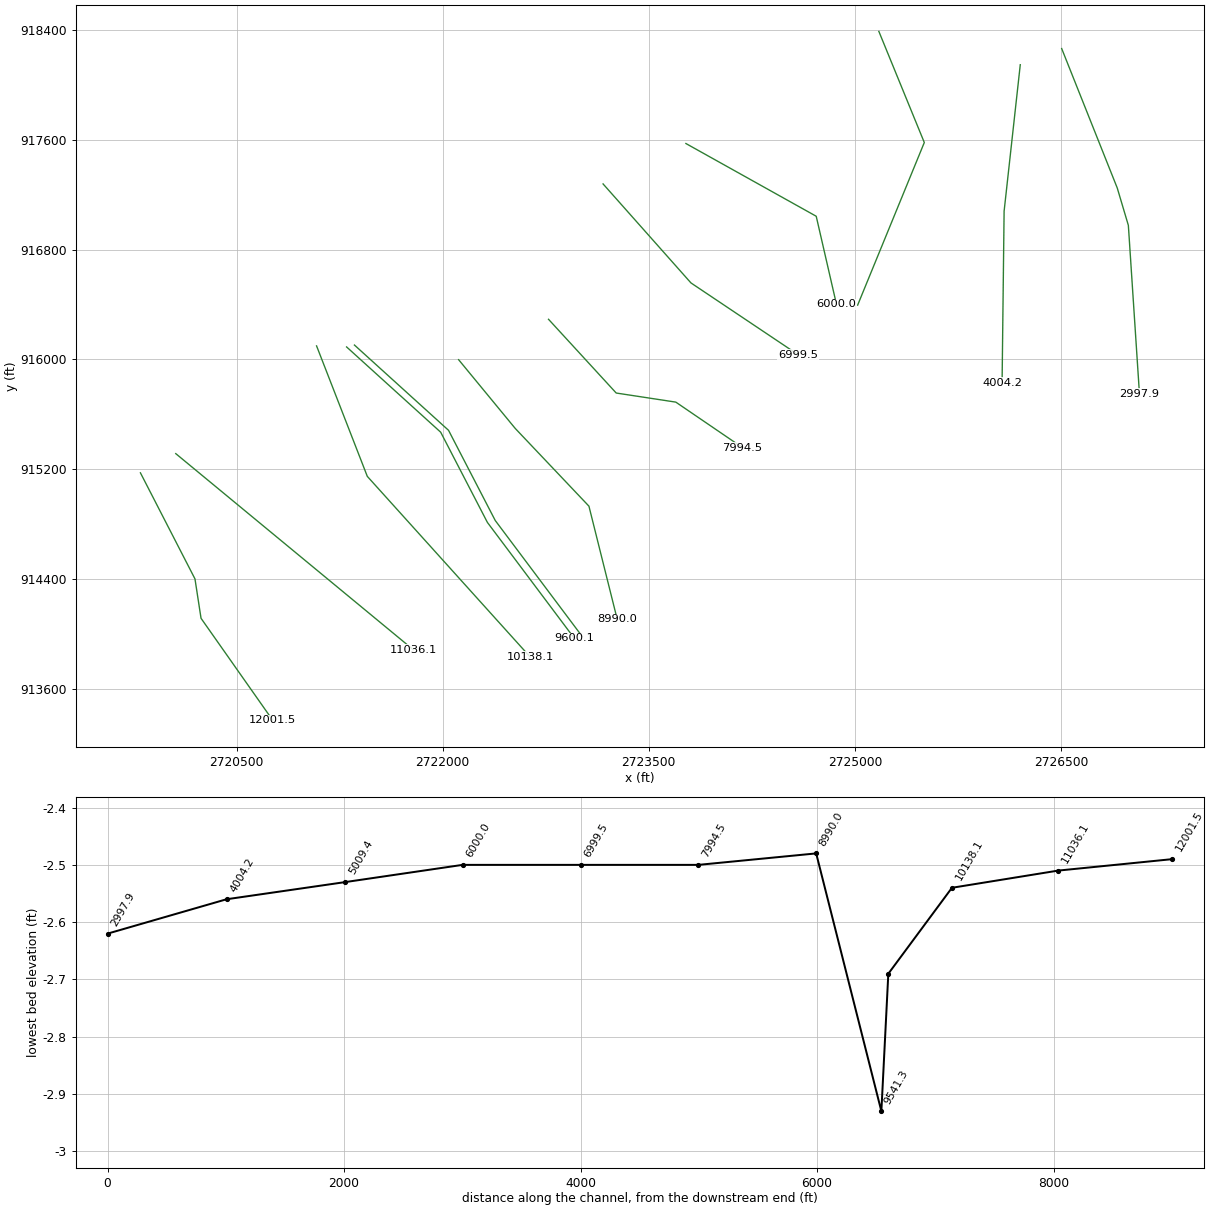
HEC-RAS study GOODWIN MILL CREEK.PRJ: Goodwin Mill Creek

--- GOODWIN MILL CREEK.g01 (geometry) --- (continued)

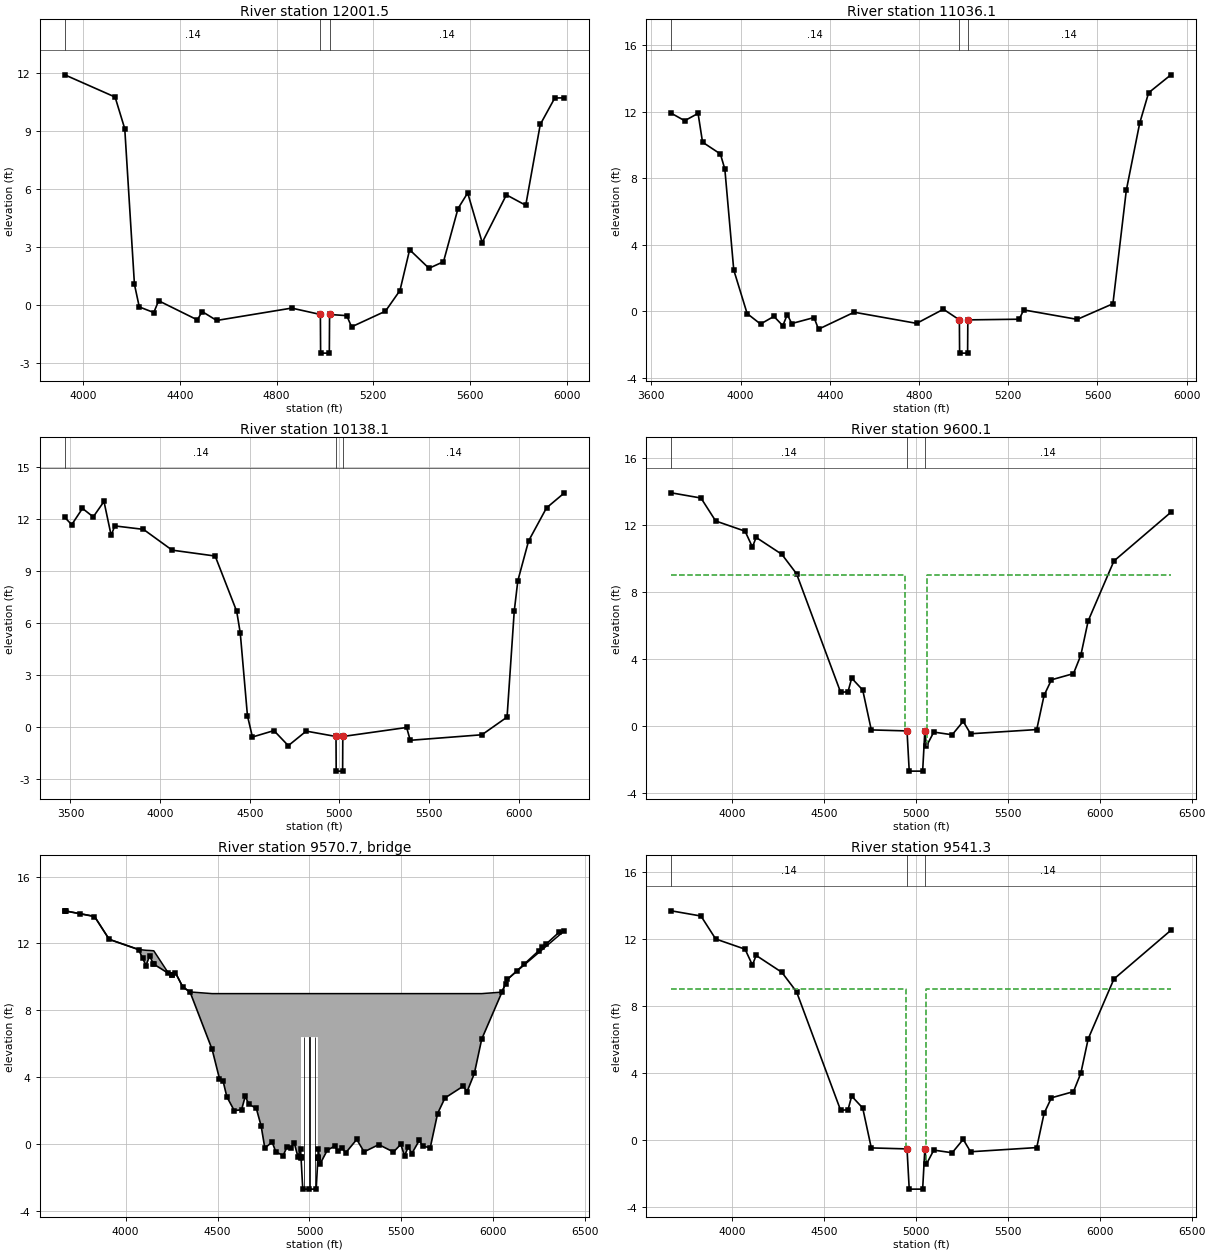
Type RM Length L Ch R = 1 ,12001.5,965.4,965.4,965.4
XS GIS Cut Line= 4
 2719800.4744690 915174.85010381 2720197.4613393 914402.93118937
 2720241.5709915 914116.21844972 2720763.5352099 913373.70597012
BEGIN DESCRIPTION:
Goodwin Mill 12.0
END DESCRIPTION:
#Sta/Elev= 30
  3924.3   11.91  4132.3   10.76  4172.3    9.12  4212.3    1.07  4232.3    -0.1
  4292.3   -0.39  4312.3    0.22  4472.3   -0.77  4492.3   -0.34  4552.3    -0.8
  4862.4   -0.16    4981   -0.49    4982   -2.49    5018   -2.49    5019   -0.49
    5090   -0.55    5110   -1.13    5250   -0.32    5310    0.75    5350    2.86
    5430     1.9    5490    2.24    5550    4.99    5590     5.8    5650    3.23
    5750     5.7    5830    5.16    5890    9.34    5950   10.71    5990   10.72
#Mann= 3 , 1 , 0
 3924.30    0.14       0    4981   0.045       0    5019    0.14       0
Bank Sta=4981.00,5019.00
Exp/Cntr=0.3,0.1

Type RM Length L Ch R = 1 ,11036.1,898,898,898
XS GIS Cut Line= 2
 2720057.7807738 915314.53066928 2721785.4088204 913888.31857974
BEGIN DESCRIPTION:
Goodwin Mill 11.0
END DESCRIPTION:
#Sta/Elev= 30
  3689.1   11.92  3749.4   11.47  3809.4   11.91  3829.4   10.18  3909.4    9.47
  3929.4    8.56  3969.4    2.49  4029.4   -0.13  4089.4   -0.76  4149.4    -0.3
  4189.4   -0.86  4209.4   -0.19  4229.4   -0.73  4329.4   -0.37  4349.4   -1.07
  4509.4   -0.05  4789.4   -0.72  4909.4    0.13    4981   -0.51    4982   -2.51
  5017.9   -2.51  5018.9   -0.51  5249.4   -0.47  5269.4    0.09  5509.4   -0.48
  5669.4    0.46  5729.4    7.28  5789.4   11.32  5829.4   13.15  5929.4   14.23
#Mann= 3 , 1 , 0
 3689.10    0.14       0    4981   0.045       0  5018.9    0.14       0
Bank Sta=4981.00,5018.90
Exp/Cntr=0.3,0.1

Type RM Length L Ch R = 1 ,10138.1,538,538,538
XS GIS Cut Line= 3
 2721082.4142320 916098.58112857 2721451.6446873  915149.1313865
 2722635.5264644 913836.31199006
BEGIN DESCRIPTION:
Goodwin Mill 10.0
END DESCRIPTION:
#Sta/Elev= 30
  3468.4   12.11  3507.1   11.69  3567.1   12.63  3627.1   12.14  3687.1   13.03
  3727.1   11.07  3747.1   11.62  3907.1   11.42  4067.1   10.22  4307.1    9.88
  4427.1    6.69  4447.1    5.43  4487.1    0.66  4514.9   -0.57  4634.9    -0.2
  4714.9   -1.07  4814.9   -0.23    4981   -0.54    4982   -2.54  5017.9   -2.54
  5018.9   -0.54  5374.9   -0.02  5394.9   -0.76  5794.9   -0.44  5934.9    0.58
  5974.9    6.69  5994.9    8.45  6054.9   10.75  6154.9   12.66  6254.9   13.53
#Mann= 3 , 1 , 0
 3468.40    0.14       0    4981   0.045       0  5018.9    0.14       0
Bank Sta=4981.00,5018.90
Exp/Cntr=0.3,0.1

Type RM Length L Ch R = 1 ,9600.1,58.8,58.8,58.8
XS GIS Cut Line= 4
 2721300.8985664 916091.06376687 2721985.6954132 915470.46662445
 2722325.6218641 914814.05692623 2722958.5883588 913970.10159994
BEGIN DESCRIPTION:
Upstream Section of Bridge/Culvert/Weir
END DESCRIPTION:
#Sta/Elev= 30
  3668.8   13.92  3830.5   13.61  3910.5   12.24  4070.5   11.63  4110.5   10.68
  4130.5   11.26  4270.5   10.25  4350.5    9.09  4590.5    2.01  4630.5    2.05
  4650.5    2.86  4710.5    2.15  4757.1   -0.23  4951.5   -0.29  4963.5   -2.69
  5036.5   -2.69  5048.5   -0.29  5057.1    -1.2  5097.1   -0.36  5197.1   -0.52
  5257.1    0.28  5297.1   -0.46  5657.1   -0.21  5697.1    1.83  5737.1    2.76
  5857.1    3.13  5897.1    4.23  5937.1    6.28  6077.1    9.85  6387.1   12.76
#Mann= 3 , 1 , 0
 3668.80    0.14       0  4951.5   0.045       0  5048.5    0.14       0
#XS Ineff= 2 , 0
       0  4941.5       9  5058.5       0       9
Bank Sta=4951.50,5048.50
Exp/Cntr=0.5,0.3

Type RM Length L Ch R = 3 ,9570.7,,,
BEGIN DESCRIPTION:
Beech Springs Rd - TOR
Structure ID: 112
Approximate Survey Structure
END DESCRIPTION:
Bridge Culvert--1,0,-1,-1, 0
Deck Dist Width WeirC Skew NumUp NumDn MinLoCord MaxHiCord MaxSubmerge Is_Ogee
10,38.8,2.6,, 60, 60,,,0.95,0,1,1,,
  3668.8  3670.5  3830.5  3910.5  4070.5  4110.5  4130.5    4153    4233  4270.5
  4310.5  4350.5  4470.5  4510.5  4530.5  4550.5  4590.5  4630.5  4650.5  4670.5
  4710.5  4737.1  4757.1  4797.1  4817.1  4857.1  4877.1  4897.1  4917.1  4937.1
  4951.5 4953.91    4954 5045.89    5046  5048.5  5057.1  5097.1  5137.1  5197.1
  5257.1  5297.1  5377.1  5457.1  5497.1  5517.1  5537.1  5557.1  5597.1  5617.1
  5657.1  5697.1  5737.1  5837.1  5857.1  5897.1  5937.1  6046.9  6077.1  6387.1
   13.92   13.95   13.62   12.25   11.64   11.59   11.58   11.56   10.22   10.26
    9.41     9.1       9       9       9       9       9       9       9       9
       9       9       9       9       9       9       9       9       9       9
       9       9       9       9       9       9       9       9       9       9
       9       9       9       9       9       9       9       9       9       9
       9       9       9       9       9       9       9    9.09    9.86   12.76
   13.92   13.95   13.61   12.24   11.63   10.68   11.26   10.76   10.21   10.25
     9.4    9.09    5.66    3.91    3.75    2.83    2.01    2.05    2.86    2.38
    2.15    1.08   -0.23    0.12   -0.47   -0.68   -0.18   -0.25    0.08   -0.76
   -0.29   -0.77     6.4     6.4   -0.79   -0.29    -1.2   -0.36   -0.12   -0.52
    0.28   -0.46   -0.03   -0.47   -0.01   -0.71   -0.17   -0.56    0.22   -0.13
   -0.21    1.83    2.76    3.47    3.13    4.23    6.28    9.08    9.85   12.76
  3668.8  3670.5  3830.5  3910.5  4070.5  4110.5  4130.5    4153    4233  4270.5
  4310.5  4350.5  4470.5  4510.5  4530.5  4550.5  4590.5  4630.5  4650.5  4670.5
  4710.5  4737.1  4757.1  4797.1  4817.1  4857.1  4877.1  4897.1  4917.1  4937.1
  4951.5 4953.91    4954 5045.89    5046  5048.5  5057.1  5097.1  5137.1  5197.1
  5257.1  5297.1  5377.1  5457.1  5497.1  5517.1  5537.1  5557.1  5597.1  5617.1
  5657.1  5697.1  5737.1  5837.1  5857.1  5897.1  5937.1  6046.9  6077.1  6387.1
   13.92   13.95   13.62   12.25   11.64   11.59   11.58   11.56   10.22   10.26
    9.41     9.1       9       9       9       9       9       9       9       9
       9       9       9       9       9       9       9       9       9       9
       9       9       9       9       9       9       9       9       9       9
       9       9       9       9       9       9       9       9       9       9
       9       9       9       9       9       9       9    9.09    9.86   12.76
   13.67    13.7   13.36   11.99   11.38   10.43   11.01   10.51    9.96      10
    9.15    8.84    5.41    3.66     3.5    2.58    1.76     1.8    2.61    2.13
     1.9    0.83   -0.48   -0.13   -0.72   -0.93   -0.43    -0.5   -0.17   -1.01
   -0.54   -1.02    6.15    6.15   -1.04   -0.54   -1.45   -0.61   -0.37   -0.77
    0.03   -0.71   -0.28   -0.72   -0.26   -0.96   -0.42   -0.81   -0.03   -0.38
   -0.46    1.58    2.51    3.22    2.88    3.98    6.03    8.83     9.6   12.51
Pier Skew, UpSta & Num, DnSta & Num=,4969.4, 2 ,4969.4, 2 , 0 , 0 , 0 ,,
       1       1
   -3.69     7.4
       1       1
   -3.94    7.15
Pier Skew, UpSta & Num, DnSta & Num=,5000.0, 2 ,5000.0, 2 , 0 , 0 , 0 ,,
       1       1
   -3.69     7.4
       1       1
   -3.94    7.15
Pier Skew, UpSta & Num, DnSta & Num=,5030.7, 2 ,5030.7, 2 , 0 , 0 , 0 ,,
       1       1
   -3.69     7.4
       1       1
   -3.94    7.15
BR Coef= 1 , 1 , 0 ,1.25, 0 ,,,0.8,0,2,0,
Wspro=,,,, 1 ,,,, 0 ,,,, 0 ,,,,-1 ,-1 ,-1 , 0 , 0 , 0 , 0 , 0
BC Design=,, 0 ,, 0 ,,,,,,
BR U #Sta/Elev= 80
  3668.8   13.92  3670.5   13.95    3673   13.94    3753   13.77  3830.5   13.61
  3910.5   12.24  4070.5   11.63    4093    11.1  4110.5   10.68  4130.5   11.26
  4150.5   10.78    4153   10.76    4233   10.21  4250.5   10.09  4252.9   10.11
  4270.5   10.25  4310.5     9.4  4350.5    9.09  4470.5    5.66  4510.5    3.91
  4530.5    3.75  4550.5    2.83  4590.5    2.01  4630.5    2.05  4650.5    2.86
  4670.5    2.38  4710.5    2.15  4737.1    1.08  4757.1   -0.23  4797.1    0.12
  4817.1   -0.47  4857.1   -0.68  4877.1   -0.18  4897.1   -0.25  4917.1    0.08
  4937.1   -0.76  4951.5   -0.29 4953.91   -0.77    4954   -0.79  4954.1   -0.81
  4963.5   -2.69    5000   -2.69  5036.5   -2.69  5045.8   -0.83 5045.89   -0.81
    5046   -0.79  5048.5   -0.29  5057.1    -1.2  5097.1   -0.36  5137.1   -0.12
  5157.1   -0.44  5177.1   -0.22  5197.1   -0.52  5257.1    0.28  5297.1   -0.46
  5377.1   -0.03  5457.1   -0.47  5497.1   -0.01  5517.1   -0.71  5537.1   -0.17
  5557.1   -0.56  5597.1    0.22  5617.1   -0.13  5657.1   -0.21  5697.1    1.83
  5737.1    2.76  5837.1    3.47  5857.1    3.13  5897.1    4.23  5937.1    6.28
  6046.9    9.08  6067.1     9.6  6077.1    9.85  6127.1   10.35  6167.1   10.75
  6247.1   11.56  6267.1   11.76  6287.1   11.96  6357.1   12.66  6387.1   12.76
BR U #Mann= 3
 3668.80    0.14  4951.5   0.045  5048.5    0.14
BR U Banks=4951.50,5048.50
BR D #Sta/Elev= 80
  3668.8   13.67  3670.5    13.7    3673   13.69    3753   13.52  3830.5   13.36
  3910.5   11.99  4070.5   11.38    4093   10.85  4110.5   10.43  4130.5   11.01
  4150.5   10.53    4153   10.51    4233    9.96  4250.5    9.84  4252.9    9.86
  4270.5      10  4310.5    9.15  4350.5    8.84  4470.5    5.41  4510.5    3.66
  4530.5     3.5  4550.5    2.58  4590.5    1.76  4630.5     1.8  4650.5    2.61
  4670.5    2.13  4710.5     1.9  4737.1    0.83  4757.1   -0.48  4797.1   -0.13
  4817.1   -0.72  4857.1   -0.93  4877.1   -0.43  4897.1    -0.5  4917.1   -0.17
  4937.1   -1.01  4951.5   -0.54 4953.91   -1.02    4954   -1.04  4954.1   -1.06
  4963.5   -2.94    5000   -2.94  5036.5   -2.94  5045.8   -1.08 5045.89   -1.06
    5046   -1.04  5048.5   -0.54  5057.1   -1.45  5097.1   -0.61  5137.1   -0.37
  5157.1   -0.69  5177.1   -0.47  5197.1   -0.77  5257.1    0.03  5297.1   -0.71
  5377.1   -0.28  5457.1   -0.72  5497.1   -0.26  5517.1   -0.96  5537.1   -0.42
  5557.1   -0.81  5597.1   -0.03  5617.1   -0.38  5657.1   -0.46  5697.1    1.58
  5737.1    2.51  5837.1    3.22  5857.1    2.88  5897.1    3.98  5937.1    6.03
  6046.9    8.83  6067.1    9.35  6077.1     9.6  6127.1    10.1  6167.1    10.5
  6247.1   11.31  6267.1   11.51  6287.1   11.71  6357.1   12.41  6387.1   12.51
BR D #Mann= 3
 3668.80    0.14  4951.5   0.045  5048.5    0.14
BR D Banks=4951.50,5048.50

Type RM Length L Ch R = 1 ,9541.3,551.3,551.3,551.3
XS GIS Cut Line= 4
 2721358.0708829 916104.80298917 2722042.8677297 915484.20584676
 2722382.7941806 914827.79614854 2723015.7606753 913983.84082225
BEGIN DESCRIPTION:
Downstream Section of Bridge/Culvert/Weir
END DESCRIPTION:
#Sta/Elev= 30
  3668.8   13.68  3830.5   13.37  3910.5      12  4070.5   11.39  4110.5   10.44
  4130.5   11.02  4270.5   10.01  4350.5    8.85  4590.5    1.77  4630.5    1.81
  4650.5    2.62  4710.5    1.91  4757.1   -0.47  4951.5   -0.53  4963.5   -2.93
  5036.5   -2.93  5048.5   -0.53  5057.1   -1.44  5097.1    -0.6  5197.1   -0.76
  5257.1    0.04  5297.1    -0.7  5657.1   -0.45  5697.1    1.59  5737.1    2.52
  5857.1    2.89  5897.1    3.99  5937.1    6.04  6077.1    9.61  6387.1   12.52
#Mann= 3 , 1 , 0
 3668.80    0.14       0  4951.5   0.045       0  5048.5    0.14       0
#XS Ineff= 2 , 0
       0 4944.83       9 5055.17       0       9
Bank Sta=4951.50,5048.50
Exp/Cntr=0.5,0.3

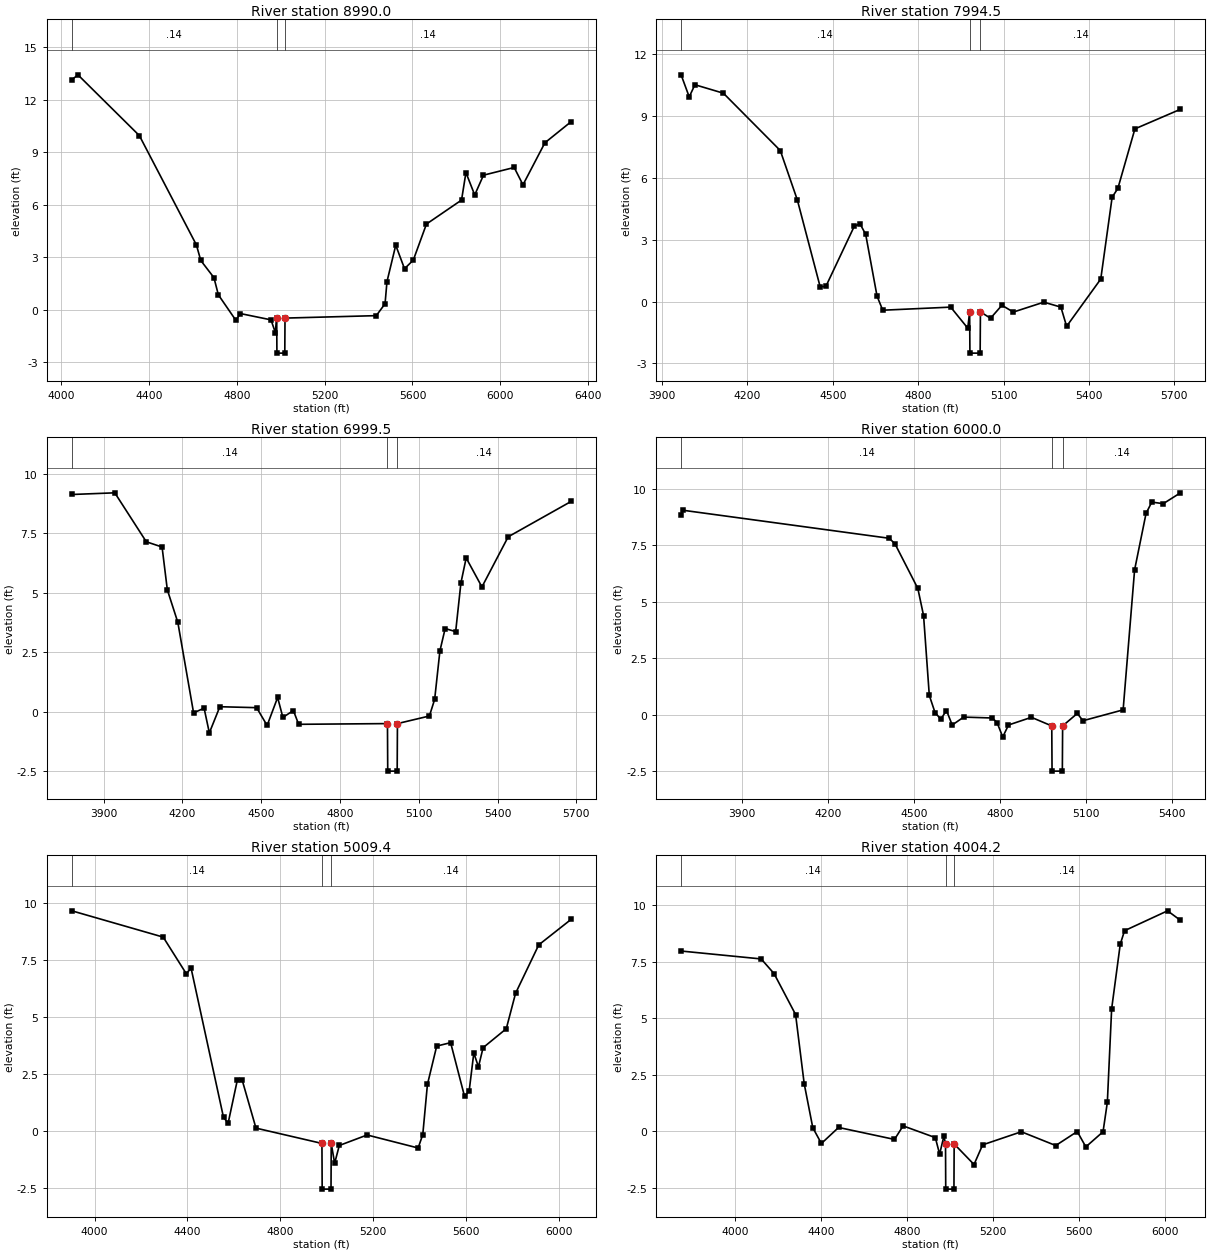
Type RM Length L Ch R = 1 ,8990.0,995.5,995.5,995.5
XS GIS Cut Line= 4
 2722116.2312123 915998.23027921 2722527.9213000   915498.320887
 2723064.5887358 914932.24701641 2723270.4337796 914108.86684101
BEGIN DESCRIPTION:
Goodwin Mill 9.0
END DESCRIPTION:
#Sta/Elev= 30
  4047.4   13.13    4075   13.41    4355    9.94    4615     3.7    4635    2.81
    4695    1.83  4715.1    0.85  4795.1   -0.61  4815.1   -0.22  4955.1   -0.58
  4975.1   -1.31  4981.1   -0.48  4982.1   -2.48    5018   -2.48    5019   -0.48
  5435.1   -0.34  5475.1    0.34  5483.8     1.6  5523.8    3.68  5563.8    2.34
  5603.8    2.83  5663.8    4.89  5823.8    6.26  5843.8    7.83  5883.8    6.55
  5923.8    7.68  6063.8    8.12  6103.8    7.13  6203.8    9.53  6323.8   10.74
#Mann= 3 , 1 , 0
 4047.40    0.14       0  4981.1   0.045       0    5019    0.14       0
Bank Sta=4981.10,5019.00
Exp/Cntr=0.3,0.1

Type RM Length L Ch R = 1 ,7994.5,995,995,995
XS GIS Cut Line= 4
 2722770.5243874 916292.29462757 2723263.0821709 915755.62719182
 2723696.8270847 915689.46271344 2724182.0332595 915358.64032153
BEGIN DESCRIPTION:
Goodwin Mill 8.0
END DESCRIPTION:
#Sta/Elev= 30
  3967.2   10.99  3995.7    9.92  4015.7   10.51  4115.7    10.1  4315.7    7.32
  4375.7    4.92  4455.7    0.72  4475.7    0.73  4575.7    3.65  4595.7    3.77
  4615.7    3.26  4655.7    0.26  4675.7   -0.42  4914.4   -0.27  4974.4   -1.29
    4981    -0.5    4982    -2.5  5017.9    -2.5  5018.9    -0.5  5054.4   -0.81
  5094.4   -0.18  5134.4   -0.51  5241.7   -0.03  5301.7   -0.27  5321.7    -1.2
  5441.7    1.09  5481.7    5.06  5501.7    5.48  5561.7    8.37  5721.7    9.32
#Mann= 3 , 1 , 0
 3967.20    0.14       0    4981   0.045       0  5018.9    0.14       0
Bank Sta=4981.00,5018.90
Exp/Cntr=0.3,0.1

Type RM Length L Ch R = 1 ,6999.5,999.5,999.5,999.5
XS GIS Cut Line= 3
 2723167.5112577 917277.41019457 2723807.1012154 916556.95254109
 2724586.3717385 916034.98832276
BEGIN DESCRIPTION:
Goodwin Mill 7.0
END DESCRIPTION:
#Sta/Elev= 30
  3779.4    9.14  3942.8    9.21  4062.8    7.15  4122.8    6.93  4142.8    5.13
  4182.8    3.76  4242.8   -0.05  4282.8    0.15  4302.8   -0.89  4342.8    0.21
  4482.8    0.17  4522.8   -0.58  4562.8     0.6  4582.8   -0.24  4622.8    0.05
  4642.8   -0.53    4981    -0.5    4982    -2.5    5018    -2.5    5019    -0.5
  5140.7   -0.18  5160.7    0.52  5180.7    2.56  5200.7     3.5  5240.7    3.37
  5260.7    5.42  5280.7    6.47  5340.7    5.25  5440.7    7.36  5680.7    8.85
#Mann= 3 , 1 , 0
 3779.40    0.14       0    4981   0.045       0    5019    0.14       0
Bank Sta=4981.00,5019.00
Exp/Cntr=0.3,0.1

Type RM Length L Ch R = 1 ,6000.0,990.6,990.6,990.6
XS GIS Cut Line= 3
 2723770.3431718 917571.47454293 2724718.7006953 917042.15871588
 2724865.7328695  916402.5687582
BEGIN DESCRIPTION:
Goodwin Mill 6.0
END DESCRIPTION:
#Sta/Elev= 29
  3687.8    8.85  3693.8    9.04  4413.8     7.8  4433.8    7.56  4513.8    5.58
  4533.8    4.38  4553.8    0.85  4573.8    0.09  4593.8    -0.2  4613.8    0.18
  4633.8   -0.46  4673.8   -0.11  4773.8   -0.15  4790.1   -0.35  4810.1   -0.99
  4830.1   -0.46  4910.1   -0.12  4981.1    -0.5  4982.1    -2.5    5018    -2.5
    5019    -0.5  5070.1    0.05  5090.1   -0.27  5230.1    0.21  5270.1     6.4
  5310.1     8.9  5330.1     9.4  5370.1    9.33  5430.1    9.81
#Mann= 3 , 1 , 0
 3687.80    0.14       0  4981.1   0.045       0    5019    0.14       0
Bank Sta=4981.10,5019.00
Exp/Cntr=0.3,0.1

Type RM Length L Ch R = 1 ,5009.4,1005.2,1005.2,1005.2
XS GIS Cut Line= 3
 2725174.5004352 918387.50310962 2725505.3228271 917578.82615163
 2725020.1166523 916395.21714949
BEGIN DESCRIPTION:
Goodwin Mill 5.0
END DESCRIPTION:
#Sta/Elev= 30
  3901.9    9.65  4295.6     8.5  4395.6    6.89  4415.6    7.15  4555.6    0.61
  4575.6    0.36  4615.6    2.26  4635.6    2.26  4695.6    0.14    4980   -0.53
    4981   -2.53  5019.1   -2.53  5020.1   -0.53  5034.8    -1.4  5054.8   -0.62
  5174.8   -0.16  5394.8   -0.73  5414.8   -0.14  5434.8    2.05  5474.8    3.73
  5534.8    3.88  5594.8    1.53  5614.8    1.77  5634.8    3.43  5654.8    2.82
  5674.8    3.66  5774.8    4.49  5814.8    6.04  5914.8    8.16  6054.8    9.28
#Mann= 3 , 1 , 0
 3901.90    0.14       0    4980   0.045       0  5020.1    0.14       0
Bank Sta=4980.00,5020.10
Exp/Cntr=0.3,0.1

Type RM Length L Ch R = 1 ,4004.2,1006.3,1006.3,1006.3
XS GIS Cut Line= 3
 2726203.7256545 918144.90002222 2726086.0999151 917078.91675943
 2726071.3966977 915829.14327891
BEGIN DESCRIPTION:
Goodwin Mill 4.0
END DESCRIPTION:
#Sta/Elev= 30
  3750.2    7.98  4122.6    7.63  4182.6    6.98  4282.6    5.17  4322.6    2.11
  4362.6    0.16  4402.6   -0.54  4482.6    0.17  4742.6   -0.36  4782.6    0.24
  4932.5   -0.28  4952.5   -1.01  4972.5   -0.21  4979.9   -0.56  4980.9   -2.56
  5019.1   -2.56  5020.1   -0.56  5112.5   -1.47  5152.5    -0.6  5332.5   -0.02
  5492.5   -0.63  5592.5   -0.01  5632.5   -0.69  5712.5   -0.02  5732.5    1.28
  5752.5    5.42  5792.5    8.28  5812.5    8.88  6012.5    9.76  6072.5    9.34
#Mann= 3 , 1 , 0
 3750.20    0.14       0  4979.9   0.045       0  5020.1    0.14       0
Bank Sta=4979.90,5020.10
Exp/Cntr=0.3,0.1

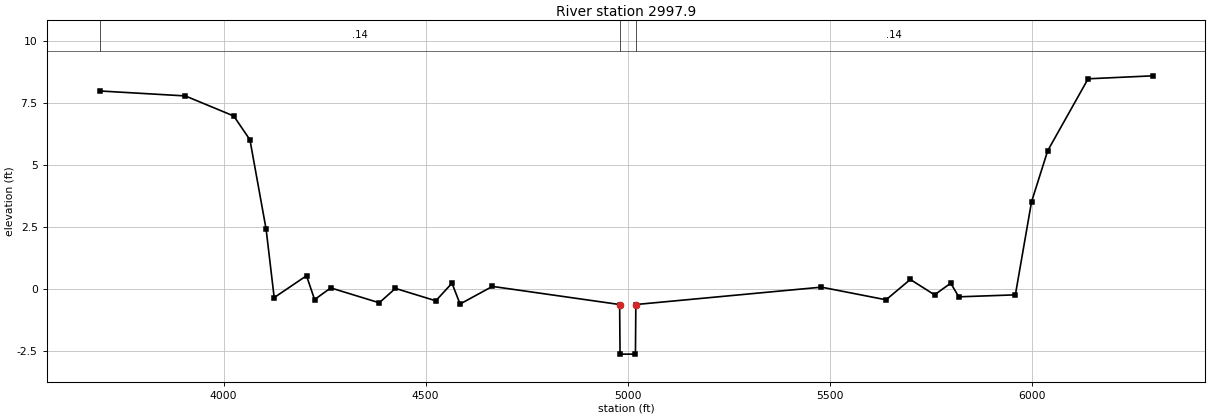
Type RM Length L Ch R = 1 ,2997.9,991.8,991.8,991.8
XS GIS Cut Line= 4
 2726505.1416115 918262.52576157 2726909.4800905 917248.00375973
 2726990.3477863  916975.9942375 2727071.2154821 915748.27558311
BEGIN DESCRIPTION:
Goodwin Mill 3.0
END DESCRIPTION:
#Sta/Elev= 30
    3693    7.99  3905.1    7.79  4025.1    6.98  4065.1    6.02  4105.1    2.42
  4125.1   -0.34  4205.1    0.54  4225.1   -0.42  4265.1    0.05  4385.1   -0.55
  4425.1    0.03  4525.1   -0.47  4565.1    0.24  4585.1    -0.6  4665.1    0.11
    4980   -0.62    4981   -2.62  5019.1   -2.62  5020.1   -0.62  5479.3    0.08
  5639.3   -0.43  5699.3    0.39  5759.3   -0.23  5799.3    0.24  5819.3   -0.31
  5959.3   -0.23  5999.3    3.52  6039.3    5.58  6139.3    8.48  6299.3     8.6
#Mann= 3 , 1 , 0
 3693.00    0.14       0    4980   0.045       0  5020.1    0.14       0
Bank Sta=4980.00,5020.10
Exp/Cntr=0.3,0.1