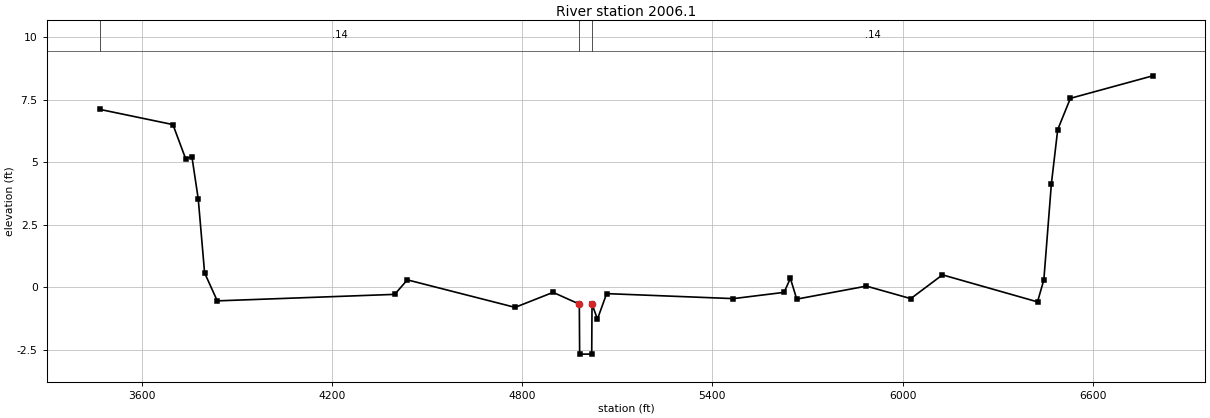
HEC-RAS study GOODWIN MILL CREEK.PRJ: Goodwin Mill Creek

--- GOODWIN MILL CREEK.g01 (geometry) --- (continued)

Type RM Length L Ch R = 1 ,2006.1,0,0,0
XS GIS Cut Line= 5
 2726659.5253944 918387.50310962 2727725.5086572 917556.77132551
 2727835.7827879 917343.57467295 2727527.0152221 915968.82384438
 2727321.1701782 915718.86914827
BEGIN DESCRIPTION:
Goodwin Mill 2.0
END DESCRIPTION:
#Sta/Elev= 30
  3465.6    7.11  3697.1     6.5  3737.1    5.14  3757.1    5.21  3777.1    3.52
  3797.1    0.57  3837.1   -0.55  4397.1   -0.29  4437.1    0.29  4777.1   -0.81
  4897.1   -0.21  4979.9   -0.68  4980.9   -2.68    5019   -2.68    5020   -0.68
  5037.1   -1.28  5066.1   -0.26  5466.1   -0.46  5626.1   -0.21  5646.1    0.35
  5666.1   -0.48  5886.1    0.04  6026.1   -0.46  6126.1    0.49  6426.1   -0.59
  6446.1    0.29  6469.9    4.13  6489.9     6.3  6529.9    7.55  6789.9    8.45
#Mann= 3 , 1 , 0
 3465.60    0.14       0  4979.9   0.045       0    5020    0.14       0
Bank Sta=4979.90,5020.00
Exp/Cntr=0.3,0.1

Chan Stop Cuts=-1