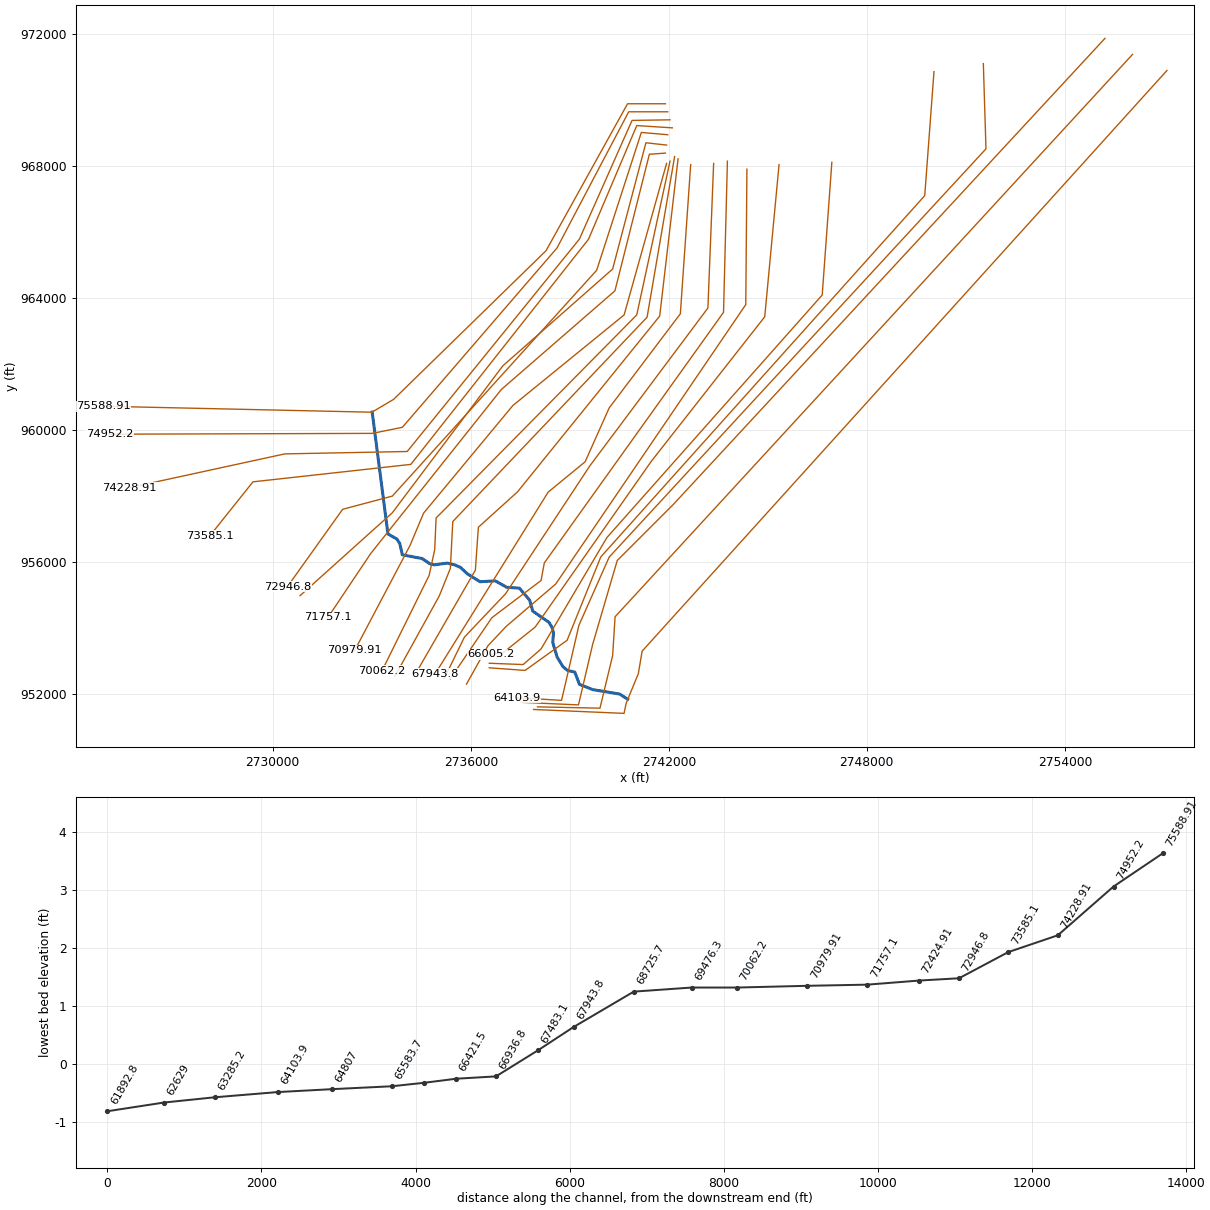
--- PerquimansRiver.prj (project) ---

Proj Title=Perquimans River
Current Plan=p02
Default Exp/Contr=0.3,0.1
English Units
Geom File=g01
Flow File=f03
Flow File=f02
Flow File=f01
Plan File=p03
Plan File=p02
Plan File=p01
Y Axis Title=Elevation
X Axis Title(PF)=Main Channel Distance
X Axis Title(XS)=Station
BEGIN DESCRIPTION:
PASQUOTANK RIVER BASIN
PERQUIMANS RIVER
HCFCD Unit X###-##-##
(Flood Hazard, Floodway) Model
10, 2, 1, 0.2% Event
Filename:  N:\NC_flood\60227\Baker\ENG\Perquimans River Trib 4 Basin\Perquimans River.prj
Prepared by:  ________     Date: ________
Reviewed by:  ________     Date: ________
STATUS (Draft RAS, SVSQ, FINAL)
END DESCRIPTION:
DSS Export Rating Curves= 0
DSS Export Rating Curve Sorted= 0
DSS Export Volume Flow Curves= 0
DXF OffsetX= 0
DXF OffsetY= 0
DXF ScaleX= 1
DXF ScaleY= 10

--- PerquimansRiver.p02 (plan) ---

Plan Title=Approximate Floodway
Program Version=4.00
Short Identifier=Plan02
Geom File=g01
Flow File=f02
Subcritical Flow
K Sum by GR= 0
Std Step Tol= 0.01
Critical Tol= 0.01
Num of Std Step Trials= 20
Max Error Tol= 0.3
Flow Tol Ratio= 0.001
Split Flow NTrial= 30
Split Flow Tol= 0.02
Split Flow Ratio= 0.02
Log Output Level= 0
Friction Slope Method= 1
Unsteady Friction Slope Method= 2
Unsteady Bridges Friction Slope Method= 1
Parabolic Critical Depth
Global Vel Dist= 0 , 0 , 0
Global Log Level= 0
CheckData=True
Encroach Param=-1 ,10,10, 2
Encroach River=Perquimans River
Encroach Reach=Reach - 1
Encroach Node=75588.91
       1 4448.05  5565.1
Encroach Node=74952.2
       1 3731.79 5624.72
Encroach Node=74228.91
       1  2882.5 5744.25
Encroach Node=73585.1
       1  4567.7    7692
Encroach Node=72946.8
       1 4901.99 6112.54
Encroach Node=72424.91
       1 4647.43 5893.59
Encroach Node=71757.1
       1 4214.75  5289.9
Encroach Node=70979.91
       1 4267.86 5283.31
Encroach Node=70062.2
       1 4225.98 5032.79
Encroach Node=69476.3
       1 4428.39 5321.51
Encroach Node=68725.7
       1 4384.56 5310.12
Encroach Node=67943.8
       1 3647.11 5221.29
Encroach Node=67483.1
       1 4417.12 5250.66
Encroach Node=66936.8
       1    4030 5054.38
Encroach Node=66421.5
       1 4368.52 5478.54
Encroach Node=66005.2
       1 4462.27 5654.41
Encroach Node=65583.7
       1 4517.79 5365.96
Encroach Node=64807
       1 3915.92 5034.03
Encroach Node=64103.9
       1 3624.68 5281.07
Encroach Node=63285.2
       1 3226.61  5020.6
Encroach Node=62629
       1  3441.6  5020.7
Encroach Node=61892.8
       1    3879  5060.5
Computation Interval=1HOUR
Output Interval=1HOUR
Run HTab= 0
Run UNet= 0
Run PostProcess= 0
Run WQNet= 0
UNET Theta= 1
UNET Theta Warmup= 1
UNET ZTol= 0.02
UNET ZSATol= 0.1
UNET MxIter= 20
UNET MaxInSteps= 20
UNET DtIC= 0
UNET DtMin= 0
UNET MaxCRTS= 20
UNET WFStab= 2
UNET SFStab= 1
UNET WFX= 1
UNET SFX= 1
UNET DSS MLevel= 4
UNET DZMax Abort= 100
UNET Convert EG Bridges=-1
UNET Use Existing IB Tables=-1
UNET Froude Reduction=False
UNET Froude Limit= 1
UNET Froude Power= 10
UNET Time Slicing=0,0, 5
Instantaneous Interval=1HOUR
Write IC File= 0
Echo Input=False
Echo Output=False
Write Detailed= 0
Detailed Automatic Start=False, 10
WQ ULTIMATE=-1
WQ Max Comp Step=1HOUR
WQ Output Interval=15MIN
WQ Output Selected Increments= 0
WQ Output face flow=0
WQ Output face velocity=0
WQ Output face area=0
WQ Output face dispersion=0
WQ Output cell volume=0
WQ Output cell surface area=0
WQ Output cell continuity=0
WQ Output face conc=0
WQ Output face dconc_dx=0
WQ Output face courant=0
WQ Output face peclet=0
WQ Output face adv mass=0
WQ Output face disp mass=0
WQ Output cell mass=0
WQ Output cell source sink temp=0
WQ Output cell source sink nsm=0
WQ Output MaxMinRange=-1
WQ Daily Max Min Mean=-1
WQ Daily Range=0
WQ Daily Time=0
WQ Create Restart=0
WQ Fixed Restart=0
WQ System Summary=False
Sorting and Armoring Iterations= 10
XS Update Threshold= 0.02
Hydraulics Update Threshold= 0.02
Energy Slope Method= 1
Volume Change Method= 0
XS Weighting Method= 0
Number of US Weighted Cross Sections= 1
Number of DS Weighted Cross Sections= 1
Upstream XS Weight=0.25
Main XS Weight=0.5
Downstream XS Weight=0.25
Number of DS XS's Weighted with US Boundary= 1
Upstream Boundary Weight= 1
Weight of XSs Associated with US Boundary= 0
Number of US XS's Weighted with DS Boundary= 1
Downstream Boundary Weight= 0.5
Weight of XSs Associated with DS Boundary= 0.5
Sediment Output Level= 4
Mass or Volume Output= 0
Output Increment Type= 1
Profile and TS Output Increment= 10
XS Output Flag= 0
XS Output Increment= 10
Disregard all LS=0
Disregard all Conn=0
Disregard all Breaches=0
Disregard all Pumps=0

--- PerquimansRiver.p01 (plan) ---

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Plan Title=100 Year Single
Short Identifier=Plan01
Geom File=g01
Flow File=f01
Encroach Param=-1 ,0,0, 0

--- PerquimansRiver.p03 (plan) ---

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Plan Title=New Profiles
Short Identifier=Plan03
Geom File=g01
Flow File=f03
Encroach Param=-1 ,0,0, 2

--- PerquimansRiver.f02 (steady flow) ---

Flow Title=Approximate Floodway
Program Version=4.00
Number of Profiles= 2
Profile Names=100-year,AFW
River Rch & RM=Perquimans River,Reach - 1       ,75588.91
     649     649
River Rch & RM=Perquimans River,Reach - 1       ,71757.1
    1372    1372
River Rch & RM=Perquimans River,Reach - 1       ,70979.91
    1457    1457
River Rch & RM=Perquimans River,Reach - 1       ,67943.8
    2419    2419
River Rch & RM=Perquimans River,Reach - 1       ,65583.7
    2494    2494
River Rch & RM=Perquimans River,Reach - 1       ,62629
    2496    2496
Boundary for River Rch & Prof#=Perquimans River,Reach - 1       , 1
Up Type= 0
Dn Type= 1
Dn Known WS=10.25
Boundary for River Rch & Prof#=Perquimans River,Reach - 1       , 2
Up Type= 0
Dn Type= 1
Dn Known WS=11.19
DSS Import GetInterval= 0
DSS Import GetPeak= 0
DSS Import FillOption= 0

--- PerquimansRiver.f01 (steady flow) ---

Flow Title=100 Year Single
Program Version=4.00
Number of Profiles= 1
Profile Names=100-Year
River Rch & RM=Perquimans River,Reach - 1       ,75588.91
     649
River Rch & RM=Perquimans River,Reach - 1       ,71757.1
    1372
River Rch & RM=Perquimans River,Reach - 1       ,70979.91
    1457
River Rch & RM=Perquimans River,Reach - 1       ,67943.8
    2419
River Rch & RM=Perquimans River,Reach - 1       ,65583.7
    2494
River Rch & RM=Perquimans River,Reach - 1       ,62629
    2496
Boundary for River Rch & Prof#=Perquimans River,Reach - 1       , 1
Up Type= 0
Dn Type= 1
Dn Known WS=10.25
DSS Import GetInterval= 0
DSS Import GetPeak= 0
DSS Import FillOption= 0

--- PerquimansRiver.f03 (steady flow) ---

Flow Title=New Profiles
Program Version=4.00
Number of Profiles= 7
Profile Names=P10yr,P25yr,P50yr,P500yr,F100yr-10,F100yr-20,F100yr-35
River Rch & RM=Perquimans River,Reach - 1       ,75588.91
     268     396     512    1055    1135    1454    1777
River Rch & RM=Perquimans River,Reach - 1       ,71757.1
     605     867    1103    2153    2341    3000    3666
River Rch & RM=Perquimans River,Reach - 1       ,70979.91
     646     924    1173    2280    2481    3180    3885
River Rch & RM=Perquimans River,Reach - 1       ,67943.8
    1120    1571    1970    3694    4049    5189    6340
River Rch & RM=Perquimans River,Reach - 1       ,65583.7
    1158    1622    2033    3804    4171    5346    6532
River Rch & RM=Perquimans River,Reach - 1       ,62629
    1159    1623    2034    3806    4173    5349    6535
Boundary for River Rch & Prof#=Perquimans River,Reach - 1       , 1
Up Type= 0
Dn Type= 1
Dn Known WS=8.37
Boundary for River Rch & Prof#=Perquimans River,Reach - 1       , 2
Up Type= 0
Dn Type= 1
Dn Known WS=9.16
Boundary for River Rch & Prof#=Perquimans River,Reach - 1       , 3
Up Type= 0
Dn Type= 1
Dn Known WS=9.7
Boundary for River Rch & Prof#=Perquimans River,Reach - 1       , 4
Up Type= 0
Dn Type= 1
Dn Known WS=11.99
Boundary for River Rch & Prof#=Perquimans River,Reach - 1       , 5
Up Type= 0
Dn Type= 1
Dn Known WS=12.37
Boundary for River Rch & Prof#=Perquimans River,Reach - 1       , 6
Up Type= 0
Dn Type= 1
Dn Known WS=13.39
Boundary for River Rch & Prof#=Perquimans River,Reach - 1       , 7
Up Type= 0
Dn Type= 1
Dn Known WS=14.31
DSS Import GetInterval= 0
DSS Import GetPeak= 0
DSS Import FillOption= 0

--- PerquimansRiver.g01 (geometry) ---

Geom Title=Geom 01 by CodeH2 for Windows
Program Version=4.00

River Reach=Perquimans River,Reach - 1
Reach XY= 30
      2740758.05       951837.13      2740514.25       951993.56
       2739696.5         952129.        2739294.       952288.13
        2739152.        952661.5      2738933.75       952708.88
      2738791.75       952827.19      2738618.25        953112.5
      2738484.25       953556.94       2738506.5       953845.88
       2738464.5       954014.13        2738367.       954169.31
        2737878.       954508.69        2737784.       954840.06
       2737473.5       955204.06      2737093.25        955228.5
        2736741.       955425.56      2736280.75       955397.63
       2735893.5       955640.06      2735687.75       955831.88
        2735517.       955908.56      2735293.75       955962.63
        2734896.       955910.31        2734760.       955943.44
      2734526.25       956100.44       2733926.5       956213.75
      2733849.75       956552.06       2733762.5       956691.56
       2733490.5       956845.06      2733012.64         960540.

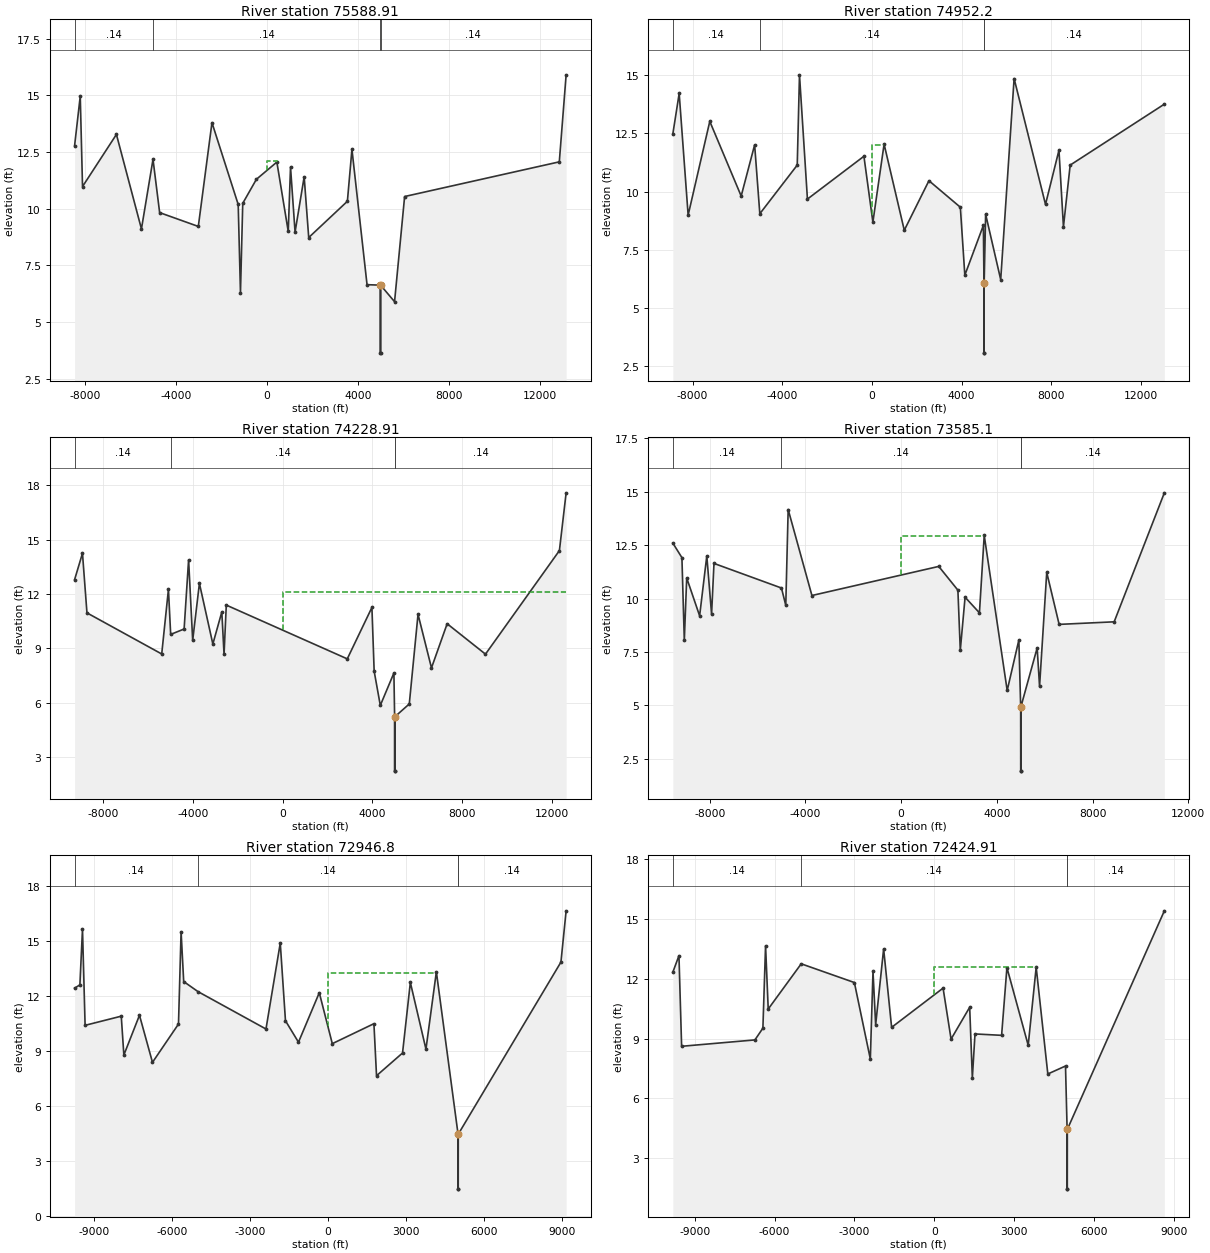
Type RM Length L Ch R = 1 ,75588.91,636.7,636.7,636.7
BEGIN DESCRIPTION:
PERQUIMANS RIVER 24.0
END DESCRIPTION:
XS GIS Cut Line= 6
      2741898.64       969881.25      2740751.07       969881.25
      2738282.06       965430.08      2733662.43       960924.18
      2733005.01       960534.99      2724855.87       960716.13
#Sta/Elev= 30
   -8446   12.79 -8198.4   14.97 -8098.4   10.98 -6608.3   13.28 -5508.3    9.11
 -5000.1   12.18 -4708.3    9.83 -3008.3    9.22 -2408.3    13.8 -1255.1   10.19
 -1155.1     6.3 -1055.1   10.24  -455.1    11.3   444.9   12.06   944.9       9
  1044.9   11.84  1244.9    8.97  1644.9   11.41  1844.9    8.73  3544.9   10.33
  3744.9   12.62  4408.9    6.65    4996    6.63  4997.5    3.63  5002.5    3.63
    5004    6.63  5618.4     5.9  6060.8   10.54 12860.8   12.07 13160.8   15.91
#Mann= 4 , 1 , 0
   -8446     .14       0 -5000.1     .14       0    4996    .045       0
    5004     .14       0
#XS Ineff= 2 , 0
       0     445    12.1               0
Permanent Ineff=
       F       F
Bank Sta=4996,5004
XS Rating Curve= 0 ,0
Exp/Cntr=0.3,0.1

Type RM Length L Ch R = 1 ,74952.2 ,723.3,723.3,723.3
BEGIN DESCRIPTION:
PERQUIMANS RIVER 23.0
END DESCRIPTION:
XS GIS Cut Line= 6
      2741968.18       969637.83      2740785.84       969637.83
      2738612.26       965509.98       2733927.6       960077.56
       2733018.6        959893.3       2725048.5       959868.56
#Sta/Elev= 30
   -8879   12.48 -8596.6   14.22 -8196.6    8.99 -7231.5   13.02 -5831.5    9.81
 -5231.5   12.01 -5000.1    9.05 -3331.5   11.14 -3231.5   15.02 -2877.1    9.68
  -358.1   11.52    41.9    8.69   541.9   12.04  1441.9    8.34  2541.9   10.47
  3941.9    9.33  4141.9    6.41  4969.4    8.55    4996    6.06  4997.5    3.06
  5002.5    3.06    5004    6.06  5069.4    9.03  5741.7    6.22  6339.6   14.86
  7739.6    9.45  8339.6   11.78  8539.6    8.49  8839.6   11.14 13039.6   13.76
#Mann= 4 , 1 , 0
   -8879     .14       0 -5000.1     .14       0    4996    .045       0
    5004     .14       0
#XS Ineff= 2 , 0
       0     541      12               0
Permanent Ineff=
       F       F
Bank Sta=4996,5004
XS Rating Curve= 0 ,0
Exp/Cntr=0.3,0.1

Type RM Length L Ch R = 1 ,74228.91,643.8,643.8,643.8
BEGIN DESCRIPTION:
PERQUIMANS RIVER 22.0
END DESCRIPTION:
XS GIS Cut Line= 6
      2742037.73       969394.41      2740887.09       969376.43
      2739290.53       965777.83      2734074.31        959344.5
      2730365.64       959272.12      2725664.92       958250.46
#Sta/Elev= 30
 -9287.5    12.8 -8936.7   14.25 -8736.7   10.96 -5399.8    8.69 -5099.8   12.26
 -5000.1    9.77 -4399.8   10.07 -4199.8   13.89 -4017.5    9.44 -3717.5   12.59
 -3117.5    9.24 -2717.5   11.01 -2617.5    8.67 -2517.5   11.39  2882.5    8.42
  3982.5   11.26  4082.5    7.74  4357.1    5.85  4964.3    7.64    4996    5.22
  4997.5    2.22  5002.5    2.22    5004    5.22  5650.6    5.93  6040.8   10.88
  6640.8    7.92  7340.8   10.36  9051.3    8.68 12351.3    14.4 12651.3   17.59
#Mann= 4 , 1 , 0
 -9287.5     .14       0 -5000.1     .14       0    4996    .045       0
    5004     .14       0
#XS Ineff= 2 , 0
       0   -3417    12.1               0
Permanent Ineff=
       F       F
Bank Sta=4996,5004
XS Rating Curve= 0 ,0
Exp/Cntr=0.3,0.1

Type RM Length L Ch R = 1 ,73585.1 ,638.3,638.3,638.3
BEGIN DESCRIPTION:
PERQUIMANS RIVER 21.0
END DESCRIPTION:
XS GIS Cut Line= 6
      2742107.28       969150.98       2741030.1       969220.18
      2739568.73       965777.83      2734184.03       958953.93
      2729400.38       958425.11      2728092.07       956786.47
#Sta/Elev= 30
 -9538.9   12.59 -9159.5   11.91 -9059.5    8.04 -8959.5   10.96 -8419.8    9.19
 -8119.8   11.99 -7919.8    9.26 -7819.8   11.64 -5000.1   10.49 -4819.8    9.68
 -4719.8   14.16 -3727.3   10.14  1572.7    11.5  2372.7   10.39  2472.7    7.58
  2672.7   10.06  3272.7    9.33  3472.7   12.95  4432.6     5.7  4919.9    8.06
    4996    4.93  4997.5    1.93  5002.5    1.93    5004    4.93  5684.9    7.69
  5784.9    5.89  6084.9   11.22  6602.9    8.79  8902.9    8.91 10999.8   14.94
#Mann= 4 , 1 , 0
 -9538.9     .14       0 -5000.1     .14       0    4996    .045       0
    5004     .14       0
#XS Ineff= 2 , 0
       0    3472    12.9               0
Permanent Ineff=
       F       F
Bank Sta=4996,5004
XS Rating Curve= 0 ,0
Exp/Cntr=0.3,0.1

Type RM Length L Ch R = 1 ,72946.8 ,521.9,521.9,521.9
BEGIN DESCRIPTION:
PERQUIMANS RIVER 20.0
END DESCRIPTION:
XS GIS Cut Line= 6
      2741968.18       968942.34      2741168.36       969011.89
      2739814.83       964835.79      2733623.12       957992.95
      2732117.51       957592.86      2730442.16       955245.43
#Sta/Elev= 30
   -9743   12.45 -9540.2   12.63 -9440.2   15.67 -9340.2   10.42 -7950.2   10.92
 -7850.2     8.8 -7250.2   10.97 -6750.2     8.4 -5750.2   10.49 -5650.2   15.53
 -5550.2   12.81 -5000.1   12.26 -2387.3   10.22 -1838.1   14.91 -1638.1   10.67
 -1138.1     9.5  -338.1    12.2   161.9    9.42  1761.9   10.51  1861.9    7.67
  2861.9    8.91  3161.9   12.76  3761.9    9.12  4161.9   13.34    4996    4.48
  4997.5    1.48  5002.5    1.48    5004    4.48  8950.1   13.87  9150.1   16.67
#Mann= 4 , 1 , 0
   -9743     .14       0 -5000.1     .14       0    4996    .045       0
    5004     .14       0
#XS Ineff= 2 , 0
       0    4161    13.3               0
Permanent Ineff=
       F       F
Bank Sta=4996,5004
XS Rating Curve= 0 ,0
Exp/Cntr=0.3,0.1

Type RM Length L Ch R = 1 ,72424.91,667.8,667.8,667.8
BEGIN DESCRIPTION:
PERQUIMANS RIVER 19.0
END DESCRIPTION:
XS GIS Cut Line= 6
      2741933.41       968629.36      2741307.46       968698.91
        2740299.       964873.69      2736969.42       961937.94
      2733623.12       957487.57      2730827.42       954975.75
#Sta/Elev= 30
 -9826.5   12.33 -9596.7   13.16 -9496.7    8.61 -6740.8    8.93 -6440.8    9.52
 -6340.8   13.66 -6240.8   10.48 -5000.1   12.75 -3001.8   11.81 -2401.8    7.97
 -2301.8   12.37 -2201.8    9.69 -1901.8    13.5 -1601.8    9.56   333.1   11.53
   633.1    8.97  1333.1   10.57  1433.1    7.02  1533.1    9.23  2533.1    9.16
  2733.1   12.56  3533.1    8.66  3833.1   12.58  4270.6    7.22  4935.4    7.62
    4996    4.44  4997.5    1.44  5002.5    1.44    5004    4.44  8651.6   15.41
#Mann= 4 , 1 , 0
 -9826.5     .14       0 -5000.1     .14       0    4996    .045       0
    5004     .14       0
#XS Ineff= 2 , 0
       0    3833    12.6               0
Permanent Ineff=
       F       F
Bank Sta=4996,5004
XS Rating Curve= 0 ,0
Exp/Cntr=0.3,0.1

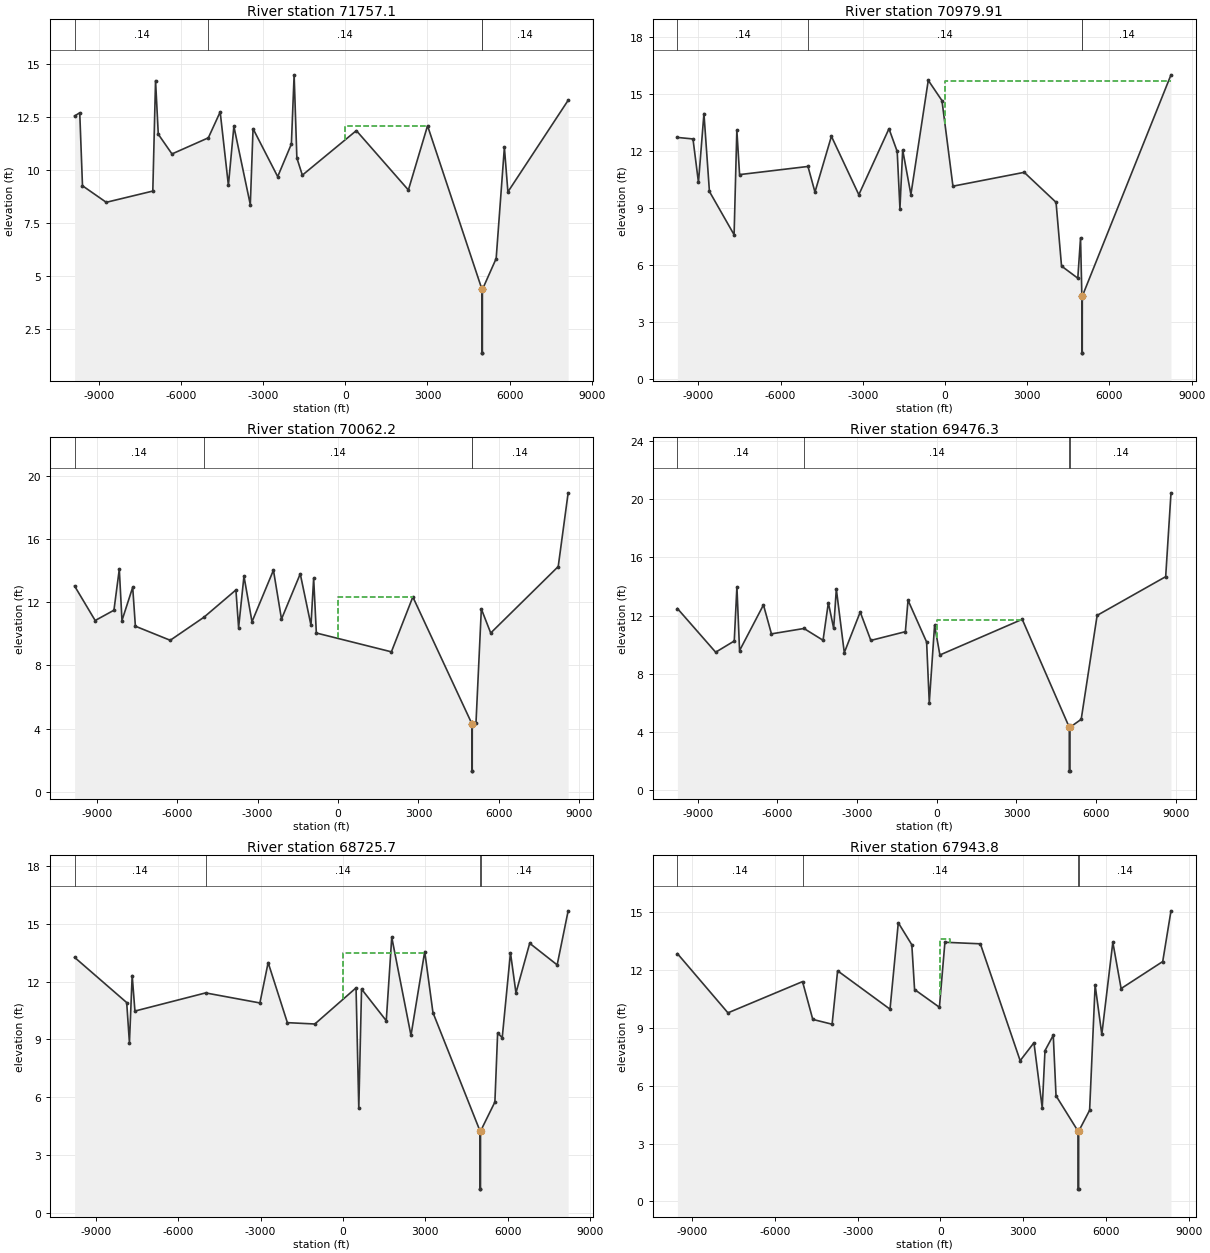
Type RM Length L Ch R = 1 ,71757.1 ,777.2,777.2,777.2
BEGIN DESCRIPTION:
PERQUIMANS RIVER 18.0
END DESCRIPTION:
XS GIS Cut Line= 6
      2741898.64       968385.94      2741411.79       968351.16
      2740368.55       964212.97      2736925.84       961222.34
      2732970.34        956255.7      2731674.99        954320.8
#Sta/Elev= 30
 -9883.6   12.55 -9695.5    12.7 -9595.5    9.26 -8727.8    8.48 -7027.8    9.01
 -6927.8   14.22 -6827.8   11.69 -6327.8   10.76 -5000.1   11.52 -4567.6   12.74
 -4267.6    9.28 -4067.6   12.06 -3467.6    8.37 -3367.6   11.95 -2467.6    9.69
 -1967.6   11.23 -1867.6   14.49 -1767.6   10.57 -1567.6    9.76   404.2   11.86
  2304.2    9.06  3004.2   12.09  4992.7    4.37  4994.2    1.37  5005.8    1.37
  5007.3    4.37  5509.6    5.83  5809.6   11.07  5938.1    8.97  8138.1   13.29
#Mann= 4 , 1 , 0
 -9883.6     .14       0 -5000.1     .14       0  4992.7    .045       0
  5007.3     .14       0
#XS Ineff= 2 , 0
       0    3004    12.1               0
Permanent Ineff=
       F       F
Bank Sta=4992.7,5007.3
XS Rating Curve= 0 ,0
Exp/Cntr=0.3,0.1

Type RM Length L Ch R = 1 ,70979.91,917.7,917.7,917.7
BEGIN DESCRIPTION:
PERQUIMANS RIVER 17.0
END DESCRIPTION:
XS GIS Cut Line= 6
      2741933.41       968072.97      2740646.74        963482.7
      2737273.59       960735.49      2734570.71       957477.04
      2734160.09       956497.86      2732484.04       953319.12
#Sta/Elev= 30
 -9762.7   12.72 -9195.5   12.64 -8995.5   10.35 -8795.5   13.98 -8595.5    9.87
 -7695.5    7.59 -7595.5   13.11 -7495.5   10.76 -5000.1   11.19 -4745.2    9.84
 -4145.2   12.78 -3145.2     9.7 -2045.2   13.18 -1745.2   11.98 -1645.2    8.97
 -1545.2   12.06 -1245.2    9.71  -611.6   15.73  -111.6   14.66   288.4   10.15
  2888.4   10.88  4050.2     9.3  4250.2    5.94  4843.7     5.3  4943.7    7.43
  4992.3    4.35  4993.8    1.35  5006.3    1.35  5007.8    4.35  8243.7   16.02
#Mann= 4 , 1 , 0
 -9762.7     .14       0 -5000.1     .14       0  4992.3    .045       0
  5007.8     .14       0
#XS Ineff= 2 , 0
       0  -611.6    15.7               0
Permanent Ineff=
       F       F
Bank Sta=4992.3,5007.8
XS Rating Curve= 0 ,0
Exp/Cntr=0.3,0.1

Type RM Length L Ch R = 1 ,70062.2 ,585.9,585.9,585.9
BEGIN DESCRIPTION:
PERQUIMANS RIVER 16.0
END DESCRIPTION:
XS GIS Cut Line= 6
      2742037.73       968142.52      2741029.27        963482.7
      2734949.52       957328.83      2734907.63       956371.52
      2734739.17       955592.39      2733306.65       952691.46
#Sta/Elev= 30
 -9827.5   13.02 -9059.8   10.84 -8359.8   11.49 -8159.8   14.08 -8059.8   10.84
 -7659.8   12.94 -7559.8   10.48 -6259.8    9.59 -5000.1   11.05 -3809.2   12.77
 -3709.2   10.39 -3509.2   13.64 -3209.2   10.76 -2409.2   14.02 -2109.2   10.93
 -1409.2   13.79 -1009.2   10.54  -909.2   13.51  -809.2   10.05  1990.8    8.86
  2790.8   12.33  4992.3    4.32  4993.8    1.32  5006.3    1.32  5007.8    4.32
  5146.2    4.35  5346.2   11.57    5696   10.05  8214.3   14.25  8584.9   18.91
#Mann= 4 , 1 , 0
 -9827.5     .14       0 -5000.1     .14       0  4992.3    .045       0
  5007.8     .14       0
#XS Ineff= 2 , 0
       0    2791    12.3               0
Permanent Ineff=
       F       F
Bank Sta=4992.3,5007.8
XS Rating Curve= 0 ,0
Exp/Cntr=0.3,0.1

Type RM Length L Ch R = 1 ,69476.3 ,750.6,750.6,750.6
BEGIN DESCRIPTION:
PERQUIMANS RIVER 15.0
END DESCRIPTION:
XS GIS Cut Line= 6
      2742176.83       968281.61      2741342.24       963413.15
      2735455.25       957221.95      2735381.43       955802.96
      2735045.77       954968.11      2733701.16       952533.65
#Sta/Elev= 30
 -9765.4   12.49 -8325.9    9.49 -7625.9   10.26 -7525.9   13.99 -7425.9     9.6
 -6525.9   12.74 -6225.9   10.75 -5000.1   11.12 -4282.6   10.31 -4082.6   12.89
 -3882.6   11.13 -3782.6   13.83 -3482.6    9.46 -2882.6   12.25 -2482.6    10.3
 -1182.6    10.9 -1082.6   13.06  -382.6   10.19  -282.6    6.02   -82.6   11.34
   117.4     9.3  3217.4   11.75  4992.3    4.32  4993.8    1.32  5006.3    1.32
  5007.8    4.32  5438.1    4.88  6038.1   12.02  8619.2   14.68  8819.2   20.44
#Mann= 4 , 1 , 0
 -9765.4     .14       0 -5000.1     .14       0  4992.3    .045       0
  5007.8     .14       0
#XS Ineff= 2 , 0
       0    3215    11.7               0
Permanent Ineff=
       F       F
Bank Sta=4992.3,5007.8
XS Rating Curve= 0 ,0
Exp/Cntr=0.3,0.1

Type RM Length L Ch R = 1 ,68725.7 ,781.9,781.9,781.9
BEGIN DESCRIPTION:
PERQUIMANS RIVER 14.0
END DESCRIPTION:
XS GIS Cut Line= 6
      2742281.16       968212.07      2741724.76       963447.92
      2737417.19        958122.4      2736230.35       957049.36
       2736139.5       955750.32        2734431.       952790.08
#Sta/Elev= 30
 -9769.7   13.25 -7873.2   10.91 -7773.2    8.83 -7673.2   12.31 -7573.2   10.47
 -5000.1   11.41 -3023.7   10.89 -2723.7   12.98 -2023.7    9.87 -1023.7     9.8
   476.3   11.67   576.3    5.43   676.3   11.61  1576.3    9.97  1776.3   14.29
  2476.3    9.21  2976.3   13.55  3276.3   10.39  4992.2    4.25  4993.7    1.25
  5006.2    1.25  5007.7    4.25  5530.9    5.76  5630.9    9.34  5797.9    9.09
  6097.9   13.49  6297.9   11.41  6797.9   13.98  7797.9   12.86  8197.9   15.66
#Mann= 4 , 1 , 0
 -9769.7     .14       0 -5000.1     .14       0  4992.2    .045       0
  5007.7     .14       0
#XS Ineff= 2 , 0
       0    2976    13.5               0
Permanent Ineff=
       F       F
Bank Sta=4992.2,5007.7
XS Rating Curve= 0 ,0
Exp/Cntr=0.3,0.1

Type RM Length L Ch R = 1 ,67943.8 ,460.7,460.7,460.7
BEGIN DESCRIPTION:
PERQUIMANS RIVER 13.0
END DESCRIPTION:
XS GIS Cut Line= 6
      2742663.68       968038.19      2742350.71       963517.47
      2740194.67       960665.94       2739464.4       959031.52
      2738344.93       958113.37      2734924.13       952612.56
#Sta/Elev= 30
 -9535.2   12.85 -7703.7    9.78 -5000.1    11.4 -4628.8    9.44 -3928.8    9.19
 -3728.8   11.96 -1828.8    9.97 -1528.8   14.45 -1038.7   13.31  -938.7   10.99
   -38.7   10.07   161.3   13.44  1445.9   13.36  2888.9     7.3  3388.9    8.23
  3688.9    4.85  3788.9    7.82  4088.9    8.62  4188.9    5.48    4990    3.64
  4991.5     .64  5008.6     .64  5010.1    3.64  5406.5    4.73  5606.5   11.22
  5848.4    8.66  6248.4   13.44  6548.4   11.04  8056.6   12.44  8356.6   15.07
#Mann= 4 , 1 , 0
 -9535.2     .14       0 -5000.1     .14       0    4990    .045       0
  5010.1     .14       0
#XS Ineff= 2 , 0
       0     360    13.6               0
Permanent Ineff=
       F       F
Bank Sta=4990,5010.1
XS Rating Curve= 0 ,0
Exp/Cntr=0.3,0.1

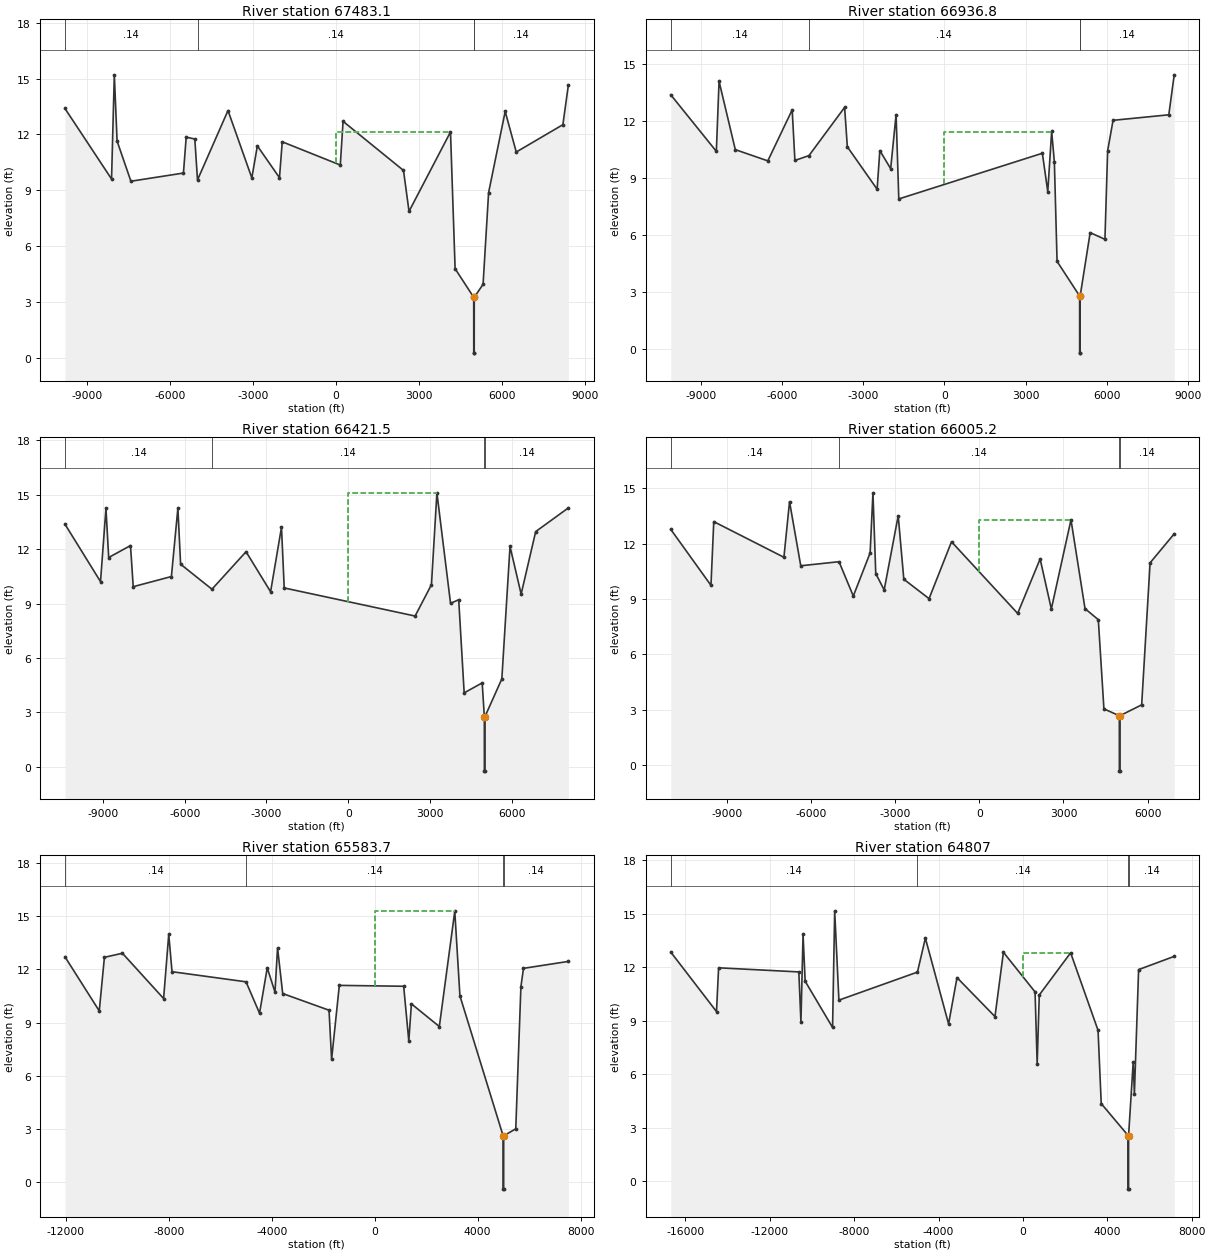
Type RM Length L Ch R = 1 ,67483.1 ,546.3,546.3,546.3
BEGIN DESCRIPTION:
PERQUIMANS RIVER 12.0
END DESCRIPTION:
XS GIS Cut Line= 6
      2743359.18       968072.97       2743185.3       963691.34
       2739609.8       958912.48      2737055.51       955034.36
      2735808.47       953720.31      2735200.28       952474.48
#Sta/Elev= 30
 -9794.1   13.39   -8109     9.6   -8009    15.2   -7909   11.64   -7409    9.48
   -5509    9.92   -5409   11.85 -5097.4   11.75 -5000.1    9.55 -3897.4   13.28
 -3035.3    9.66 -2835.3   11.38 -2035.3    9.67 -1935.3    11.6   164.7   10.35
   264.7    12.7  2450.4   10.06  2650.4    7.86  4150.4   12.13  4317.1    4.78
    4990    3.24  4991.5     .24  5008.6     .24  5010.1    3.24  5328.6    3.94
  5528.6    8.87  6128.6   13.23  6528.6   11.05    8215   12.52    8415   14.66
#Mann= 4 , 1 , 0
 -9794.1     .14       0 -5000.1     .14       0    4990    .045       0
  5010.1     .14       0
#XS Ineff= 2 , 0
       0    4150    12.1               0
Permanent Ineff=
       F       F
Bank Sta=4990,5010.1
XS Rating Curve= 0 ,0
Exp/Cntr=0.3,0.1

Type RM Length L Ch R = 1 ,66936.8 ,515.3,515.3,515.3
BEGIN DESCRIPTION:
PERQUIMANS RIVER 11.0
END DESCRIPTION:
XS GIS Cut Line= 6
      2743776.47       968142.52       2743658.9       963561.72
      2738228.49       955968.38      2738129.44       955434.46
      2736640.24       954308.94      2735377.81       952454.75
#Sta/Elev= 30
-10103.2   13.36 -8420.9   10.39 -8320.9   14.07 -7720.9   10.48 -6520.9    9.89
 -5620.9   12.57 -5520.9    9.91 -5000.1   10.17 -3685.6    12.7 -3585.6   10.63
 -2485.6     8.4 -2385.6   10.43 -1985.6    9.48 -1785.6   12.32 -1685.6    7.89
  3614.4   10.29  3814.4    8.27  3957.4   11.44  4057.4    9.84  4157.4    4.61
    4990    2.79  4991.5    -.21  5008.6    -.21  5010.1    2.79  5378.8    6.12
  5924.2    5.77  6024.2   10.42  6224.2   12.02    8282   12.31    8482   14.41
#Mann= 4 , 1 , 0
-10103.2     .14       0 -5000.1     .14       0    4990    .045       0
  5010.1     .14       0
#XS Ineff= 2 , 0
       0    3957    11.4               0
Permanent Ineff=
       F       F
Bank Sta=4990,5010.1
XS Rating Curve= 0 ,0
Exp/Cntr=0.3,0.1

Type RM Length L Ch R = 1 ,66421.5 ,416.3,416.3,416.3
BEGIN DESCRIPTION:
PERQUIMANS RIVER 10.0
END DESCRIPTION:
XS GIS Cut Line= 6
      2744367.64       967899.09      2744332.87       963795.67
      2738574.93       955330.42      2737076.98       954047.97
      2736521.88       953460.75      2735870.95       952296.95
#Sta/Elev= 30
-10391.1   13.38 -9087.5   10.21 -8887.5   14.25 -8787.5   11.54 -7987.5    12.2
 -7887.5    9.93 -6487.5   10.49 -6249.6   14.26 -6149.6   11.17 -5000.1    9.79
 -3749.6   11.86 -2849.6    9.65 -2449.6   13.21 -2349.6    9.86  2450.4    8.31
  3050.4   10.04  3250.4   15.11  3750.4    9.01  4050.2    9.21  4250.2    4.07
  4911.8    4.62  4989.9    2.75  4991.4    -.25  5008.5    -.25    5010    2.75
  5631.8    4.84  5931.8   12.15  6339.8    9.52  6873.3   12.97  8073.3   14.28
#Mann= 4 , 1 , 0
-10391.1     .14       0 -5000.1     .14       0  4989.9    .045       0
    5010     .14       0
#XS Ineff= 2 , 0
       0    3250    15.1               0
Permanent Ineff=
       F       F
Bank Sta=4989.9,5010
XS Rating Curve= 0 ,0
Exp/Cntr=0.3,0.1

Type RM Length L Ch R = 1 ,66005.2 ,421.5,421.5,421.5
BEGIN DESCRIPTION:
PERQUIMANS RIVER 9.0
END DESCRIPTION:
XS GIS Cut Line= 6
      2745341.34       968038.19      2744907.41        963426.2
      2741466.64       959042.25      2737950.46        954023.6
      2736977.98       953245.69      2736620.51       953204.32
#Sta/Elev= 30
-10996.4   12.77 -9564.1    9.74 -9464.1   13.19 -6964.1   11.26 -6764.1   14.27
 -6364.1    10.8 -5000.1   11.02 -4491.1    9.16 -3891.1    11.5 -3791.1   14.75
 -3691.1   10.38 -3391.1    9.49 -2891.1   13.51 -2691.1   10.07 -1791.1    9.02
  -991.1    12.1  1366.9    8.22  2166.9   11.17  2566.9    8.46  3266.9   13.29
  3766.9    8.48    4241    7.88    4441    3.05    4990    2.68  4991.5    -.32
  5008.6    -.32  5010.1    2.68  5786.3    3.27  6086.3   10.96  6946.2   12.53
#Mann= 4 , 1 , 0
-10996.4     .14       0 -5000.1     .14       0    4990    .045       0
  5010.1     .14       0
#XS Ineff= 2 , 0
       0    3267    13.3               0
Permanent Ineff=
       F       F
Bank Sta=4990,5010.1
XS Rating Curve= 0 ,0
Exp/Cntr=0.3,0.1

Type RM Length L Ch R = 1 ,65583.7 ,776.7,776.7,776.7
BEGIN DESCRIPTION:
PERQUIMANS RIVER 8.0
END DESCRIPTION:
XS GIS Cut Line= 6
      2746940.98       968107.74      2746649.11         964086.
      2740125.12       956736.39      2738129.44       953360.28
      2737587.05       952888.71      2736561.33       952928.16
#Sta/Elev= 30
-12035.3   12.71-10702.9    9.66-10502.9   12.68 -9802.9   12.91 -8202.9   10.36
 -8002.9   13.98 -7875.5   11.87 -5000.1    11.3 -4475.5    9.53 -4175.5   12.09
 -3875.5   10.72 -3775.5   13.21 -3575.5   10.64 -1775.5     9.7 -1675.5    6.93
 -1375.5    11.1  1124.5   11.05  1324.5    7.96  1424.5   10.06  2510.1    8.78
  3110.1   15.28  3310.1   10.51  4989.3    2.62  4990.8    -.38  5009.2    -.38
  5010.7    2.62  5479.6    3.02  5679.6   11.03  5779.6   12.06  7524.8   12.45
#Mann= 4 , 1 , 0
-12035.3     .14       0 -5000.1     .14       0  4989.3    .045       0
  5010.7     .14       0
#XS Ineff= 2 , 0
       0    3109    15.3               0
Permanent Ineff=
       F       F
Bank Sta=4989.3,5010.7
XS Rating Curve= 0 ,0
Exp/Cntr=0.3,0.1

Type RM Length L Ch R = 1 ,64807   ,703.1,703.1,703.1
BEGIN DESCRIPTION:
PERQUIMANS RIVER 7.0
END DESCRIPTION:
XS GIS Cut Line= 6
      2750035.93       970854.95       2749755.7        967097.5
      2739940.24       956150.55       2738919.1        953623.5
      2737646.23       952711.18      2736561.33       952790.08
#Sta/Elev= 30
-16694.5   12.84-14526.6    9.51-14426.6   11.96-10623.6   11.73-10523.6    8.92
-10423.6   13.83-10323.6   11.21 -9023.6    8.62 -8923.6   15.15 -8723.6   10.15
 -5000.1   11.72 -4623.6   13.62 -3523.6    8.82 -3123.6   11.41 -1323.6    9.23
  -923.6   12.83   576.4   10.61   676.4    6.59   776.4   10.44  2262.7    12.8
  3562.7    8.46  3713.6    4.36  4989.3    2.57  4990.8    -.43  5009.1    -.43
  5010.6    2.57  5229.7    6.69  5286.3    4.92  5486.3   11.86  7174.1    12.6
#Mann= 4 , 1 , 0
-16694.5     .14       0 -5000.1     .14       0  4989.3    .045       0
  5010.6     .14       0
#XS Ineff= 2 , 0
       0    2265    12.8               0
Permanent Ineff=
       F       F
Bank Sta=4989.3,5010.6
XS Rating Curve= 0 ,0
Exp/Cntr=0.3,0.1

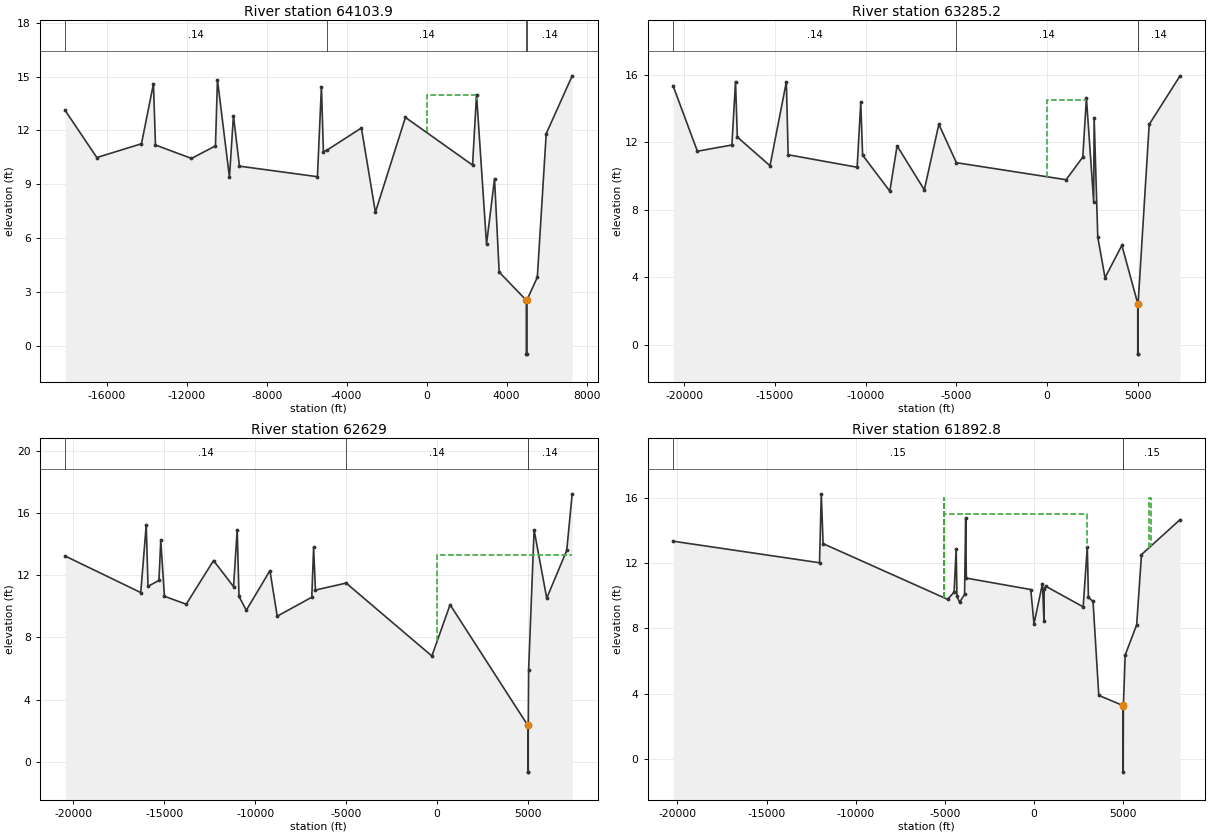
Type RM Length L Ch R = 1 ,64103.9 ,818.7,818.7,818.7
BEGIN DESCRIPTION:
PERQUIMANS RIVER 6.0
END DESCRIPTION:
XS GIS Cut Line= 6
      2751531.25       971098.37      2751611.22       968515.42
      2740194.67       956145.22       2739278.3       954081.73
      2738750.85       951803.82      2737409.53       951882.72
#Sta/Elev= 30
-18078.8   13.12-16494.6   10.49-14261.3   11.26-13661.3   14.61-13561.3   11.19
-11761.3   10.44-10561.3   11.14-10461.3   14.83 -9861.3    9.39 -9661.3   12.83
 -9361.3   10.01 -5461.3    9.42 -5261.3   14.45 -5161.3   10.82 -5000.1   10.89
 -3261.3   12.14 -2561.3    7.44 -1061.3   12.73  2296.5   10.07  2496.5      14
  2996.5    5.66  3396.5    9.31  3628.7     4.1  4989.3    2.52  4990.8    -.48
  5009.1    -.48  5010.6    2.52  5537.1    3.81  5980.7   11.82  7280.7   15.05
#Mann= 4 , 1 , 0
-18078.8     .14       0 -5000.1     .14       0  4989.3    .045       0
  5010.6     .14       0
#XS Ineff= 2 , 0
       0    2481      14               0
Permanent Ineff=
       F       F
Bank Sta=4989.3,5010.6
XS Rating Curve= 0 ,0
Exp/Cntr=0.3,0.1

Type RM Length L Ch R = 1 ,63285.2 ,656.2,656.2,656.2
BEGIN DESCRIPTION:
PERQUIMANS RIVER 5.0
END DESCRIPTION:
XS GIS Cut Line= 6
      2755217.37       971863.42      2742142.06       957744.86
      2740438.09       956040.89      2739694.17       953503.41
      2739263.71       951665.74      2737527.88       951744.64
#Sta/Elev= 30
-20609.3   15.35-19266.2   11.46-17366.2   11.83-17166.2   15.59-17066.2    12.3
-15266.2    10.6-14366.2   15.57-14266.2   11.25-10466.2   10.51-10266.2   14.35
-10166.2   11.23 -8666.2    9.09 -8266.2   11.78 -6766.2    9.17 -5966.2   13.06
 -5000.1   10.78  1043.6    9.77  1962.5   11.11  2162.5   14.61  2562.5    8.47
  2587.9   13.45  2787.9    6.37  3187.9    3.96  4114.6    5.88  4989.3    2.43
  4990.8    -.57  5009.1    -.57  5010.6    2.43  5620.9   13.05  7320.9   15.93
#Mann= 4 , 1 , 0
-20609.3     .14       0 -5000.1     .14       0  4989.3    .045       0
  5010.6     .14       0
#XS Ineff= 2 , 0
       0  2156.3    14.5               0
Permanent Ineff=
       F       F
Bank Sta=4989.3,5010.6
XS Rating Curve= 0 ,0
Exp/Cntr=0.3,0.1

Type RM Length L Ch R = 1 ,62629   ,736.2,736.2,736.2
BEGIN DESCRIPTION:
PERQUIMANS RIVER 4.0
END DESCRIPTION:
XS GIS Cut Line= 5
      2756051.97       971376.57      2740372.86       954336.66
      2740299.38       953160.99      2739914.65       951567.11
      2738021.01       951606.56
#Sta/Elev= 30
-20442.2   13.24-16286.4   10.89-15986.4   15.23-15886.4   11.29-15286.4   11.67
-15186.4   14.26-14986.4   10.65-13786.4   10.14-12286.4   12.95-11186.4   11.27
-10986.4   14.92-10886.4   10.64-10486.4    9.75 -9186.4    12.3 -8786.4    9.37
 -6886.4   10.59 -6786.4   13.81 -6686.4   11.05 -5000.1    11.5  -286.4    6.81
   713.6   10.11  4989.3    2.34  4990.8    -.66  5009.2    -.66  5010.7    2.34
  5031.3    5.92  5331.3   14.92  6025.3   10.53  7125.3    13.6  7425.3   17.24
#Mann= 4 , 1 , 0
-20442.2     .14       0 -5000.1     .14       0  4989.3    .045       0
  5010.7     .14       0
#XS Ineff= 2 , 0
       0 -5686.7    13.3               0
Permanent Ineff=
       F       F
Bank Sta=4989.3,5010.7
XS Rating Curve= 0 ,0
Exp/Cntr=0.3,0.1

Type RM Length L Ch R = 1 ,61892.8 ,61892.8,61892.8,61892.8
BEGIN DESCRIPTION:
PERQUIMANS RIVER 3.0
END DESCRIPTION:
XS GIS Cut Line= 6
      2757095.21       970889.72      2741192.66       953295.45
      2741077.51       952612.74        2740709.       951717.79
      2740644.48       951409.31      2737902.66       951527.66
#Sta/Elev= 30
-20247.2   13.33-12031.1   12.01-11931.1   16.23-11831.1   13.18 -4847.3    9.77
   -4484   10.21 -4367.2   12.86 -4324.8    9.98 -4176.5    9.59 -3897.5   10.07
 -3833.6   14.76 -3798.2   11.07  -184.6   10.37    -3.3    8.27   472.2   10.73
   556.3    8.42   567.9   10.42   658.2   10.57  2755.5    9.31  2986.6   12.99
  3049.5    9.89  3307.7    9.64  3630.7    3.89 4978.41    3.27 4999.84    -.81
 5009.94    3.26  5111.5    6.36  5754.7    8.21  6025.7   12.51  8188.6   14.65
#Mann= 3 ,-1 , 0
-20247.2     .15       0 4978.41    .045       0 5009.94     .15       0
#XS Ineff= 3 ,-1
 -5049.8 -5048.8      16 -5048.8  2986.6      15  6441.1  6532.4      16
Permanent Ineff=
       F       F       F
Bank Sta=4978.41,5009.94
XS Rating Curve= 0 ,0
Exp/Cntr=0.3,0.1
Stream Node=Perquimans River,Reach - 1       , 0 , 0 ,Upstream end
Stream Node=Perquimans River,Reach - 1       , 0 , 1 ,Downstream end

Chan Stop Cuts=-1
Use User Specified Reach Order=0